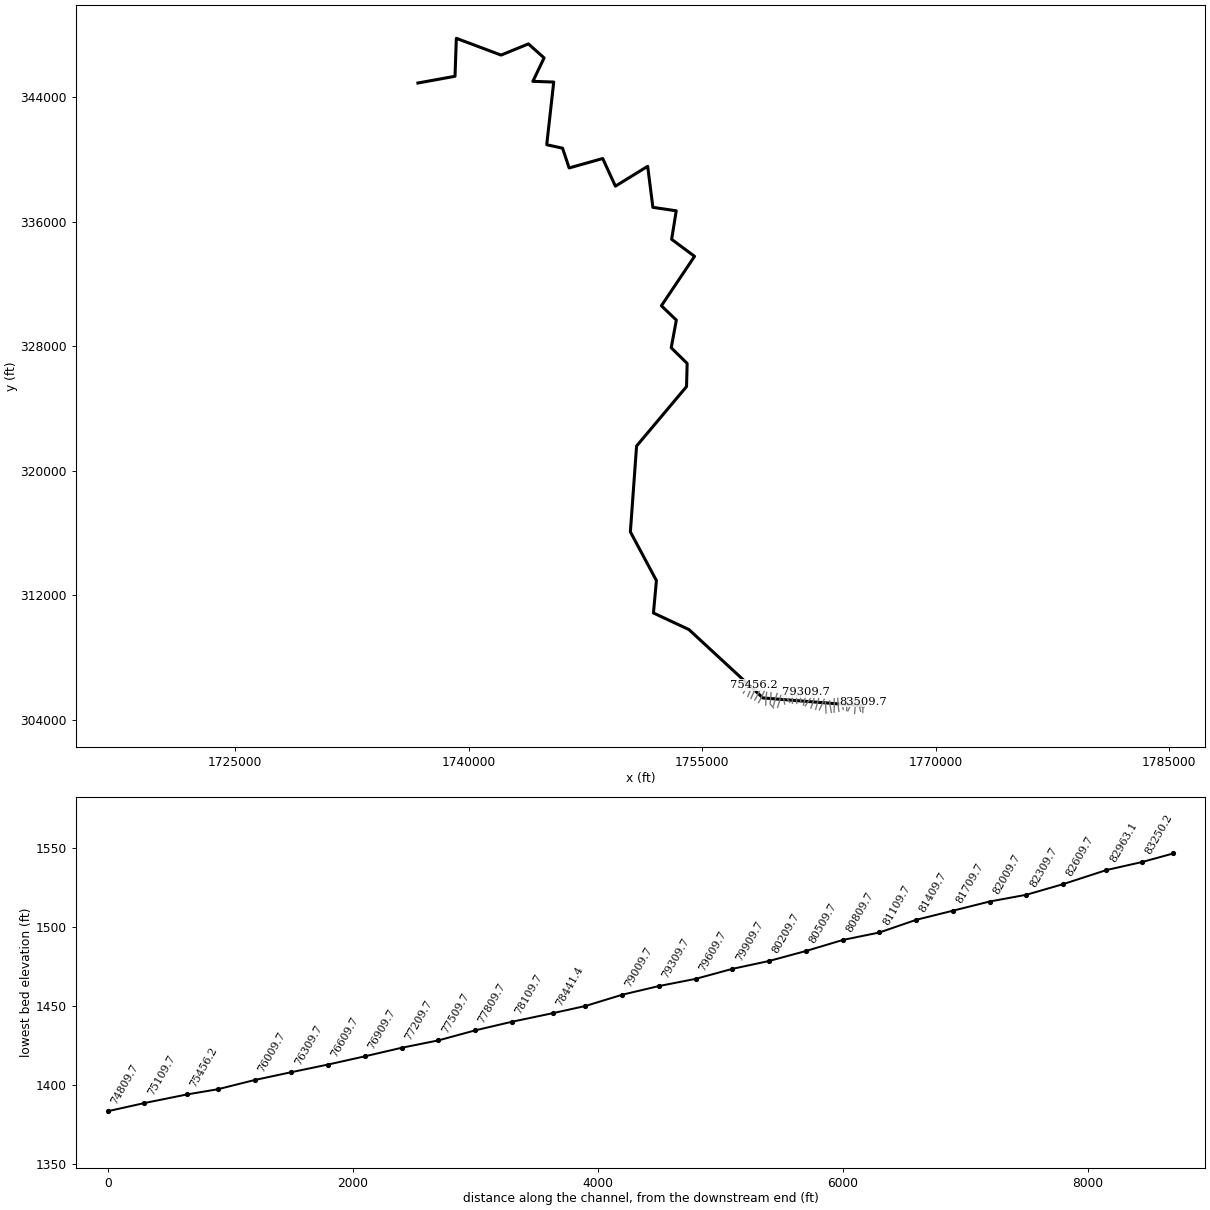
--- SPLAURFK.prj (project) ---

Proj Title=SPLAURFK
Current Plan=p01
Default Exp/Contr=0,0
English Units
Geom File=g01
Flow File=f01
Plan File=p01
BEGIN DESCRIPTION:
END DESCRIPTION:
DSS Export Rating Curves= 0
DSS Export Rating Curve Sorted= 0
DSS Export Volume Flow Curves= 0
DXF OffsetX= 0
DXF OffsetY= 0
DXF ScaleX= 0
DXF ScaleY= 0

--- SPLAURFK.p01 (plan) ---

Plan Title=Floodplain
Program Version=4.00
Geom File=g01
Flow File=f01
K Sum by GR=0
Std Step Tol=0.01
Critical Tol=0.01
Num of Std Step Trials=20
Max Error Tol=0.3
Flow Tol Ratio=0.001
Split Flow NTrial=30
Split Flow Tol=0.02
Split Flow Ratio=0.02
Log Output Level=0
Friction Slope Method=1
Unsteady Friction Slope Method=2
Unsteady Bridges Friction Slope Method=1
Global Log Level=0
CheckData=False
Run HTab=0
Run UNet=0
Run PostProcess=0
UNET Theta=0
UNET Theta Warmup=0
UNET ZTol=0
UNET ZSATol=0
UNET MxIter=0
UNET MaxInSteps=0
UNET DtIC=0
UNET DtMin=0
UNET MaxCRTS=0
UNET WFStab=0
UNET SFStab=0
UNET WFX=0
UNET SFX=0
UNET DSS MLevel=0
UNET DZMax Abort=0
UNET Convert EG Bridges=0
UNET Use Existing IB Tables=0
UNET Froude Limit=0
UNET Froude Power=0
Write IC File=0
Echo Input=False
Echo Output=False
Write Detailed=0

--- SPLAURFK.f01 (steady flow) ---

Flow Title=NFF Regression Equation
Program Version=4.10
Number of Profiles= 1
Profile Names=P100yr
River Rch & RM=SPLAURFK,Main            ,83509.7
1046.105
River Rch & RM=SPLAURFK,Main            ,82009.7
1112.025
River Rch & RM=SPLAURFK,Main            ,81709.7
1218.976
River Rch & RM=SPLAURFK,Main            ,79909.7
1349.528
River Rch & RM=SPLAURFK,Main            ,76609.7
1776.607
River Rch & RM=SPLAURFK,Main            ,76309.7
1890.583
River Rch & RM=SPLAURFK,Main            ,72709.7
2065.322
River Rch & RM=SPLAURFK,Main            ,70009.7
2270.315
River Rch & RM=SPLAURFK,Main            ,61609.7
2522.399
River Rch & RM=SPLAURFK,Main            ,57109.7
2800.192
River Rch & RM=SPLAURFK,Main            ,51409.7
3673.811
River Rch & RM=SPLAURFK,Main            ,50809.7
3958.125
River Rch & RM=SPLAURFK,Main            ,42331.9
4380.245
River Rch & RM=SPLAURFK,Main            ,39109.7
4819.621
River Rch & RM=SPLAURFK,Main            ,29209.7
5153.663
River Rch & RM=SPLAURFK,Main            ,15409.7
5711.648
Boundary for River Rch & Prof#=SPLAURFK,Main            , 1
Up Type= 0
Dn Type= 1
Dn Known WS=816.65
DSS Import GetInterval= 0
DSS Import GetPeak= 0
DSS Import FillOption= 0

--- SPLAURFK.g01 (geometry) ---

Geom Title=USGS 10m DEM
Program Version=4.10

River Reach=SPLAURFK        ,Main
Reach XY= 30
     1765331.191        304893.2     1758891.955       305401.88
     1754141.065      309793.482     1751862.324      310858.187
     1752052.211      312941.303     1750380.119      316068.039
      1750778.34      321581.928     1753987.198      325400.439
       1754026.3      326887.092     1753003.135      327890.706
     1753332.894       329669.71     1752372.291      330589.255
     1754502.039      333764.586     1753030.506      334857.483
     1753326.376      336689.404     1751826.169      336910.982
     1751491.196      339547.359     1749417.898      338271.575
     1748603.669      340047.232     1746446.396      339441.631
     1746024.794       340710.64     1745007.732      340932.308
      1745457.53      344959.203     1744117.686      345003.473
     1744837.738      346510.114     1743831.227      347408.552
     1742077.321      346691.104     1739202.321      347766.494
     1739116.384      345329.385     1736734.873      344896.768

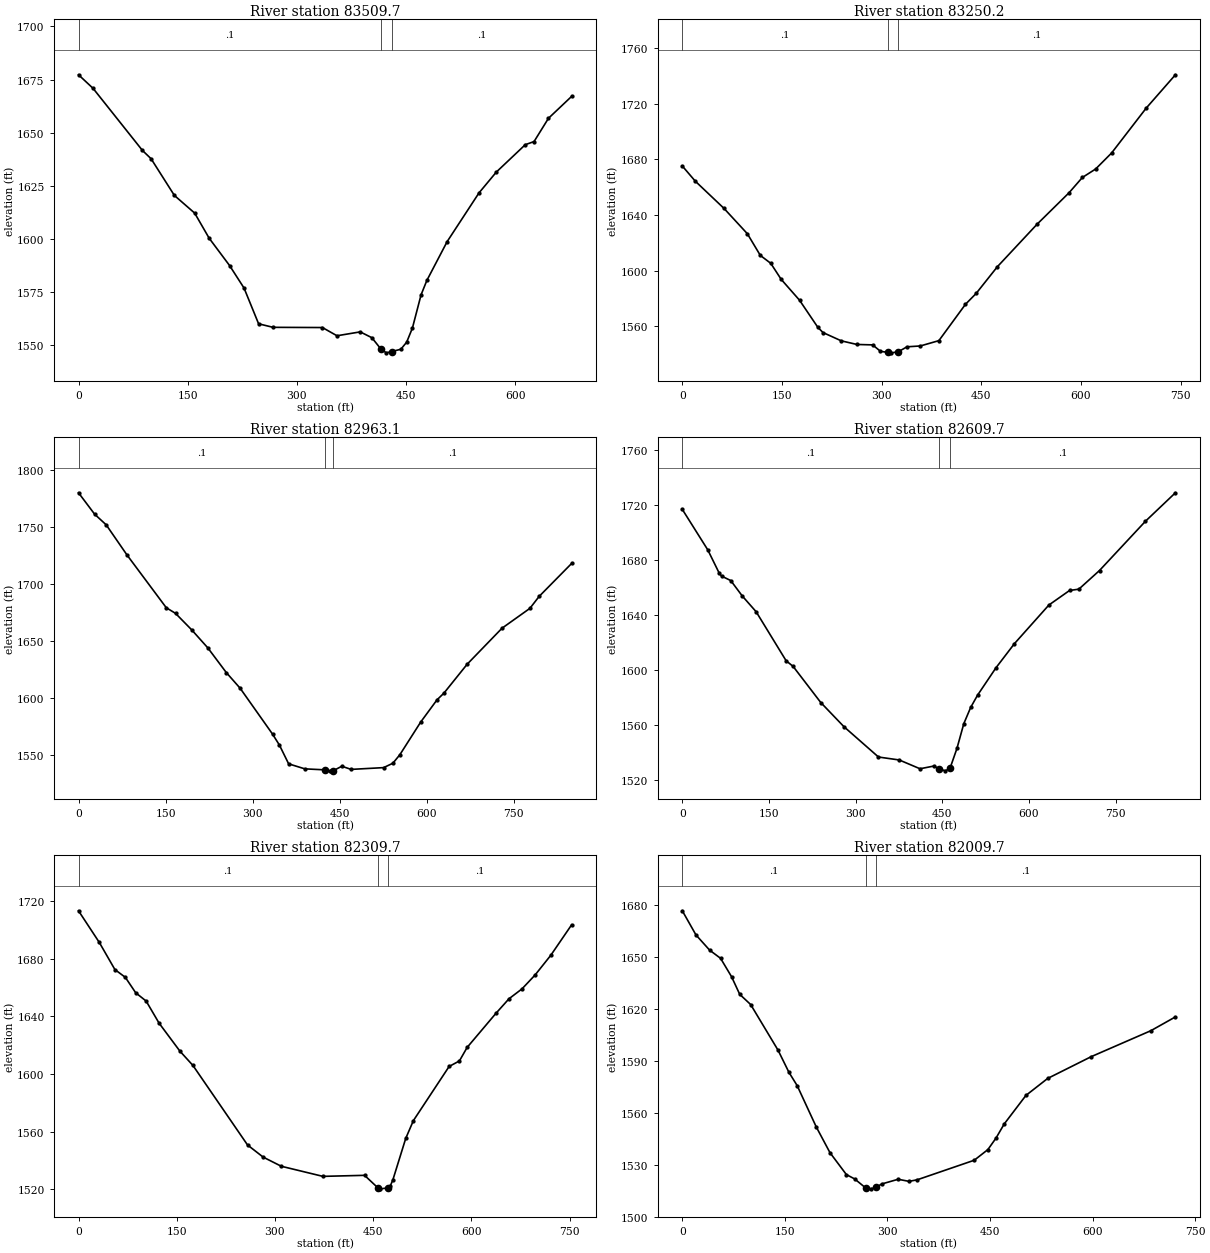
Type RM Length L Ch R = 1 ,83509.7 ,251.8,259.4,265.1
XS GIS Cut Line= 3
     1765307.846      304473.094     1765321.533      304895.791
     1765318.492      305150.301
#Sta/Elev= 30
       0 1677.25      20 1670.86    87.8 1641.66    99.7 1637.75   131.7 1620.49
   159.6 1612.17   179.5 1600.35   207.5 1587.52   227.4 1576.91   247.4  1560.1
   267.3 1558.44   335.1 1558.34   355.1 1554.47     387  1556.3     403 1553.56
   415.4 1548.24   422.9 1546.44   430.4 1547.06   442.8 1548.13   450.8 1551.46
   458.7  1558.1   470.6 1573.75   478.6 1580.55   506.4 1598.76   550.2  1621.7
     574 1631.49   613.8 1644.38   625.8 1645.83   645.6 1656.78   677.4 1667.08
#Mann= 3 , 0 , 0
       0      .1       0   415.4    .045       0   430.4      .1       0
Bank Sta=415.4,430.4
XS Rating Curve= 0 ,0
Exp/Cntr=0.3,0.1

Type RM Length L Ch R = 1 ,83250.2 ,296.7,287.2,277.6
XS GIS Cut Line= 4
     1765166.582      304544.833     1765142.323      304675.705
     1765081.946      304837.801     1764955.561      305255.043
#Sta/Elev= 30
       0 1675.26    19.6 1664.32    62.6 1644.84    97.9 1626.56   117.4 1610.98
   133.1 1605.29   148.8 1593.76   176.4 1578.76   203.9 1559.31   211.7 1555.51
   239.2 1549.55   262.8 1546.94   286.4 1546.64   298.2 1542.02   309.7  1541.2
   314.1 1540.92   324.7 1541.61   338.1 1545.26   358.1 1545.86   386.1 1549.69
   426.1 1575.82   442.1 1583.59   474.1 1602.84   534.1 1633.52     582 1656.04
     602 1667.01     622 1673.11     646 1684.62     698 1716.85     742 1740.85
#Mann= 3 , 0 , 0
       0      .1       0   309.7    .045       0   324.7      .1       0
Bank Sta=309.7,324.7
XS Rating Curve= 0 ,0
Exp/Cntr=0.3,0.1

Type RM Length L Ch R = 1 ,82963.1 ,362.1,353.4,344.9
XS GIS Cut Line= 3
      1764782.56      304409.739      1764819.36      304837.801
     1764875.117      305253.982
#Sta/Elev= 30
       0 1779.91    27.8 1761.11    47.7 1751.78    83.5 1725.36   151.2 1679.05
   167.1 1674.11   194.9 1659.69   222.8  1643.8   254.6 1622.17   278.5 1608.36
   334.2 1568.21   346.1 1558.53     362 1542.06   389.9 1537.66   424.1  1536.8
   433.6 1535.92   439.1 1536.08   453.6 1539.96   469.6 1537.19   525.6 1538.74
   541.6  1542.6   553.6 1550.06   589.6  1578.8   617.6 1598.22   629.6 1604.15
   669.6 1629.51   729.6 1661.07   777.6 1678.48   793.6 1689.01   849.5 1717.88
#Mann= 3 , 0 , 0
       0      .1       0   424.1    .045       0   439.1      .1       0
Bank Sta=424.1,439.1
XS Rating Curve= 0 ,0
Exp/Cntr=0.3,0.1

Type RM Length L Ch R = 1 ,82609.7 ,289.9,300,311
XS GIS Cut Line= 3
     1764351.152      304569.652     1764550.931      304974.504
     1764738.209      305330.323
#Sta/Elev= 30
       0  1716.9      44 1687.57    63.9 1670.58    67.9 1668.47    83.9 1665.19
   103.9 1653.95   127.8 1642.57   179.8 1606.91   191.8 1602.88   239.7 1576.63
   279.7 1559.12   339.6 1537.04   375.6  1534.9   411.5 1528.52   435.5 1530.49
     444 1528.51   455.4 1527.01   463.4 1528.81   475.4 1543.24   487.3 1561.26
   499.2 1573.06   511.2 1582.02     543 1601.86   574.9 1619.37   634.6 1647.44
   670.4    1658   686.4 1658.94   722.2  1672.5   801.8  1708.3   853.6 1728.95
#Mann= 3 , 0 , 0
       0      .1       0     444    .045       0   463.4      .1       0
Bank Sta=444,463.4
XS Rating Curve= 0 ,0
Exp/Cntr=0.3,0.1

Type RM Length L Ch R = 1 ,82309.7 ,296.1,300,302.6
XS GIS Cut Line= 4
     1764272.114      304590.856     1764276.879      305055.497
     1764273.178      305176.434      1764352.78      305323.912
#Sta/Elev= 30
       0 1713.37    31.8 1691.36    55.6 1672.54    71.5 1667.16    87.4 1656.41
   103.3 1650.68   123.1 1635.31   154.9 1615.89   174.8 1605.95   258.2 1550.73
     282 1542.32   309.8 1535.95   373.3 1528.94   436.9 1529.66   457.2 1521.02
   460.7 1520.28   472.2 1520.87   476.4 1522.48   480.3 1526.69   499.8 1555.28
   511.5 1567.65   566.1 1605.26   581.8 1609.09   593.6 1618.48   637.5  1642.1
   657.5 1652.25   677.4 1659.13   697.4 1668.78   721.3 1682.41   753.2 1703.61
#Mann= 3 , 0 , 0
       0      .1       0   457.2    .045       0   472.2      .1       0
Bank Sta=457.2,472.2
XS Rating Curve= 0 ,0
Exp/Cntr=0.3,0.1

Type RM Length L Ch R = 1 ,82009.7 ,301.2,300,297.8
XS GIS Cut Line= 3
     1764053.301       304662.02      1764008.17      304934.253
     1763941.856      305374.549
#Sta/Elev= 30
       0 1676.77      20  1662.8      40    1654      56 1649.27      72 1638.68
      84 1628.46     100 1622.55     140 1596.19     156 1583.34     168 1575.68
     196 1551.74     216  1536.9     240 1524.24     252 1521.75   268.4 1516.46
     276    1516   283.4 1516.93   291.8 1518.83   315.7 1521.53   331.6 1520.32
   343.5 1521.22     427 1532.54   446.9 1538.68   458.8 1545.33   470.8  1553.5
   502.6 1570.02   534.4 1579.84     598 1592.41   685.4 1607.45   721.2 1615.41
#Mann= 3 , 0 , 0
       0      .1       0   268.4    .045       0   283.4      .1       0
Bank Sta=268.4,283.4
XS Rating Curve= 0 ,0
Exp/Cntr=0.3,0.1

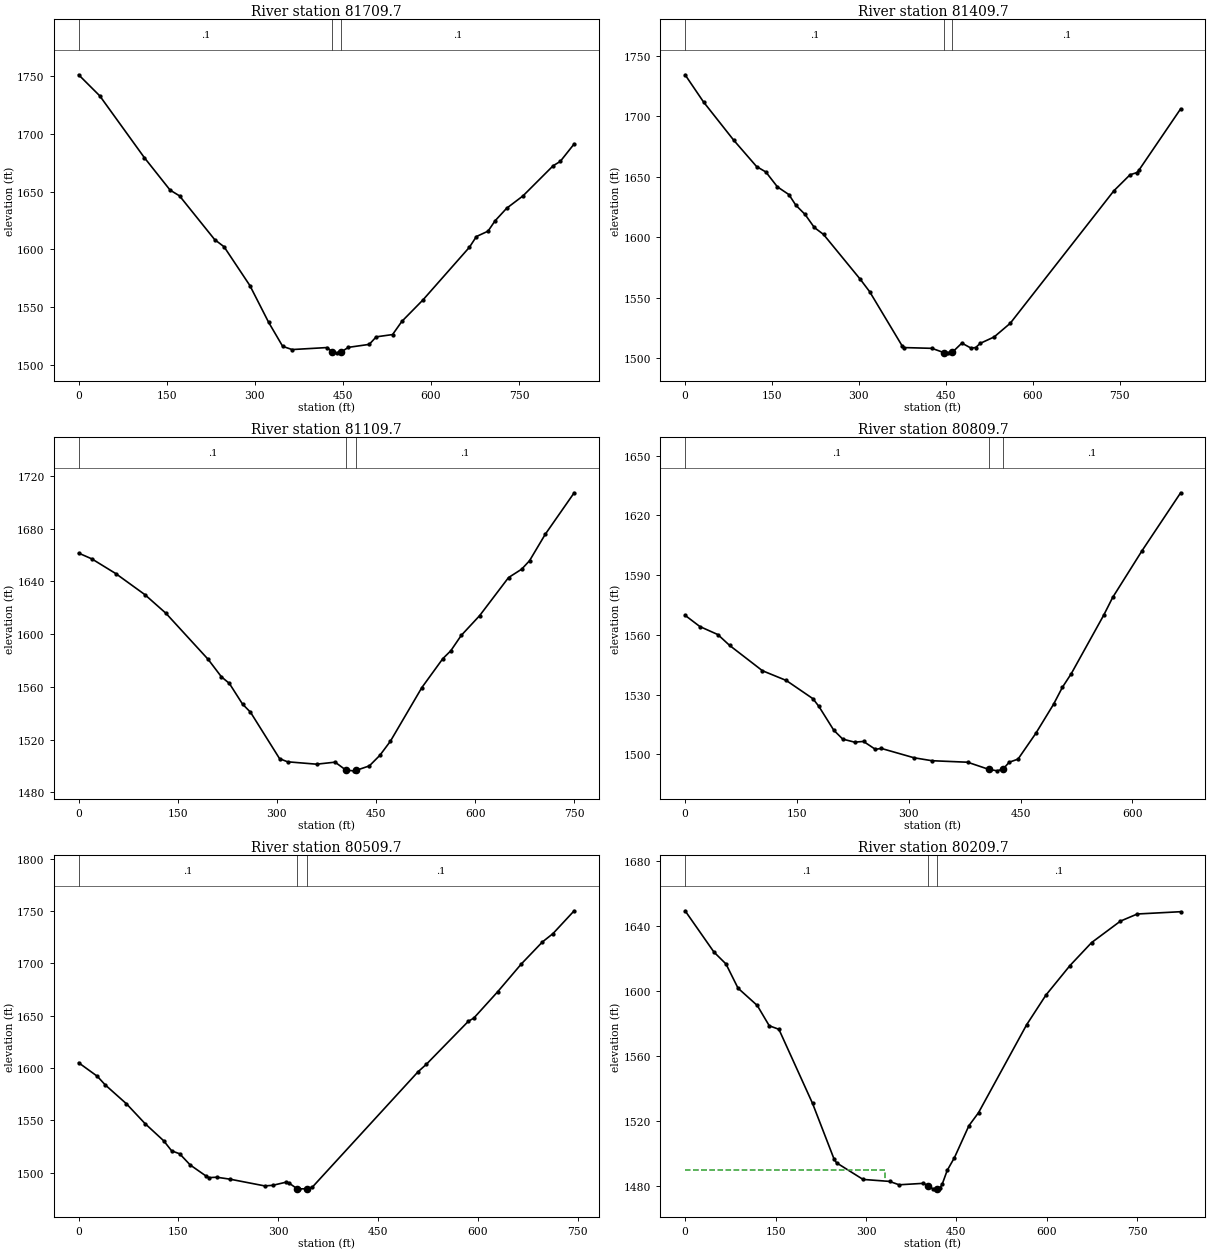
Type RM Length L Ch R = 1 ,81709.7 ,303.3,300,299.3
XS GIS Cut Line= 3
     1763772.208      304537.898     1763722.289      304974.473
     1763701.011       305378.42
#Sta/Elev= 30
       0 1751.35      36 1733.07   111.8 1679.57   155.8 1651.32   171.8 1646.35
   231.7 1608.38   247.7 1602.18   291.6 1568.58   323.6 1536.62   347.5 1515.82
   363.5 1513.03   423.4 1514.78   431.9 1510.79   439.4 1510.19   446.9 1510.83
   459.2 1514.93   494.9 1517.53   506.8 1524.06   534.6 1526.03   550.5 1537.49
   586.2 1555.98   665.5 1601.77   677.4 1611.06   697.2 1615.72   709.1 1624.64
   728.9 1635.58   756.7  1646.3   808.2  1672.5   820.1 1676.15   843.9 1691.39
#Mann= 3 , 0 , 0
       0      .1       0   431.9    .045       0   446.9      .1       0
Bank Sta=431.9,446.9
XS Rating Curve= 0 ,0
Exp/Cntr=0.3,0.1

Type RM Length L Ch R = 1 ,81409.7 ,296.9,300,299.8
XS GIS Cut Line= 3
     1763462.502      304489.125     1763480.319      304942.659
     1763467.185      305343.865
#Sta/Elev= 30
       0 1734.32    31.8 1711.85    83.6 1680.42   123.4 1658.44   139.4 1653.96
   159.3 1641.66   179.2 1635.25   191.1  1626.5     207 1618.89     223 1608.07
   238.9 1602.32   302.6 1565.08   318.5    1555   374.3 1510.43   378.2 1508.76
     426 1508.13   446.4 1504.64   453.9 1504.41   461.4 1504.96   477.7 1512.45
   493.6  1508.3   501.6 1508.82   509.5 1512.28   533.4 1517.54   561.2 1528.85
     740 1638.36   767.9 1651.61   779.8 1653.46   783.8 1655.79   855.3 1706.15
#Mann= 3 , 0 , 0
       0      .1       0   446.4    .045       0   461.4      .1       0
Bank Sta=446.4,461.4
XS Rating Curve= 0 ,0
Exp/Cntr=0.3,0.1

Type RM Length L Ch R = 1 ,81109.7 ,301.5,300,299.8
XS GIS Cut Line= 3
     1763289.095      304469.234     1763214.769      304874.465
     1763167.884      305208.895
#Sta/Elev= 30
       0 1661.44      20 1657.06      56 1645.98     100 1630.05     132 1615.88
     196 1580.88     216 1567.68     228 1562.69     248 1546.97     260 1540.85
     304 1505.65     316 1503.27     360 1501.45     388 1502.99   404.5 1496.92
     416 1496.41   419.5 1496.71   439.8 1500.15   455.7 1508.15   471.6 1518.81
   519.3 1559.56     551 1581.46     563 1587.39   578.8 1599.03   606.7 1614.06
   650.4 1642.91   670.2 1649.24   682.2  1655.7     706 1675.75   749.7 1707.17
#Mann= 3 , 0 , 0
       0      .1       0   404.5    .045       0   419.5      .1       0
Bank Sta=404.5,419.5
XS Rating Curve= 0 ,0
Exp/Cntr=0.3,0.1

Type RM Length L Ch R = 1 ,80809.7 ,311.4,300,288.6
XS GIS Cut Line= 3
     1762947.676      304439.391      1762925.88      304853.582
     1762905.297      305102.558
#Sta/Elev= 30
       0 1569.79    19.9 1564.13    43.9 1560.12    59.8 1554.64   103.7 1541.95
   135.6 1537.07   171.5 1527.88   179.5 1523.98   199.4 1512.06   211.4 1507.59
   227.3 1506.05   239.3 1506.41   255.2 1502.45   263.2  1502.9   307.1  1498.2
     331 1496.73   378.9 1495.97   407.3 1492.38   418.7 1491.64   426.7 1492.63
   434.6 1495.95   446.5 1497.53   470.3 1510.45   494.1 1525.05     506 1533.61
   517.9 1540.46   561.5 1569.91   573.4 1578.75     613 1602.35   664.6 1631.37
#Mann= 3 , 0 , 0
       0      .1       0   407.3    .045       0   426.7      .1       0
Bank Sta=407.3,426.7
XS Rating Curve= 0 ,0
Exp/Cntr=0.3,0.1

Type RM Length L Ch R = 1 ,80509.7 ,296.1,300,303.2
XS GIS Cut Line= 3
     1762519.012      304638.149     1762662.319      304941.478
     1762828.822      305315.197
#Sta/Elev= 30
       0 1605.07      28 1592.19    39.9 1583.96    71.9 1565.86    99.8 1546.97
   127.8 1530.57   139.8 1520.93   151.8 1518.15   167.7 1507.44   191.7  1496.8
   195.7  1495.4   207.7 1495.76   227.6 1493.89   279.6 1487.48   291.6 1488.03
   311.5 1491.01   315.5 1490.46     328 1484.93   331.5 1484.68     343 1484.73
   351.4 1486.46   510.2 1596.58   522.2 1603.41   585.7 1644.71   593.7 1647.64
   629.4 1672.67   665.2 1699.39   696.9 1720.41   712.8  1728.4   744.6 1750.16
#Mann= 3 , 0 , 0
       0      .1       0     328    .045       0     343      .1       0
Bank Sta=328,343
XS Rating Curve= 0 ,0
Exp/Cntr=0.3,0.1

Type RM Length L Ch R = 1 ,80209.7 ,301.9,300,299.9
XS GIS Cut Line= 3
     1762279.811       304667.73     1762389.261      305063.786
     1762501.838      305459.144
#Sta/Elev= 30
       0 1649.49    47.9 1624.06    67.8 1616.77    87.8 1601.87   119.7 1591.22
   139.6 1578.73   155.6 1576.56   211.4 1530.96   247.3 1496.51   251.3 1494.37
   295.2 1484.17   339.1 1482.96     355 1480.87   394.9 1481.76   403.4 1480.36
   410.9 1478.38   418.4  1478.4   422.9 1478.96   426.9 1481.66   434.8 1489.74
   446.8 1497.59   470.8 1517.24   486.7 1525.22   566.6 1579.39   598.5 1597.59
   638.4 1615.77   674.3 1629.92   722.2 1643.14   750.1 1647.51     822 1648.92
#Mann= 3 , 0 , 0
       0      .1       0   403.4    .045       0   418.4      .1       0
#XS Ineff= 2 , 0
          331.26 1490.24
Permanent Ineff=
       F       F
Bank Sta=403.4,418.4
XS Rating Curve= 0 ,0
Exp/Cntr=0.3,0.1

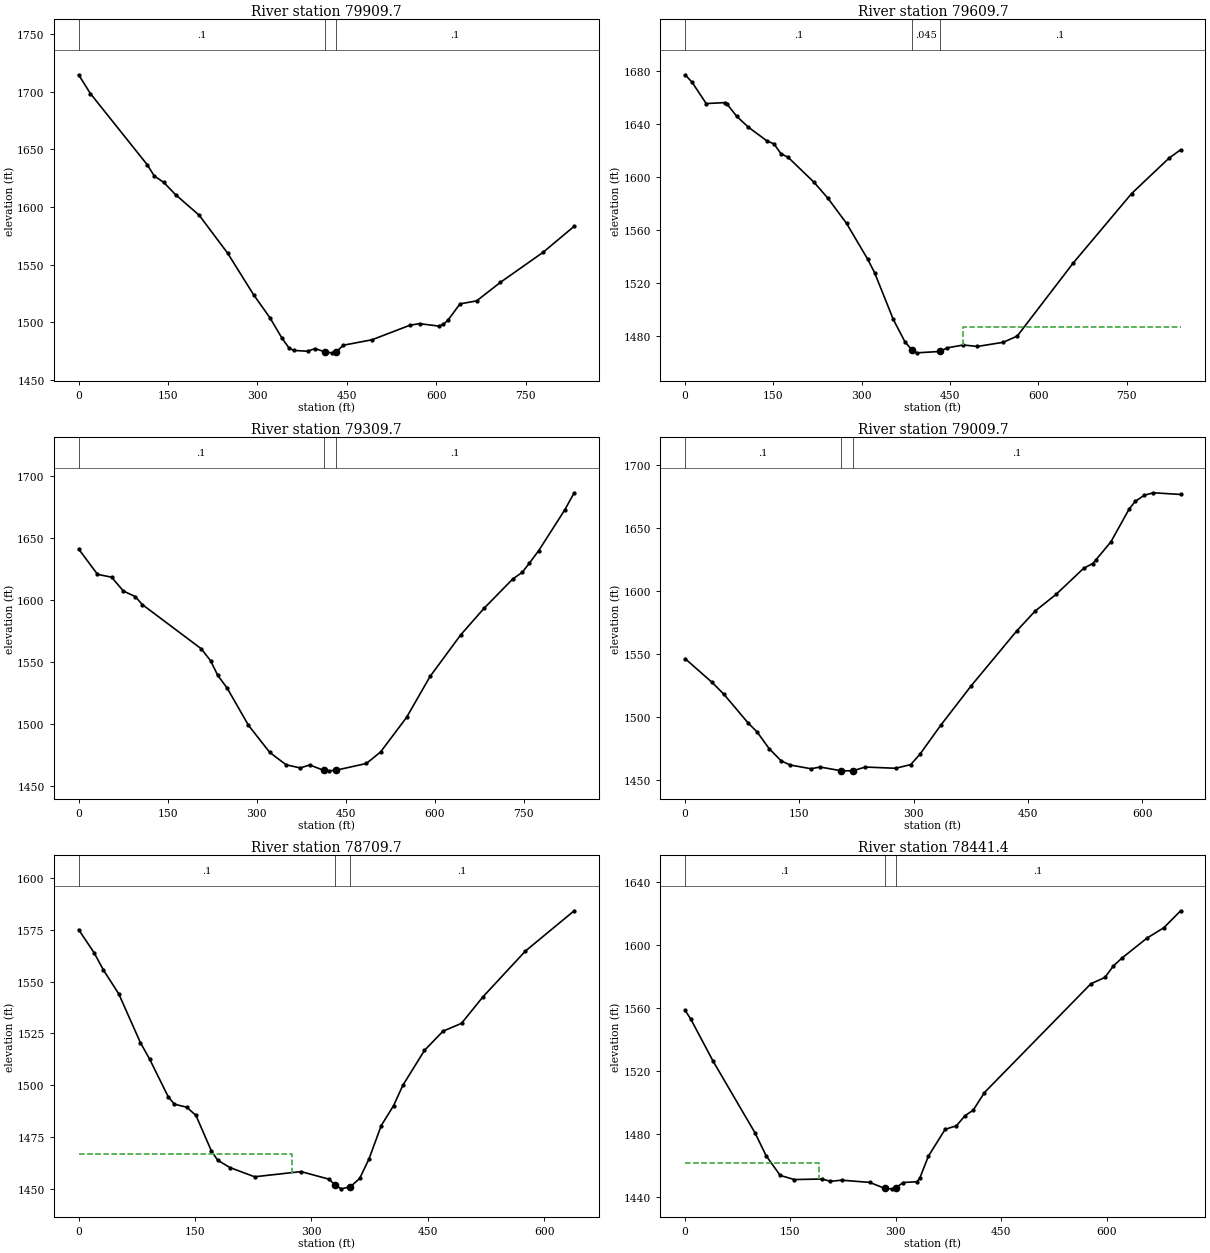
Type RM Length L Ch R = 1 ,79909.7 ,306.4,300,291.3
XS GIS Cut Line= 3
     1761975.796      304755.173     1762120.072      305149.955
     1762211.229      305550.547
#Sta/Elev= 30
       0 1714.86    19.8 1698.52     115  1636.8   126.9    1627   142.8 1621.38
   162.6 1610.75   202.2  1592.9   249.8 1560.05   293.4 1523.92   321.2  1503.6
     341 1486.23   352.9  1477.6   360.8 1475.49   384.6  1474.8   396.5 1477.14
   412.8 1474.25   424.3  1473.4   432.3 1474.44   444.2 1480.04   492.1 1484.75
   555.9 1497.41   571.9 1498.75   603.8 1496.64   611.8  1498.1   619.8 1501.95
   639.7 1515.93   667.6  1518.5   707.5 1534.63   779.3 1560.79   831.2  1583.3
#Mann= 3 , 0 , 0
       0      .1       0   412.8    .045       0   432.3      .1       0
Bank Sta=412.8,432.3
XS Rating Curve= 0 ,0
Exp/Cntr=0.3,0.1

Type RM Length L Ch R = 1 ,79609.7 ,291.5,300,310
XS GIS Cut Line= 3
     1761613.555      304895.001     1761855.866      305244.342
     1762091.081      305587.956
#Sta/Elev= 30
       0 1676.79    11.9 1671.14    35.8 1655.08    67.6 1655.79    71.5 1654.51
    87.4  1645.6   107.3 1637.33   139.1 1626.89     151 1624.65   162.9  1617.2
   174.8 1614.61   218.5 1595.91   242.4 1583.76   274.2 1564.69   309.9 1537.84
   321.8 1527.52   353.6 1492.25   373.5 1475.29   385.4 1469.11   393.4 1467.05
   432.7 1468.08     445  1470.8   472.7 1472.97   496.5 1471.87   540.2    1475
     564 1479.65   659.1 1534.78   758.3 1587.18   821.7 1613.86   841.6 1620.23
#Mann= 3 , 0 , 0
       0      .1       0   385.4    .045       0   432.7      .1       0
#XS Ineff= 2 , 0
                          471.45         1486.61
Permanent Ineff=
       F       F
Bank Sta=385.4,432.7
XS Rating Curve= 0 ,0
Exp/Cntr=0.3,0.1

Type RM Length L Ch R = 1 ,79309.7 ,293.8,300,302.4
XS GIS Cut Line= 3
     1761494.067      304943.201     1761595.275      305360.379
     1761667.007      305760.002
#Sta/Elev= 30
       0 1641.38    31.8 1620.95    55.6 1618.64    75.5 1607.46    95.4 1603.02
   107.3 1596.59   206.7 1560.93   222.6 1551.17   234.5 1539.48   250.4  1529.2
   286.2 1499.31     322 1477.42   349.8 1467.38   373.6 1464.86   389.5 1467.25
   413.4 1462.85   421.3 1462.51   433.3 1462.95     485 1468.44   508.9 1477.69
   552.7 1505.54   592.5  1538.7   644.2 1572.22     684 1593.89   731.8 1617.19
   747.7 1622.53   759.7 1629.91   775.6 1640.12   819.4 1672.85   835.3  1686.7
#Mann= 3 , 0 , 0
       0      .1       0   413.4    .045       0   433.3      .1       0
Bank Sta=413.4,433.3
XS Rating Curve= 0 ,0
Exp/Cntr=0.3,0.1

Type RM Length L Ch R = 1 ,79009.7 ,301.3,300,299.6
XS GIS Cut Line= 3
     1761316.755       305126.43     1761306.996      305338.688
     1761326.129      305775.967
#Sta/Elev= 30
       0 1546.06    35.4 1527.23    51.2  1517.6    82.6 1495.06    94.4 1487.95
   110.2 1474.69   125.9 1465.02   137.7 1461.66   165.3 1458.66   177.1 1460.04
     205 1457.05     220 1457.01   236.4 1460.02   276.2 1459.05     296 1461.95
     308 1470.09   335.8 1493.49   375.6 1524.67   435.3 1568.17   459.2 1583.78
     487 1597.19   522.8 1617.67   534.8 1621.55   538.8 1624.29   558.7 1638.76
   582.5 1664.66   590.5 1670.81   602.4 1675.73   614.4  1677.7   650.2 1676.37
#Mann= 3 , 0 , 0
       0      .1       0     205    .045       0     220      .1       0
Bank Sta=205,220
XS Rating Curve= 0 ,0
Exp/Cntr=0.3,0.1

Type RM Length L Ch R = 1 ,78709.7 ,269,268.3,267.4
XS GIS Cut Line= 4
     1761065.019      305048.305      1761052.69      305386.372
     1761041.368      305541.101     1761156.165      305629.902
#Sta/Elev= 30
       0 1575.07    19.9 1563.93    31.8 1555.67    51.7 1544.04    79.6  1520.5
    91.5 1512.52   115.4 1494.37   123.4 1490.75   139.3 1489.31   151.2 1485.33
   171.1 1468.16   179.1 1463.74     195 1460.15   226.8 1455.71   286.6  1458.2
   322.4 1454.58   330.8  1451.7   338.3 1449.88   350.2 1450.88   362.2 1454.92
   374.1 1464.25     390 1480.46   405.9 1490.07   417.8 1499.88   445.7 1516.74
   469.6 1526.03   493.4  1529.8   520.9 1542.55   575.8 1564.73   638.6 1584.17
#Mann= 3 , 0 , 0
       0      .1       0   330.8    .045       0   350.2      .1       0
#XS Ineff= 2 , 0
          275.41 1466.48
Permanent Ineff=
       F       F
Bank Sta=330.8,350.2
XS Rating Curve= 0 ,0
Exp/Cntr=0.3,0.1

Type RM Length L Ch R = 1 ,78441.4 ,320.1,331.7,345.1
XS GIS Cut Line= 3
     1760787.242      305056.985     1760787.242      305343.444
     1760774.193      305762.076
#Sta/Elev= 30
       0 1558.59       8 1553.11    39.8 1526.38    99.5 1480.84   115.4 1466.28
   135.3 1453.86   155.2 1451.21     195 1451.54   206.9 1450.08   222.8  1450.8
   262.6 1449.41   284.6 1445.54   294.4 1445.31   299.6 1445.81   310.4 1449.32
   330.3 1449.83   334.3 1452.41   346.3 1466.07   370.2 1483.13   386.2 1485.32
   398.2 1491.66   410.1 1495.28   426.1 1506.44   577.6 1575.49   597.6  1579.5
   609.6 1586.79   621.5 1591.68   657.4 1604.46   681.4 1611.05   705.3  1621.8
#Mann= 3 , 0 , 0
       0      .1       0   284.6    .045       0   299.6      .1       0
#XS Ineff= 2 , 0
          190.84  1461.9
Permanent Ineff=
       F       F
Bank Sta=284.6,299.6
XS Rating Curve= 0 ,0
Exp/Cntr=0.3,0.1

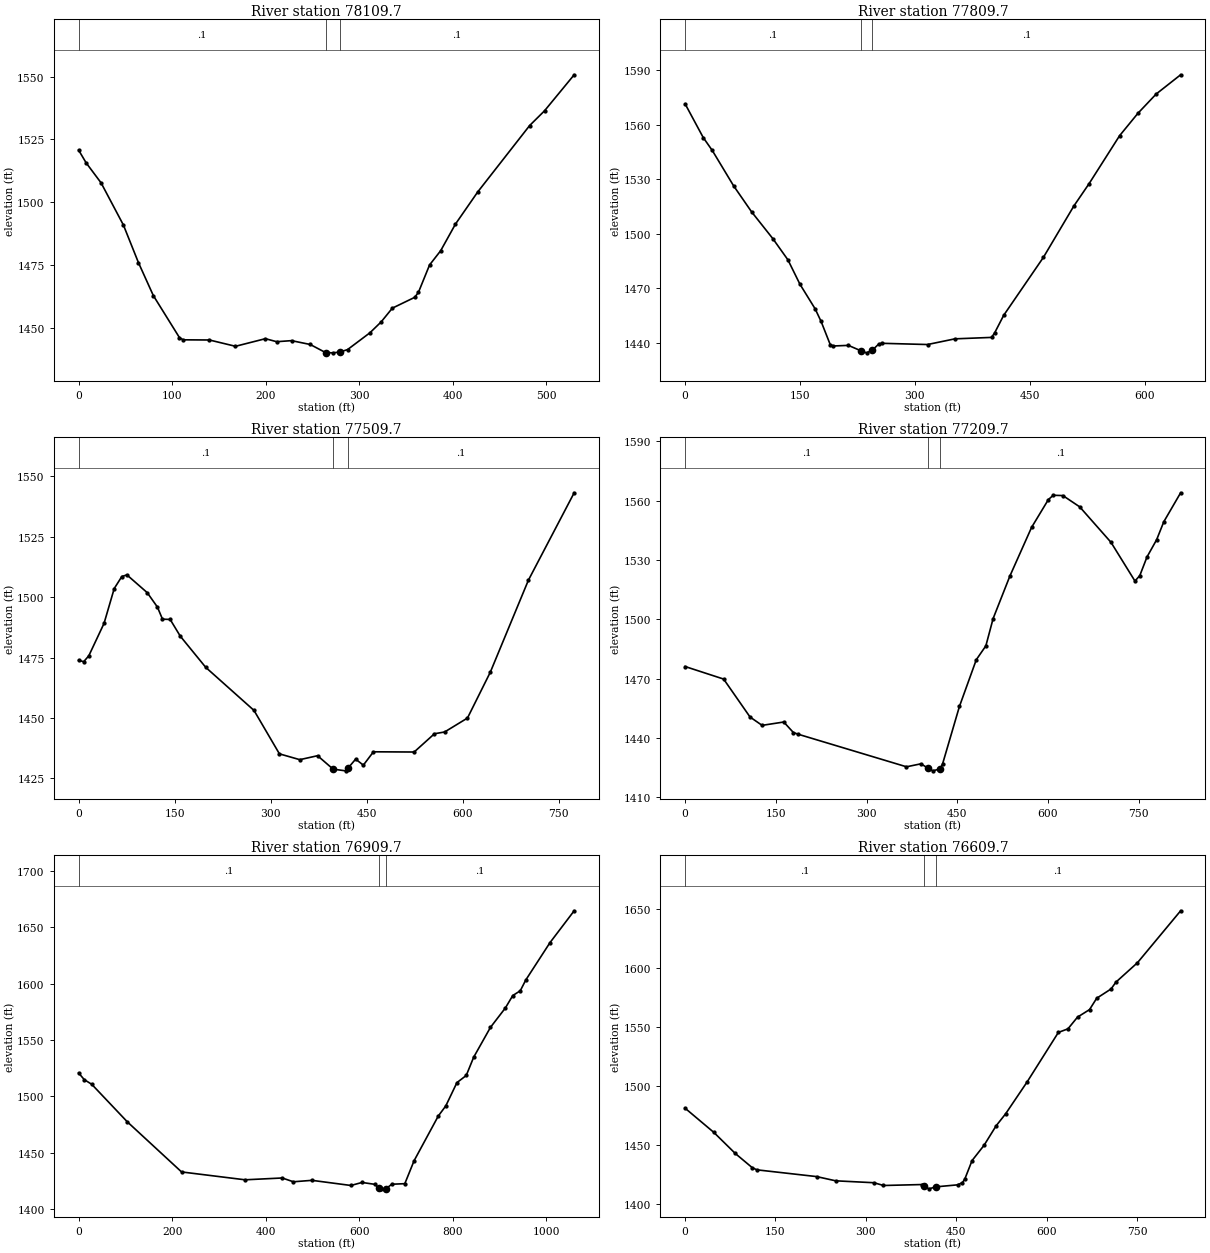
Type RM Length L Ch R = 1 ,78109.7 ,307.8,300,290.5
XS GIS Cut Line= 4
      1760613.63      305115.579     1760468.668      305345.238
     1760412.672      305422.796     1760394.446      305584.329
#Sta/Elev= 30
       0 1520.71       8 1515.65      24 1507.66    47.9 1490.83    63.9 1475.91
    79.9 1462.71   107.8 1445.98   111.8  1445.1   139.8 1445.03   167.7 1442.52
   199.7 1445.55   211.7 1444.35   227.6 1444.77   247.6 1443.24   264.1    1440
   271.6 1439.91   279.1 1440.21   287.5  1441.2   311.4 1447.89   323.4 1452.22
   335.4 1457.72   359.3 1462.03   363.3 1464.03   375.2 1474.94   387.1 1480.63
   402.9 1491.24   426.7 1504.05   482.2 1530.51   498.1 1536.38   529.8 1550.74
#Mann= 3 , 0 , 0
       0      .1       0   264.1    .045       0   279.1      .1       0
Bank Sta=264.1,279.1
XS Rating Curve= 0 ,0
Exp/Cntr=0.3,0.1

Type RM Length L Ch R = 1 ,77809.7 ,311.2,300,290.1
XS GIS Cut Line= 3
      1760290.28      305009.242     1760248.815      305242.457
     1760158.802      305642.547
#Sta/Elev= 30
       0 1571.42    23.7 1552.86    35.5 1545.77    63.2 1526.41    86.8 1512.02
   114.5  1497.3   134.2 1485.64     150 1472.15   169.8 1458.64   177.6 1451.69
   189.5 1438.97   193.4 1438.22   213.2 1438.55   229.4 1435.61   236.9 1434.45
   244.4  1435.9   252.8 1439.28   256.8  1439.7   316.5 1439.02   352.3 1442.15
   400.1 1442.94   404.1 1445.38     416 1455.11   467.8 1486.96   507.6 1515.24
   527.5 1527.54   567.3  1553.9   591.2 1566.21   615.1 1576.84     647 1587.41
#Mann= 3 , 0 , 0
       0      .1       0   229.4    .045       0   244.4      .1       0
Bank Sta=229.4,244.4
XS Rating Curve= 0 ,0
Exp/Cntr=0.3,0.1

Type RM Length L Ch R = 1 ,77509.7 ,299.2,300,297.5
XS GIS Cut Line= 3
     1759835.994      304802.361     1759960.155      305187.915
     1760034.203      305549.607
#Sta/Elev= 30
       0 1473.87     7.9 1473.29    15.9 1475.74    39.7 1489.15    55.6 1503.57
    67.5 1508.55    75.4 1509.22   107.2 1501.86   123.1  1495.9     131 1490.89
     143 1490.78   158.8 1483.86   198.6 1470.94     274 1453.12   313.7 1435.15
   345.5 1432.74   373.3 1434.38   397.6 1428.82     417 1428.12   420.9 1429.26
   432.8 1432.97   444.8 1430.47   460.6    1436   524.2 1435.91   555.9 1443.47
   571.8  1444.2   607.5 1449.97   643.2 1468.96   702.8 1507.09   774.2  1543.2
#Mann= 3 , 0 , 0
       0      .1       0   397.6    .045       0   420.9      .1       0
Bank Sta=397.6,420.9
XS Rating Curve= 0 ,0
Exp/Cntr=0.3,0.1

Type RM Length L Ch R = 1 ,77209.7 ,295.8,300,305.2
XS GIS Cut Line= 3
     1759570.141      304903.079     1759681.418      305297.481
     1759806.206      305687.449
#Sta/Elev= 30
       0 1476.16    63.7 1469.82   107.4 1450.63   127.3 1446.43   163.1 1448.12
     179 1442.81     187 1441.94     366 1425.49   389.9    1427   402.3 1424.64
   409.8 1423.45   421.7 1424.48   425.7 1426.99   453.5 1455.97   481.4 1479.61
   497.2  1486.6   509.2 1500.39     537 1521.93   572.8 1546.47   600.6 1560.54
   608.6 1562.69   624.5 1562.54   652.3 1556.85     704 1538.94   743.7 1519.34
   751.7 1522.12   763.6 1531.53   779.5 1540.22   791.4 1549.33   819.2 1563.95
#Mann= 3 , 0 , 0
       0      .1       0   402.3    .045       0   421.7      .1       0
Bank Sta=402.3,421.7
XS Rating Curve= 0 ,0
Exp/Cntr=0.3,0.1

Type RM Length L Ch R = 1 ,76909.7 ,298.6,300,299
XS GIS Cut Line= 4
     1759576.304      304761.846     1759356.342      305015.821
     1759383.795      305328.134     1759416.587      305736.561
#Sta/Elev= 30
       0 1520.79      12  1514.9      28 1510.75     104 1477.48     220 1433.03
   355.8 1426.05   435.2 1427.67     459  1424.3   498.7 1425.58     582 1421.02
   605.8  1423.7   633.6    1422     642  1418.5   645.5 1418.04     657  1418.2
   669.4 1422.13   697.2 1422.62   717.1 1443.03   768.8 1482.65   784.8 1491.59
   808.6 1512.23   828.5 1518.56   844.4 1534.77   880.2 1561.19   912.1 1578.41
     928 1589.48   943.9 1593.62   955.8 1603.27  1007.5 1636.37  1059.2 1664.62
#Mann= 3 , 0 , 0
       0      .1       0     642    .045       0     657      .1       0
Bank Sta=642,657
XS Rating Curve= 0 ,0
Exp/Cntr=0.3,0.1

Type RM Length L Ch R = 1 ,76609.7 ,310.8,300,293.4
XS GIS Cut Line= 3
     1759074.433      304941.698     1759084.925      305350.106
     1759135.311      305760.745
#Sta/Elev= 30
       0 1481.08    47.6 1460.66    83.3 1442.77   111.1  1430.9     119 1428.94
   218.2 1423.22   249.9 1419.64   313.4 1418.02   329.2 1415.68   392.7 1416.48
   396.6 1415.25   404.6 1412.85     416 1414.53   452.3 1416.24   460.3 1418.16
   464.2  1421.2   476.2 1436.78   496.1  1449.7     516  1466.1   531.9 1476.37
   567.7 1503.44   619.4 1545.22   635.3 1548.25   651.2 1558.18   671.1 1564.52
     683 1574.13   706.9 1582.02   714.8 1587.72   750.7 1604.23   822.3 1648.16
#Mann= 3 , 0 , 0
       0      .1       0   396.6    .045       0     416      .1       0
Bank Sta=396.6,416
XS Rating Curve= 0 ,0
Exp/Cntr=0.3,0.1

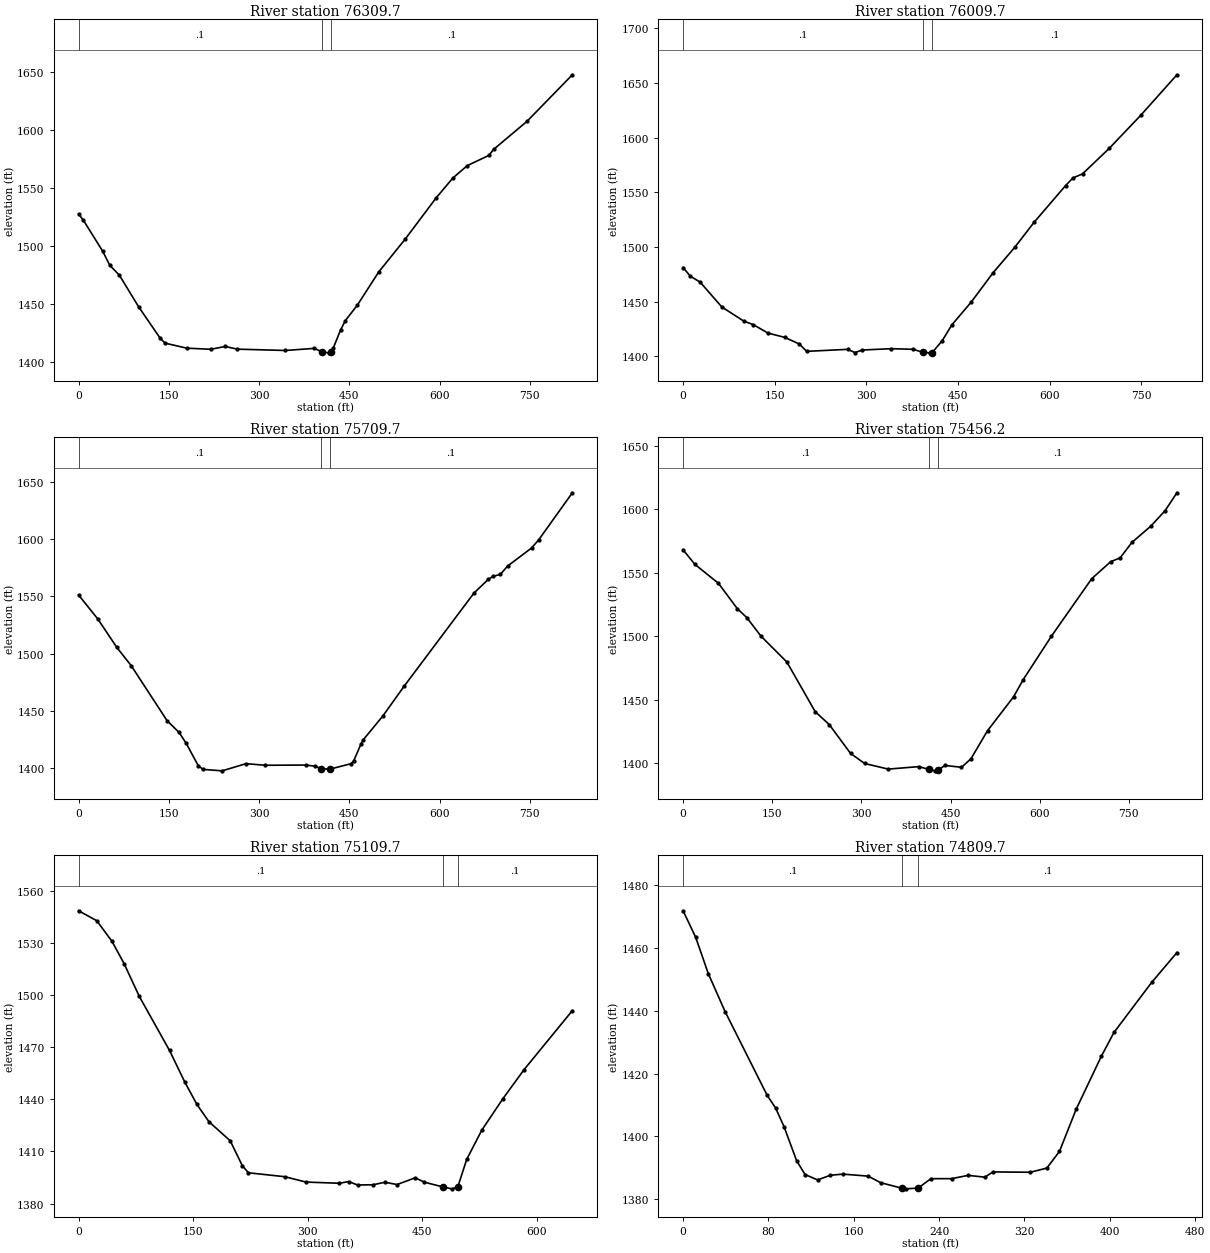
Type RM Length L Ch R = 1 ,76309.7 ,299.7,300,298.8
XS GIS Cut Line= 3
     1758612.247      305098.519     1758811.678      305458.711
       1758974.8      305833.892
#Sta/Elev= 30
       0  1527.7       8 1522.35      40 1495.74      52 1483.46      68 1474.82
    99.9 1447.67   135.9 1420.44   143.9 1416.37   179.9 1412.02   219.8  1411.1
   243.8 1413.48   263.8 1411.19   343.8 1410.05   391.7 1411.86   404.2 1408.99
   415.7 1408.01   419.2 1408.72   423.6 1412.37   435.6  1427.8   443.5 1435.82
   463.4 1449.13   499.1 1477.84   542.8 1505.96   594.4  1541.6   622.2 1558.71
   646.1 1569.39   681.8 1578.15   689.8 1583.34   745.4 1607.58   820.8 1647.72
#Mann= 3 , 0 , 0
       0      .1       0   404.2    .045       0   419.2      .1       0
Bank Sta=404.2,419.2
XS Rating Curve= 0 ,0
Exp/Cntr=0.3,0.1

Type RM Length L Ch R = 1 ,76009.7 ,298.2,300,300.2
XS GIS Cut Line= 3
     1758369.707      305267.489     1758562.385      305618.406
      1758748.43      305981.631
#Sta/Elev= 30
       0 1481.14    11.9 1473.14    27.8  1467.8    63.4    1445    99.1 1432.17
     115 1428.81   138.7 1421.18   166.5 1417.16   190.3 1411.12   202.2  1404.4
   269.5 1406.24   281.4 1403.28   293.3 1405.63   340.9 1406.84   376.6 1406.28
   392.8 1403.46   404.3 1403.04   407.8 1403.33   424.1 1414.06     440 1428.66
   471.6 1449.44   507.3 1476.23     543 1499.68   574.7  1522.6   626.2 1556.14
   638.1 1563.06   653.9 1566.84   697.5 1590.13     749 1620.33   808.4 1657.53
#Mann= 3 , 0 , 0
       0      .1       0   392.8    .045       0   407.8      .1       0
Bank Sta=392.8,407.8
XS Rating Curve= 0 ,0
Exp/Cntr=0.3,0.1

Type RM Length L Ch R = 1 ,75709.7 ,253.1,253.5,250.9
XS GIS Cut Line= 3
     1758127.683      305373.809     1758295.098       305747.59
     1758478.671      306115.287
#Sta/Elev= 30
       0 1551.31    31.8 1530.41    63.6 1505.35    87.5 1489.36   147.1 1441.18
     167 1430.89   178.9 1421.32   198.8 1401.82   206.8 1398.49   238.6 1397.22
   278.3  1403.5   310.2 1402.11   377.8 1402.28   393.7  1401.2   402.1 1399.26
   417.1 1398.62   453.4 1403.58   457.4 1406.19   469.4 1420.87   473.4 1424.65
   505.3 1445.03   541.2 1471.51   656.9 1552.88   680.9 1565.04   688.9 1567.59
   700.8 1569.29   712.8 1576.56   752.7 1592.43   764.7 1599.67   820.5 1640.81
#Mann= 3 , 0 , 0
       0      .1       0   402.1    .045       0   417.1      .1       0
Bank Sta=402.1,417.1
XS Rating Curve= 0 ,0
Exp/Cntr=0.3,0.1

Type RM Length L Ch R = 1 ,75456.2 ,347.1,346.5,349.4
XS GIS Cut Line= 3
     1757920.623      305493.811     1758083.249      305881.638
     1758301.601      306229.126
#Sta/Elev= 30
       0 1567.92    19.8 1556.52    59.5 1541.58    91.2 1521.62   107.1 1514.62
   130.9 1500.04   174.6 1479.58   222.2 1440.54     246 1430.28   281.7 1407.65
   305.5 1399.68   345.2 1395.27   396.7 1397.23   413.5 1395.03   424.5  1393.9
   428.5 1394.23   440.5 1398.17   468.4 1396.68   484.3 1403.36   512.2  1425.5
     556 1452.14     572 1465.54   619.8 1499.98   687.5 1545.18   719.4  1558.6
   735.3 1561.58   755.2 1573.77   787.1 1586.66     811 1598.75   830.9 1612.87
#Mann= 3 , 0 , 0
       0      .1       0   413.5    .045       0   428.5      .1       0
Bank Sta=413.5,428.5
XS Rating Curve= 0 ,0
Exp/Cntr=0.3,0.1

Type RM Length L Ch R = 1 ,75109.7 ,294.7,300,306.8
XS GIS Cut Line= 4
     1757633.955      305710.408     1757878.758      306128.434
     1757901.715      306169.846     1757994.273      306237.541
#Sta/Elev= 30
       0 1548.82    23.8 1543.12    43.7 1531.24    59.6 1518.37    79.4 1499.55
   119.1 1468.25     139 1450.11   154.9 1437.17   170.7 1427.17   198.5  1416.2
   214.4 1401.79   222.4 1397.72     270 1395.45   297.8 1392.36   341.5 1391.68
   353.4 1392.64   365.3 1390.69   385.2 1390.78     401 1392.25   416.9 1390.94
   440.8 1394.82   452.7 1392.29   476.9 1389.57   488.4 1388.46   496.3 1389.38
   508.1 1405.44   527.8 1422.26   555.5 1440.46   583.2 1457.21   646.4 1491.26
#Mann= 3 , 0 , 0
       0      .1       0   476.9    .045       0   496.3      .1       0
Bank Sta=476.9,496.3
XS Rating Curve= 0 ,0
Exp/Cntr=0.3,0.1

Type RM Length L Ch R = 1 ,74809.7 ,306.3,300,289.6
XS GIS Cut Line= 4
     1757521.183      305931.551     1757583.149       306135.17
     1757608.284      306264.854     1757673.092      306363.409
#Sta/Elev= 30
       0 1471.82    11.8 1463.37    23.6 1451.82    39.4 1439.69    78.8 1413.06
    86.7 1409.03    94.6 1403.11   106.4 1392.25   114.3 1387.85   126.1 1386.13
     138 1387.61   149.8 1387.98   173.4 1387.34   185.2 1385.25   205.3 1383.47
   208.9 1383.29   220.3 1383.54   232.3 1386.52   251.7 1386.53   267.2 1387.58
   282.8 1387.01   290.5 1388.68   325.5 1388.57     341  1389.9   352.8 1395.21
   368.5 1408.67   392.1 1425.53   403.9 1433.09   439.3 1449.04   462.9  1458.5
#Mann= 3 , 0 , 0
       0      .1       0   205.3    .045       0   220.3      .1       0
Bank Sta=205.3,220.3
XS Rating Curve= 0 ,0
Exp/Cntr=0.3,0.1