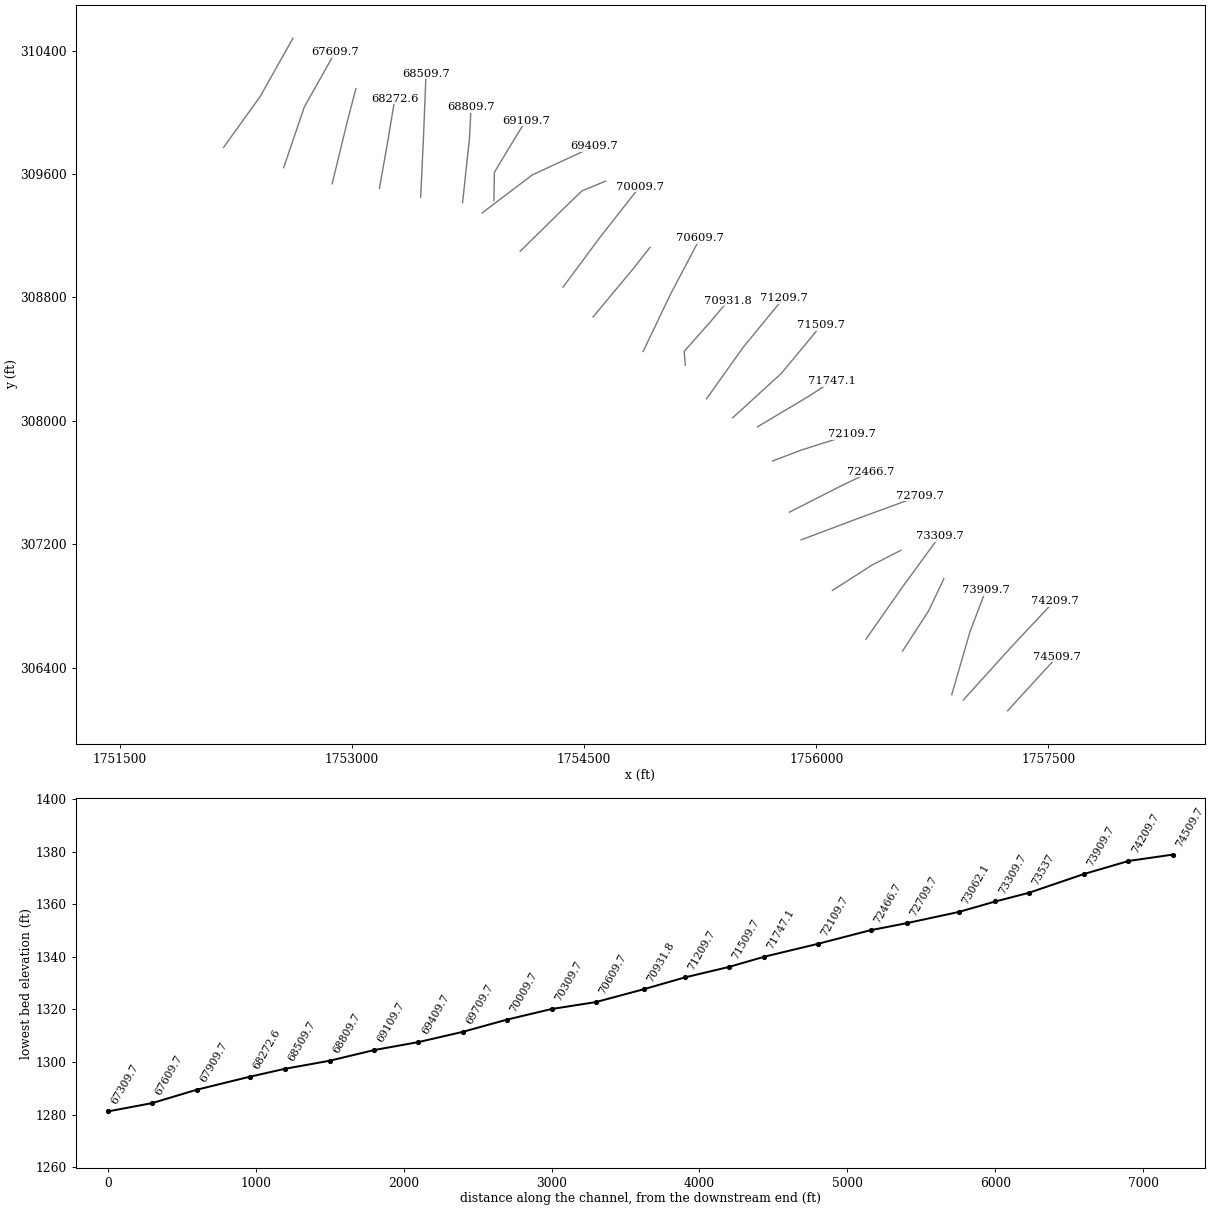
HEC-RAS study SPLAURFK.prj: SPLAURFK

--- SPLAURFK.g01 (geometry) --- (continued)

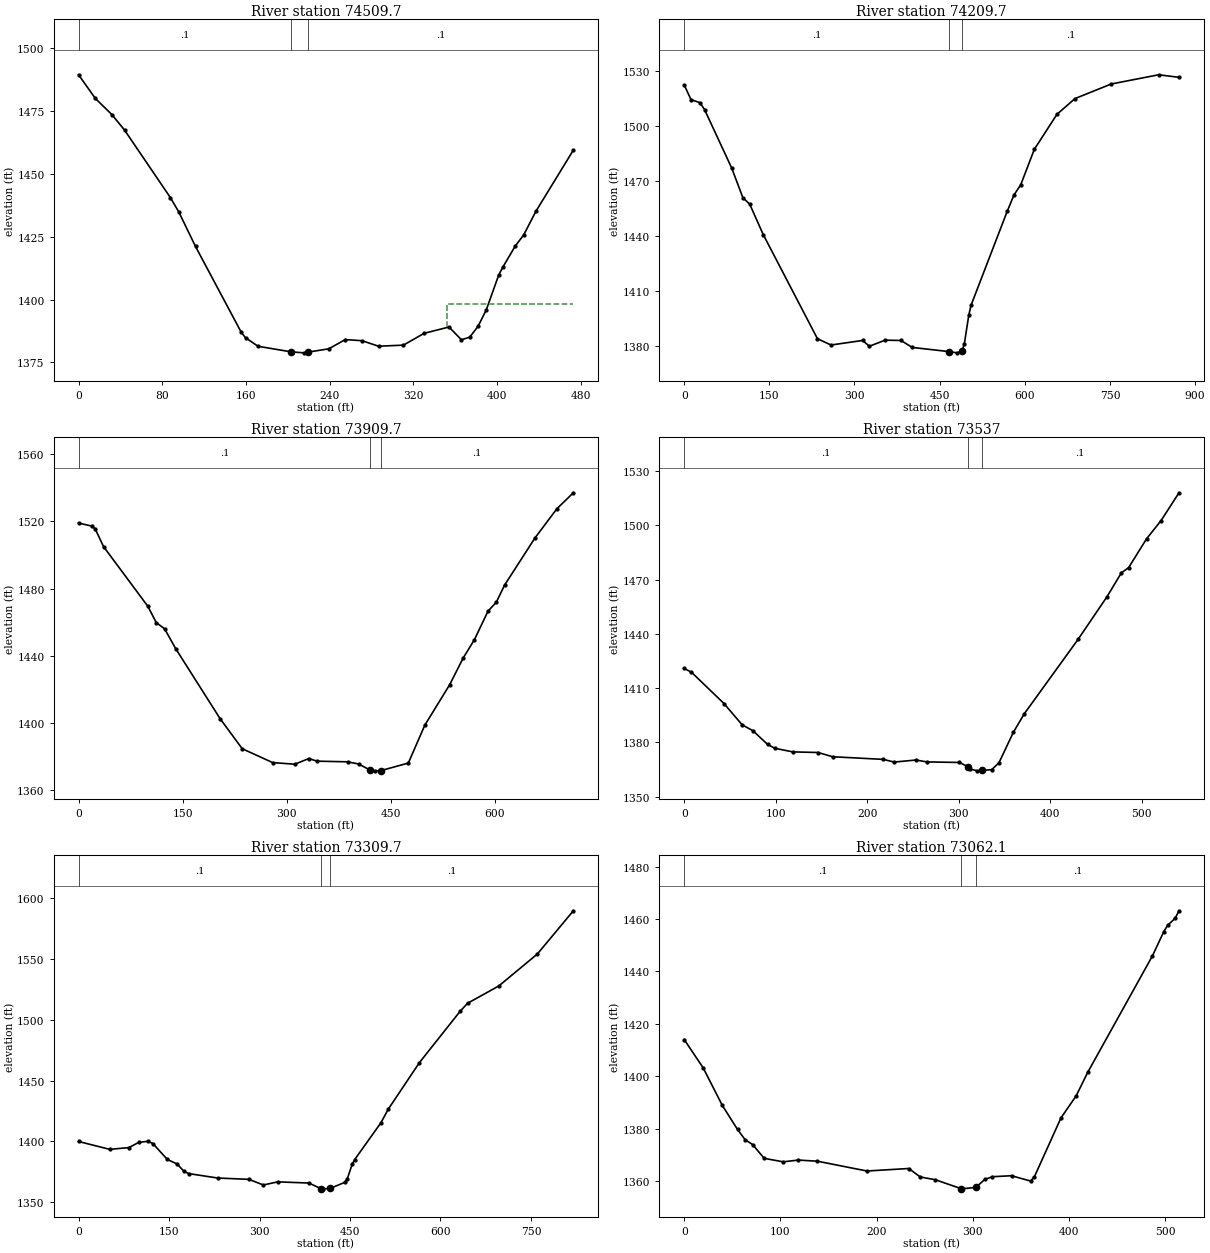
Type RM Length L Ch R = 1 ,74509.7 ,303.8,300,298
XS GIS Cut Line= 3
     1757236.894      306120.353     1757376.834      306273.605
     1757555.905      306469.746
#Sta/Elev= 30
       0 1489.42      16 1480.02    31.9 1473.55    43.9 1467.45    87.8 1440.55
    95.8 1434.88   111.8 1421.13   155.6 1386.95   159.6 1384.84   171.6 1381.44
   203.5  1379.2   215.5 1378.83   219.4 1379.11   239.2 1380.43   255.1 1384.11
     271 1383.65   286.8 1381.47   310.6 1381.89   330.4  1386.6   354.2  1389.1
   366.1 1384.02     374 1385.06     382 1389.39   389.9 1395.99   401.8 1409.85
   405.7 1412.94   417.6 1421.35   425.6 1425.71   437.4  1435.2   473.1 1459.46
#Mann= 3 , 0 , 0
       0      .1       0   203.5    .045       0   219.4      .1       0
#XS Ineff= 2 , 0
                          352.46         1398.17
Permanent Ineff=
       F       F
Bank Sta=203.5,219.4
XS Rating Curve= 0 ,0
Exp/Cntr=0.3,0.1

Type RM Length L Ch R = 1 ,74209.7 ,289.7,300,308.8
XS GIS Cut Line= 3
     1756950.518      306189.767     1757267.642      306541.305
     1757539.821      306831.908
#Sta/Elev= 30
       0  1522.3    11.9 1514.34    27.8 1512.62    35.8 1508.92    83.6  1477.1
   103.4 1460.85   115.4 1457.38   139.2 1440.82   234.7  1384.1   258.6 1380.66
   314.3 1383.15   326.2    1380   354.1 1383.31   381.9 1383.13   401.8 1379.34
   465.9  1377.1   480.9  1376.4   489.4 1377.36   493.4  1381.1   501.3 1396.83
   505.3  1402.3     569 1453.46   580.9 1462.35   592.9 1467.97   616.8 1487.23
   656.6 1506.29   688.4 1514.87   752.2 1522.81   835.8 1527.84   871.6 1526.46
#Mann= 3 , 0 , 0
       0      .1       0   465.9    .045       0   489.4      .1       0
Bank Sta=465.9,489.4
XS Rating Curve= 0 ,0
Exp/Cntr=0.3,0.1

Type RM Length L Ch R = 1 ,73909.7 ,379.2,372.6,370.2
XS GIS Cut Line= 3
     1756875.363      306223.661     1756994.331      306634.701
     1757095.835      306901.603
#Sta/Elev= 30
       0 1518.99      20  1517.1      24 1515.45      36 1504.96     100 1469.35
     112 1459.72     124 1456.04     140 1444.23     204 1402.55     236 1384.62
   279.9 1376.37   311.9  1375.4   331.9 1378.78   343.9 1377.22   387.9 1376.83
   403.9 1375.52   420.4 1371.91   427.9 1371.46   435.4 1371.55   475.5 1376.07
   499.3 1398.66     535 1422.65   554.8 1438.78   570.7 1449.46   590.5  1466.6
   602.4 1471.85   614.3 1482.02   657.9 1509.98   689.7 1527.49   713.5 1537.02
#Mann= 3 , 0 , 0
       0      .1       0   420.4    .045       0   435.4      .1       0
Bank Sta=420.4,435.4
XS Rating Curve= 0 ,0
Exp/Cntr=0.3,0.1

Type RM Length L Ch R = 1 ,73537   ,228.8,227.4,222.9
XS GIS Cut Line= 3
     1756557.641      306506.638     1756726.912      306769.225
     1756824.568      306975.388
#Sta/Elev= 30
       0 1420.87     7.9 1418.83    43.5 1401.49    63.3 1389.75    75.1 1386.48
      91 1378.96    98.9  1376.8   118.6 1374.79   146.3 1374.45   162.1 1372.11
   217.5 1370.65   229.4 1369.16   253.1  1370.3     265 1369.26   300.6 1368.94
   309.8 1366.69   312.4 1365.32   320.3 1364.32   324.8 1364.54     336 1364.99
   343.9 1368.81   359.6 1385.63   371.4 1395.76   430.4 1437.06   461.9 1460.54
   477.6 1473.72   485.5  1476.6   505.1 1492.54   520.9 1502.56   540.5 1517.96
#Mann= 3 , 0 , 0
       0      .1       0   309.8    .045       0   324.8      .1       0
Bank Sta=309.8,324.8
XS Rating Curve= 0 ,0
Exp/Cntr=0.3,0.1

Type RM Length L Ch R = 1 ,73309.7 ,257,247.5,235.7
XS GIS Cut Line= 3
     1756320.995      306583.891     1756555.527      306919.859
     1756796.998      307251.873
#Sta/Elev= 30
       0 1399.96    51.7 1393.49    83.5 1394.95    99.4 1399.16   115.4 1400.17
   123.3 1398.19   147.2 1385.15   163.1 1381.54     175 1375.29     183 1373.52
   230.7  1369.9   282.4 1368.83   306.3 1364.18   330.2 1366.75   381.9 1365.78
   402.2 1361.04   405.8 1361.01   417.2 1361.38   441.6  1366.4   445.6 1369.41
   453.6 1381.22   457.6 1384.98   501.4 1415.48   513.4 1426.54   565.2 1464.95
   632.9 1507.29   644.9 1513.67   696.7 1527.93   760.5 1554.16   820.3 1589.79
#Mann= 3 , 0 , 0
       0      .1       0   402.2    .045       0   417.2      .1       0
Bank Sta=402.2,417.2
XS Rating Curve= 0 ,0
Exp/Cntr=0.3,0.1

Type RM Length L Ch R = 1 ,73062.1 ,357.3,352.5,349.9
XS GIS Cut Line= 3
     1756104.082      306899.433     1756360.158      307064.364
      1756546.79       307159.85
#Sta/Elev= 30
       0 1414.02    19.8 1403.16    39.6 1388.88    55.4  1379.7    63.3  1375.8
    71.2  1373.9    83.1 1368.68   102.8 1367.34   118.7 1368.01   138.4 1367.58
   189.9 1363.84   233.4 1364.79   245.3 1361.57   261.1 1360.49   288.1 1357.06
   288.8 1357.03   303.1  1357.6   312.5 1360.63   320.4 1361.67   340.2 1362.03
     360    1360   363.9  1361.6   391.6 1384.13   407.4 1392.56   419.3 1401.46
   486.6 1445.95   498.4  1455.2   502.4 1457.62   510.3 1460.34   514.2 1463.18
#Mann= 3 , 0 , 0
       0      .1       0   288.1    .045       0   303.1      .1       0
Bank Sta=288.1,303.1
XS Rating Curve= 0 ,0
Exp/Cntr=0.3,0.1

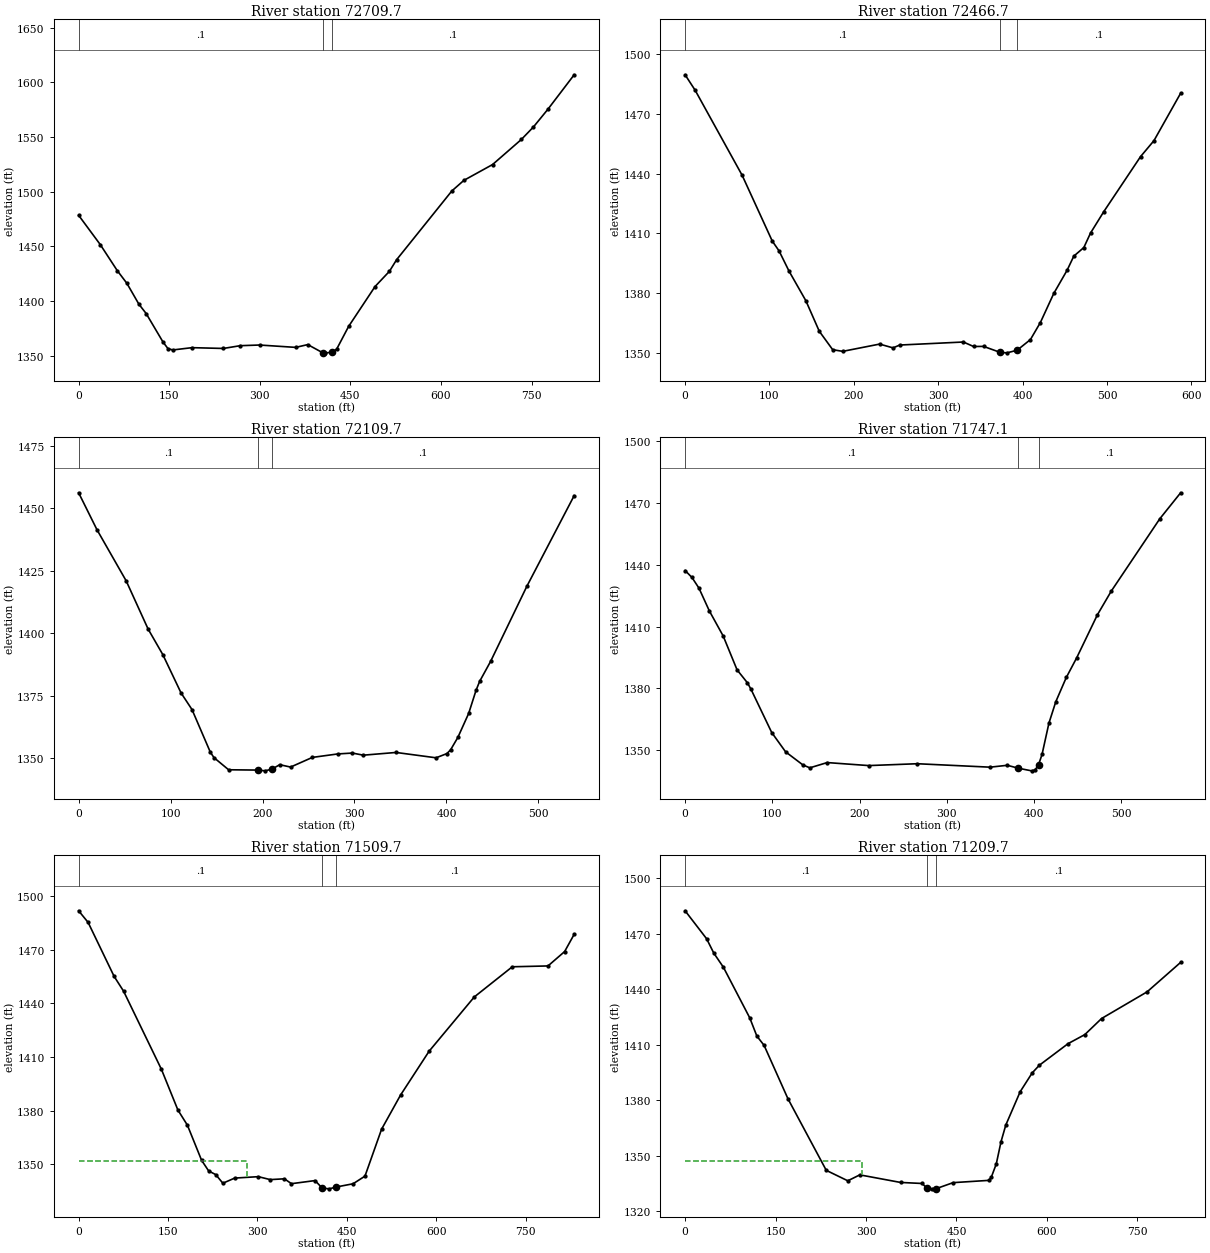
Type RM Length L Ch R = 1 ,72709.7 ,240.4,243,245.1
XS GIS Cut Line= 3
     1755901.771      307227.628     1756286.624      307372.792
     1756670.856      307513.478
#Sta/Elev= 30
       0 1478.47    35.9 1451.64    63.9 1427.97    79.9  1416.3    99.8 1397.21
   111.8  1388.7   139.8 1362.56   147.8 1356.71   155.7 1355.38   187.7 1357.49
   239.6 1356.77   267.6  1359.3   299.5  1359.9   359.4 1357.75   379.4 1360.29
   403.8 1352.94   407.3 1352.76   418.8 1353.12   427.2  1356.1   447.1 1376.97
   490.8 1413.36   514.6 1427.27   526.5 1437.88   617.9 1500.68   637.8 1510.37
   685.4 1524.86   733.1  1547.8     753 1559.17   776.8 1575.25   820.5  1606.9
#Mann= 3 , 0 , 0
       0      .1       0   403.8    .045       0   418.8      .1       0
Bank Sta=403.8,418.8
XS Rating Curve= 0 ,0
Exp/Cntr=0.3,0.1

Type RM Length L Ch R = 1 ,72466.7 ,359.3,357,354.3
XS GIS Cut Line= 3
     1755826.304      307407.246     1756162.676      307578.687
     1756351.478      307669.833
#Sta/Elev= 30
       0 1489.59    11.9 1481.84    67.6 1439.17   103.3 1406.17   111.3 1401.28
   123.2 1391.07   143.1 1376.26     159 1360.94   174.9 1351.68   186.8 1350.86
   230.5  1354.5   246.4  1352.6   254.3 1354.02   329.8 1355.54   341.8 1353.29
   353.7 1353.34   373.6  1350.3   381.5 1350.11   393.4 1351.41   409.2 1356.76
     421 1365.32   436.9 1379.93   452.7 1391.57   460.6 1398.62   472.5 1402.93
   480.4 1410.18   496.2 1420.98   539.7 1448.54   555.6 1456.56   587.2 1480.33
#Mann= 3 , 0 , 0
       0      .1       0   373.6    .045       0   393.4      .1       0
Bank Sta=373.6,393.4
XS Rating Curve= 0 ,0
Exp/Cntr=0.3,0.1

Type RM Length L Ch R = 1 ,72109.7 ,358.7,362.6,368.2
XS GIS Cut Line= 3
     1755717.797      307739.277     1755907.476      307811.152
      1756227.78      307912.888
#Sta/Elev= 30
       0 1456.24    19.9 1441.48    51.7 1420.98    75.6 1401.65    91.5 1391.48
   111.4 1376.09   123.3 1369.44   143.2  1352.4   147.2 1350.19   163.1 1345.34
   195.3 1345.21   202.8 1344.91   210.3 1345.61   218.7 1347.37   230.5 1346.42
   254.2 1350.29   281.9 1351.68   297.7 1352.03   309.6 1351.18   345.2 1352.27
   388.7 1350.13   400.5 1351.82   404.5 1353.32   412.4 1358.28   424.2 1367.93
   432.2 1377.16   436.1 1380.73     448 1388.71   487.5 1418.84   538.9  1455.1
#Mann= 3 , 0 , 0
       0      .1       0   195.3    .045       0   210.3      .1       0
Bank Sta=195.3,210.3
XS Rating Curve= 0 ,0
Exp/Cntr=0.3,0.1

Type RM Length L Ch R = 1 ,71747.1 ,232.8,237.4,244.1
XS GIS Cut Line= 3
     1755620.141      307960.631     1755954.342      308160.284
     1756104.082       308257.94
#Sta/Elev= 30
       0 1437.19     7.9 1433.81    15.9 1428.64    27.8  1417.6    43.7  1405.4
    59.6 1388.99    71.5 1382.69    75.5 1379.63    99.3  1358.6   115.2 1349.24
   135.1 1342.86     143 1341.47   162.9 1344.02   210.5 1342.56   266.2 1343.46
   349.6 1341.79   369.4  1342.7   381.9  1341.3   397.2 1340.01   401.2 1340.41
   405.2 1342.96   409.2 1347.96   417.1 1363.15     425 1373.57     437  1385.3
   448.9 1394.82   472.7 1415.73   488.6 1427.22   544.2 1462.29   568.1 1474.91
#Mann= 3 , 0 , 0
       0      .1       0   381.9    .045       0   405.2      .1       0
Bank Sta=381.9,405.2
XS Rating Curve= 0 ,0
Exp/Cntr=0.3,0.1

Type RM Length L Ch R = 1 ,71509.7 ,295.2,300,300.1
XS GIS Cut Line= 3
     1755459.843      308019.258     1755773.176      308305.663
     1756032.631      308619.051
#Sta/Elev= 30
       0 1491.92    15.9 1485.41    59.5 1455.19    75.4 1446.89   138.9 1403.11
   166.6 1380.27   182.5  1371.8   206.3 1352.14   218.2 1346.16   230.1 1344.11
     242 1339.29   261.8 1342.17   301.5 1342.97   321.4 1341.32   345.2 1341.77
   357.1 1339.04   396.7 1340.78   408.6 1336.58   420.5 1336.15     432 1337.17
   460.4 1338.98   480.4 1343.26   508.3 1369.57   540.2 1388.73     588 1413.24
   663.8 1443.64   727.6 1460.55   787.5 1461.02   815.4 1469.08   831.4 1478.74
#Mann= 3 , 0 , 0
       0      .1       0   408.6    .045       0     432      .1       0
#XS Ineff= 2 , 0
          282.08 1351.93
Permanent Ineff=
       F       F
Bank Sta=408.6,432
XS Rating Curve= 0 ,0
Exp/Cntr=0.3,0.1

Type RM Length L Ch R = 1 ,71209.7 ,279.6,277.8,278.2
XS GIS Cut Line= 3
      1755290.75      308142.333     1755527.438      308475.584
     1755788.784      308795.271
#Sta/Elev= 30
       0 1482.34    35.7 1467.22    47.6 1459.46    63.5 1451.85   107.2  1424.5
     119 1414.65     131 1409.64   170.6 1380.77   234.1 1342.13   269.8 1336.48
   289.7 1339.69   357.2  1335.6   392.9 1335.04   401.2 1332.48   408.8 1332.14
   416.2 1332.23   444.5 1335.49     504 1336.72     508 1338.64     516 1345.59
   523.9 1357.65   531.8 1366.61   555.6 1384.58   575.5 1394.74   587.4  1398.9
   635.1 1410.58   662.8 1415.45   690.6 1424.14   766.1 1438.55   821.7 1454.46
#Mann= 3 , 0 , 0
       0      .1       0   401.2    .045       0   416.2      .1       0
#XS Ineff= 2 , 0
          293.39 1347.43
Permanent Ineff=
       F       F
Bank Sta=401.2,416.2
XS Rating Curve= 0 ,0
Exp/Cntr=0.3,0.1

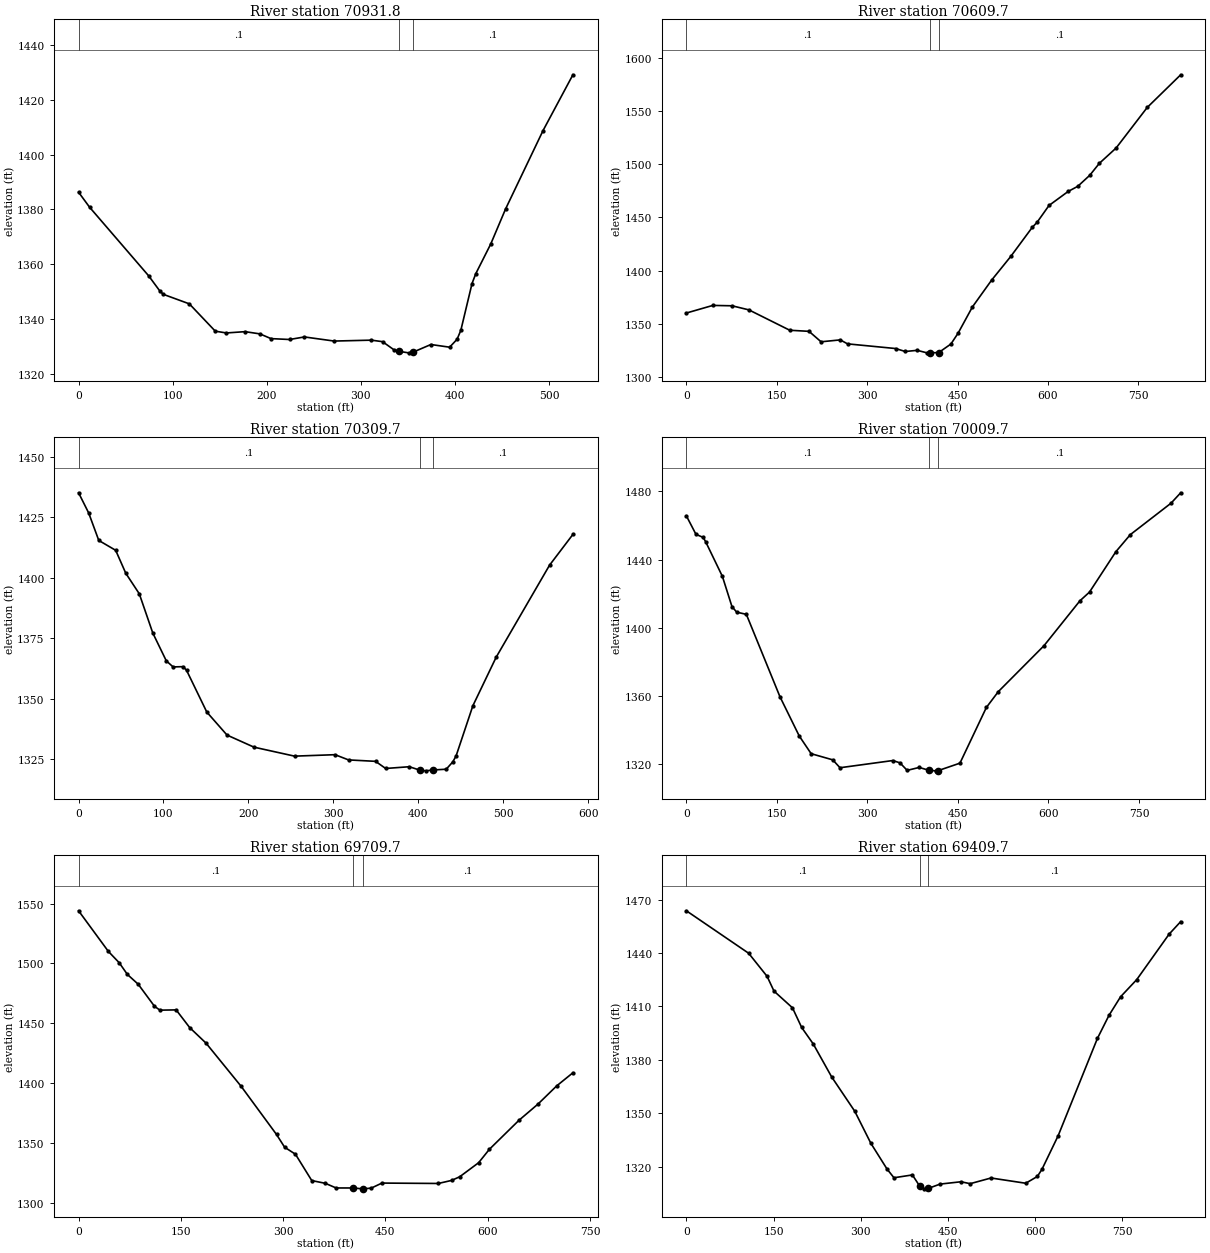
Type RM Length L Ch R = 1 ,70931.8 ,316.2,322.2,326.6
XS GIS Cut Line= 4
     1755153.561      308359.937     1755146.474      308449.676
     1755316.321      308642.055     1755431.339      308778.774
#Sta/Elev= 30
       0 1386.28    11.7  1380.8    74.4 1355.79    86.1 1350.34      90 1349.01
   117.7 1345.53   145.3 1335.55   157.1 1334.91   176.9 1335.38   192.7 1334.57
   204.5 1332.84   224.2 1332.52     240 1333.45   271.6 1331.95   311.1 1332.28
     323 1331.73   334.8 1328.84   340.8 1328.18   350.6 1327.65   355.8 1327.95
   374.4 1330.69   394.3 1329.71   402.2 1332.59   406.2 1335.86   418.1 1352.95
   422.1 1356.55     438 1367.38   453.8  1380.2   493.6  1408.8   525.3 1429.14
#Mann= 3 , 0 , 0
       0      .1       0   340.8    .045       0   355.8      .1       0
Bank Sta=340.8,355.8
XS Rating Curve= 0 ,0
Exp/Cntr=0.3,0.1

Type RM Length L Ch R = 1 ,70609.7 ,306,300,295.4
XS GIS Cut Line= 3
     1754880.927      308448.473      1755057.67      308819.603
      1755248.17      309181.694
#Sta/Elev= 30
       0 1360.16    43.9 1367.32    75.8 1366.96   103.8 1363.12   171.6 1343.99
   203.5 1342.98   223.5 1333.16   255.4 1334.95   267.4 1331.22   347.2 1326.83
   363.2 1324.05   383.1 1325.14   399.1 1322.79   403.6 1322.81   418.6 1323.01
   438.9 1331.05   450.8 1341.18   474.6 1365.88   506.4    1391   538.2 1413.27
   573.9  1440.6   581.9 1445.34   601.7 1461.15   633.5 1474.32   649.4 1479.12
   669.3 1489.48   685.2 1500.71     713 1515.08   764.6 1553.14   820.2 1583.86
#Mann= 3 , 0 , 0
       0      .1       0   403.6    .045       0   418.6      .1       0
Bank Sta=403.6,418.6
XS Rating Curve= 0 ,0
Exp/Cntr=0.3,0.1

Type RM Length L Ch R = 1 ,70309.7 ,298.8,300,299.8
XS GIS Cut Line= 3
     1754557.534      308673.014     1754819.089      308987.836
     1754925.696      309123.826
#Sta/Elev= 30
       0 1435.18    11.9 1426.83    23.8 1415.46    43.7 1411.38    55.6 1401.88
    71.5 1393.39    87.4 1377.17   103.3 1365.65   111.3 1363.14   123.2 1363.25
   127.2 1361.71     151 1344.46   174.8 1334.95   206.6 1329.94   254.3 1326.23
     302 1326.83   317.9 1324.67   349.7 1324.08   361.6 1321.13   389.4 1321.85
   401.8 1320.45   409.3 1320.15   416.8  1320.5   432.9 1320.82   440.7 1323.87
   444.6 1326.37   464.3 1347.07   491.8  1367.2   554.6 1405.23   582.1 1417.95
#Mann= 3 , 0 , 0
       0      .1       0   401.8    .045       0   416.8      .1       0
Bank Sta=401.8,416.8
XS Rating Curve= 0 ,0
Exp/Cntr=0.3,0.1

Type RM Length L Ch R = 1 ,70009.7 ,303.4,300,296.8
XS GIS Cut Line= 3
     1754363.305      308866.161     1754607.109       309195.41
     1754859.764      309517.633
#Sta/Elev= 30
       0 1465.66    15.9 1454.82    27.8 1453.02    31.8  1450.6    59.7 1430.17
    75.6  1412.4    83.5 1409.16    99.4 1407.91   155.1 1359.59     187 1336.61
   206.8 1326.19   242.6 1322.58   254.6 1317.96   342.1 1322.18     354 1320.82
   365.9 1316.42   385.8 1318.13   402.2 1316.45   413.7 1316.14   417.2 1316.26
   453.4 1320.65   497.2 1353.32     517  1362.6   592.6 1389.49   652.2 1415.84
   668.1 1420.96   711.8 1444.65   735.7 1454.63   803.2 1473.08   819.2 1479.18
#Mann= 3 , 0 , 0
       0      .1       0   402.2    .045       0   417.2      .1       0
Bank Sta=402.2,417.2
XS Rating Curve= 0 ,0
Exp/Cntr=0.3,0.1

Type RM Length L Ch R = 1 ,69709.7 ,302.8,300,292.4
XS GIS Cut Line= 4
     1754086.624      309098.646     1754378.164      309386.272
     1754485.915      309489.879     1754639.238      309553.513
#Sta/Elev= 30
       0 1543.95    43.7 1509.98    59.6  1500.5    71.6 1490.73    87.5 1482.52
   111.3 1464.13   119.3 1460.87   143.1 1461.09     163 1446.27   186.9 1433.32
   238.6 1397.06   290.3 1356.93   302.2 1346.27   318.1  1340.4     342 1318.39
   361.8 1316.11   377.7 1312.21     402 1312.21     417 1311.48   429.2 1312.07
   444.9  1316.3   527.6 1315.97   547.2 1318.54     559 1321.59   586.7 1333.31
   602.5 1344.53     646 1368.85   673.6 1382.24   701.3 1397.59     725 1408.52
#Mann= 3 , 0 , 0
       0      .1       0     402    .045       0     417      .1       0
Bank Sta=402,417
XS Rating Curve= 0 ,0
Exp/Cntr=0.3,0.1

Type RM Length L Ch R = 1 ,69409.7 ,291,300,313.5
XS GIS Cut Line= 3
     1753840.319      309346.907     1754165.627      309594.104
     1754566.152      309779.897
#Sta/Elev= 30
       0  1463.7   107.1 1439.86   138.8  1426.9   150.7  1418.6   182.5  1409.2
   198.3 1398.18   218.2 1388.93   249.9  1370.4   289.6 1351.14   317.3 1333.14
   345.1 1318.69     357  1313.8   388.7 1315.39   401.1 1309.19   408.6 1307.58
   416.1 1307.84   436.4 1310.25   472.2 1311.55   488.1 1310.48   523.9 1313.67
   583.6 1310.72   603.5 1314.51   611.4 1318.46   639.3 1337.35   706.9 1392.05
   726.8    1405   746.7 1415.41   774.5 1425.05   830.2 1450.59   850.1 1457.62
#Mann= 3 , 0 , 0
       0      .1       0   401.1    .045       0   416.1      .1       0
Bank Sta=401.1,416.1
XS Rating Curve= 0 ,0
Exp/Cntr=0.3,0.1

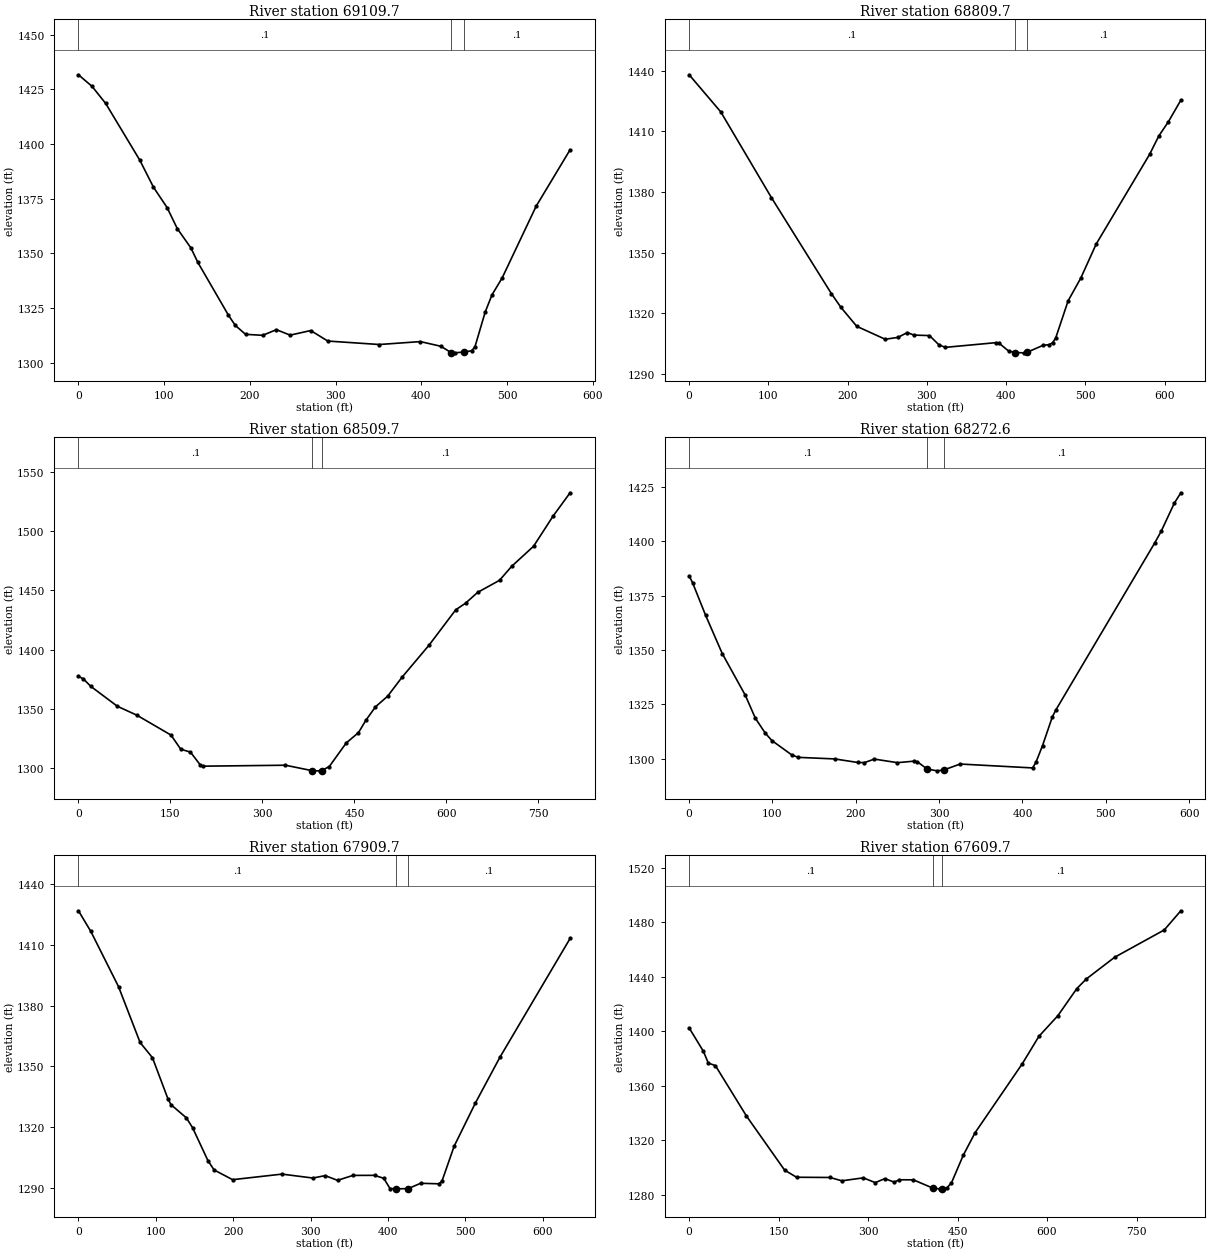
Type RM Length L Ch R = 1 ,69109.7 ,290.4,300,311.5
XS GIS Cut Line= 4
     1753916.582      309427.645     1753919.929      309610.534
      1754053.76      309833.243     1754122.745      309944.138
#Sta/Elev= 30
       0 1431.66    15.9 1426.36    31.8 1418.54    71.6  1392.6    87.5 1380.27
   103.4 1370.95   115.3 1361.32   131.2  1352.5   139.2 1345.93     175 1321.72
   182.9  1317.1   194.9 1313.01   214.9 1312.56   230.9 1315.14   246.9 1312.64
   270.9 1314.74   290.8 1309.94   350.8 1308.36   398.8 1309.69   422.8 1307.54
   434.8  1304.6   438.8 1304.55   450.2 1304.95   458.6 1305.51   462.5 1307.39
   474.4 1323.23   482.3 1331.05   494.2 1338.82   533.8 1371.57   573.4 1397.38
#Mann= 3 , 0 , 0
       0      .1       0   434.8    .045       0   450.2      .1       0
Bank Sta=434.8,450.2
XS Rating Curve= 0 ,0
Exp/Cntr=0.3,0.1

Type RM Length L Ch R = 1 ,68809.7 ,298.3,300,300.2
XS GIS Cut Line= 3
     1753714.127       309413.12      1753758.64      309829.807
     1753769.012      310030.944
#Sta/Elev= 30
       0  1437.9    39.9 1419.55   103.8  1377.2   179.6 1329.69   191.6 1322.93
   211.5 1313.61   247.4 1307.21   263.4 1308.13   275.4 1310.54   283.4 1309.28
   303.3 1309.02   315.3 1304.43   323.3 1303.21   387.1 1305.53   391.1 1305.27
   403.1  1301.4   411.6 1300.63     423  1300.5   426.6 1300.79   446.7 1304.23
   454.6 1304.55   458.6 1305.47   462.5 1307.76   478.3 1326.24   494.1 1337.33
   513.8 1354.35     581 1398.51   592.8 1407.73   604.7 1414.63   620.5 1425.35
#Mann= 3 , 0 , 0
       0      .1       0   411.6    .045       0   426.6      .1       0
Bank Sta=411.6,426.6
XS Rating Curve= 0 ,0
Exp/Cntr=0.3,0.1

Type RM Length L Ch R = 1 ,68509.7 ,240,237.1,234.3
XS GIS Cut Line= 3
     1753443.492      309449.346     1753461.508      309838.054
     1753477.919      310250.213
#Sta/Elev= 30
       0 1377.31     7.9 1375.34    19.8 1369.04    63.5 1352.05    95.3 1344.51
   150.9  1327.7   166.8 1315.75   182.6  1313.3   198.5 1302.56   202.5  1301.4
   337.5 1302.21   381.6 1297.54   393.1 1297.46   396.6 1297.68     409 1301.12
   436.7 1321.08   456.6 1329.79   468.4 1340.03   484.3 1351.58   504.1 1360.56
   527.9 1376.82   571.6 1403.72   615.2 1433.66   631.1 1439.21   650.9 1448.37
   686.6  1458.6   706.4 1470.43   742.1  1487.4   773.8 1512.85   801.6 1532.59
#Mann= 3 , 0 , 0
       0      .1       0   381.6    .045       0   396.6      .1       0
Bank Sta=381.6,396.6
XS Rating Curve= 0 ,0
Exp/Cntr=0.3,0.1

Type RM Length L Ch R = 1 ,68272.6 ,363.9,362.9,361.4
XS GIS Cut Line= 3
     1753176.565       309505.77     1753228.648      309798.739
     1753276.391      310087.367
#Sta/Elev= 30
       0  1384.1       4 1381.07    19.8 1365.94    39.7 1348.41    67.4  1329.2
    79.4  1318.7    91.2 1311.87    99.2 1308.41     123 1301.82   130.9 1300.66
   174.6 1299.94   202.3 1298.31   210.3 1298.24   222.2 1299.86     250 1298.22
   269.8 1298.91   273.8 1298.63   285.7 1295.28   297.6 1294.46   305.5 1294.85
   325.2 1297.59   412.2  1295.8   416.2 1298.39   424.1 1306.06   435.9 1319.29
   439.9 1322.34   558.5 1399.11   566.4 1404.56   582.2 1417.52   590.1 1422.36
#Mann= 3 , 0 , 0
       0      .1       0   285.7    .045       0   305.5      .1       0
Bank Sta=285.7,305.5
XS Rating Curve= 0 ,0
Exp/Cntr=0.3,0.1

Type RM Length L Ch R = 1 ,67909.7 ,301.7,300,294
XS GIS Cut Line= 3
     1752871.148      309535.832     1752969.878      309942.633
     1753024.655      310152.471
#Sta/Elev= 30
       0 1426.91      16 1416.72    51.8 1389.42    79.7  1361.8    95.7 1354.26
   115.6 1334.04   119.6 1331.07   139.5 1324.56   147.5  1319.7   167.4  1303.4
   175.4 1298.78   199.3 1293.99   263.1 1296.74     303  1294.8   318.9 1295.99
   334.9 1293.66   354.8  1296.1   382.7 1296.13   394.7 1294.66   402.7  1289.6
   410.6 1289.46   411.1 1289.48   426.1 1289.55   442.3  1292.2   465.9 1291.95
   469.9 1293.28   485.6 1310.51   513.2 1331.97   544.8 1354.52   635.5 1413.23
#Mann= 3 , 0 , 0
       0      .1       0   411.1    .045       0   426.1      .1       0
Bank Sta=411.1,426.1
XS Rating Curve= 0 ,0
Exp/Cntr=0.3,0.1

Type RM Length L Ch R = 1 ,67609.7 ,306.9,300,299.7
XS GIS Cut Line= 3
     1752557.978      309640.305     1752691.443      310034.241
     1752891.387      310390.309
#Sta/Elev= 30
       0 1402.54      24 1385.25      32 1376.76      44 1374.86      96 1337.89
     160 1298.14     180 1292.91     236 1292.74     256  1290.3     292 1292.47
     312 1288.96     328  1291.9   343.9 1289.29   351.9 1291.06   375.9 1291.01
   408.4 1284.95   419.9  1284.4   423.4 1284.44   431.8    1285   439.7 1288.73
   459.5 1309.04   479.4 1325.64   558.7 1376.39   586.4 1396.39   618.1  1411.5
   649.8 1431.37   665.7 1438.45   713.3 1454.42   796.5 1474.48   824.3 1488.56
#Mann= 3 , 0 , 0
       0      .1       0   408.4    .045       0   423.4      .1       0
Bank Sta=408.4,423.4
XS Rating Curve= 0 ,0
Exp/Cntr=0.3,0.1

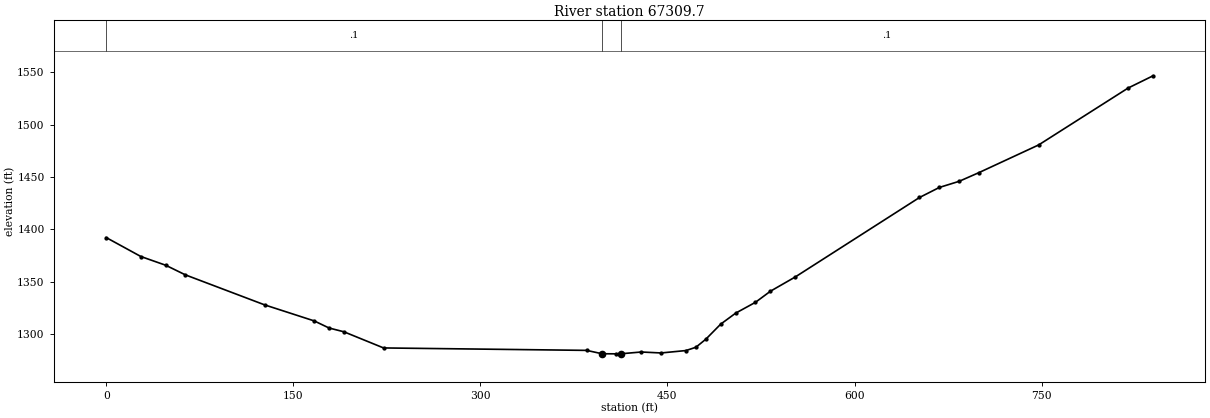
Type RM Length L Ch R = 1 ,67309.7 ,306.4,300,291.5
XS GIS Cut Line= 3
     1752169.479      309771.646     1752405.423      310100.905
     1752617.893      310479.687
#Sta/Elev= 30
       0 1392.16    27.8 1374.08    47.7 1365.76    63.5 1356.57   127.1 1327.92
   166.8 1312.64   178.7 1305.87   190.6 1302.27   222.4 1286.86   385.2 1284.53
   397.6 1281.32     409 1281.23   412.6 1281.28     429 1282.98   444.9 1282.07
   464.8 1284.36   472.8 1287.49   480.8 1295.19   492.7 1309.54   504.7 1320.04
   520.6  1330.4   532.6 1340.98   552.5 1354.57   652.1 1430.38     668 1439.95
     684 1445.86   699.9 1454.18   747.7 1480.55   819.4 1534.81   839.4  1546.5
#Mann= 3 , 0 , 0
       0      .1       0   397.6    .045       0   412.6      .1       0
Bank Sta=397.6,412.6
XS Rating Curve= 0 ,0
Exp/Cntr=0.3,0.1