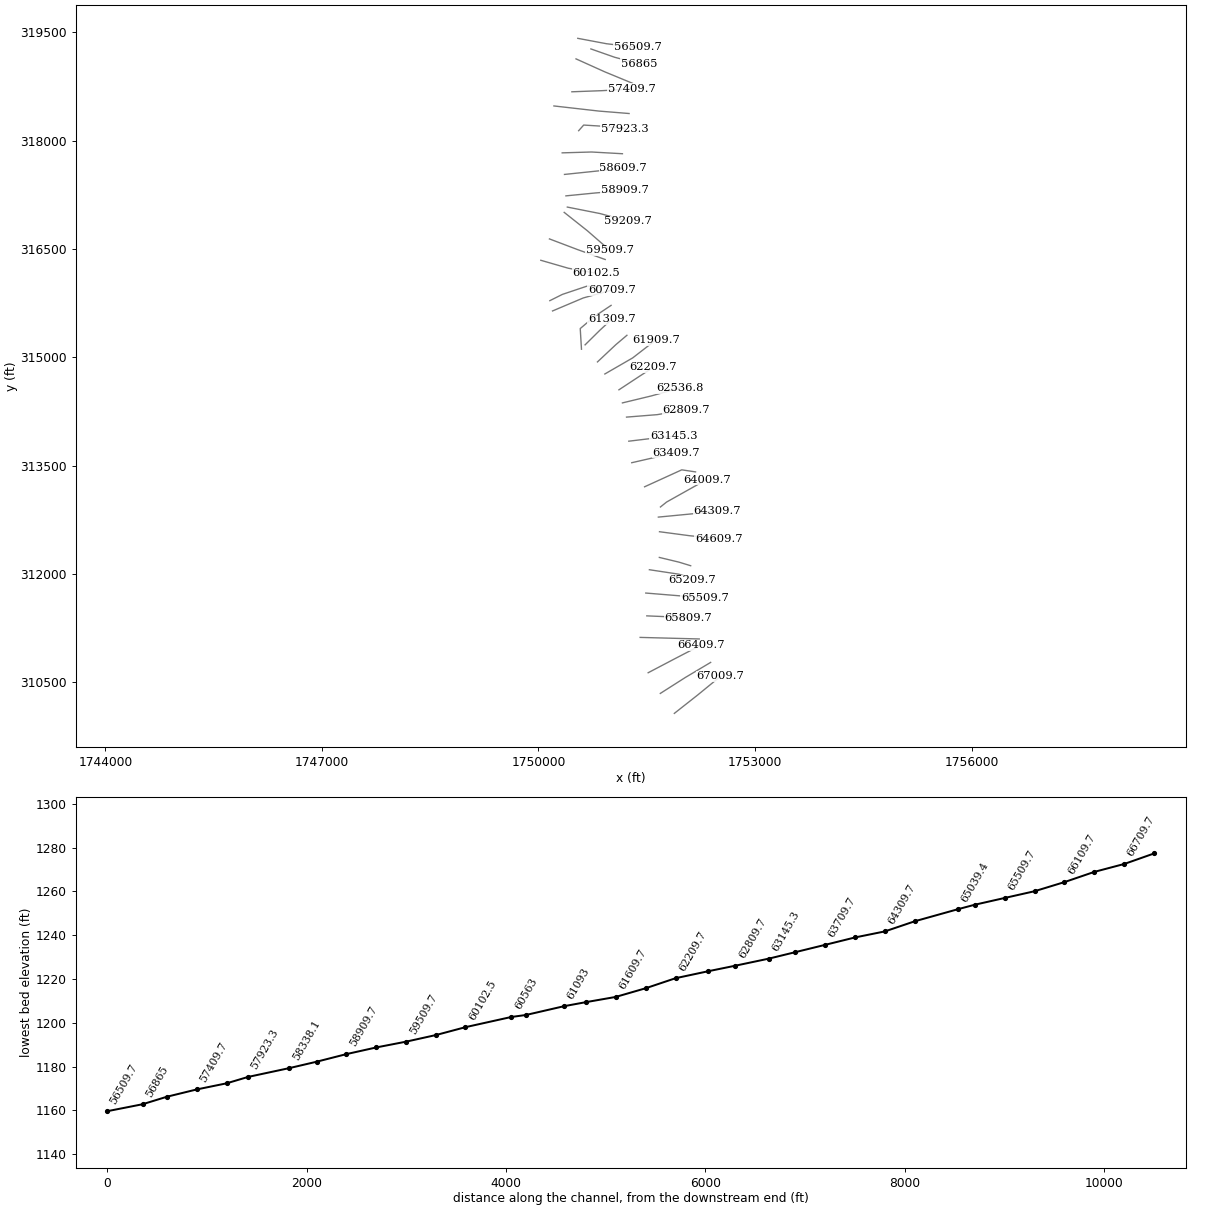
HEC-RAS study SPLAURFK.prj: SPLAURFK

--- SPLAURFK.g01 (geometry) --- (continued)

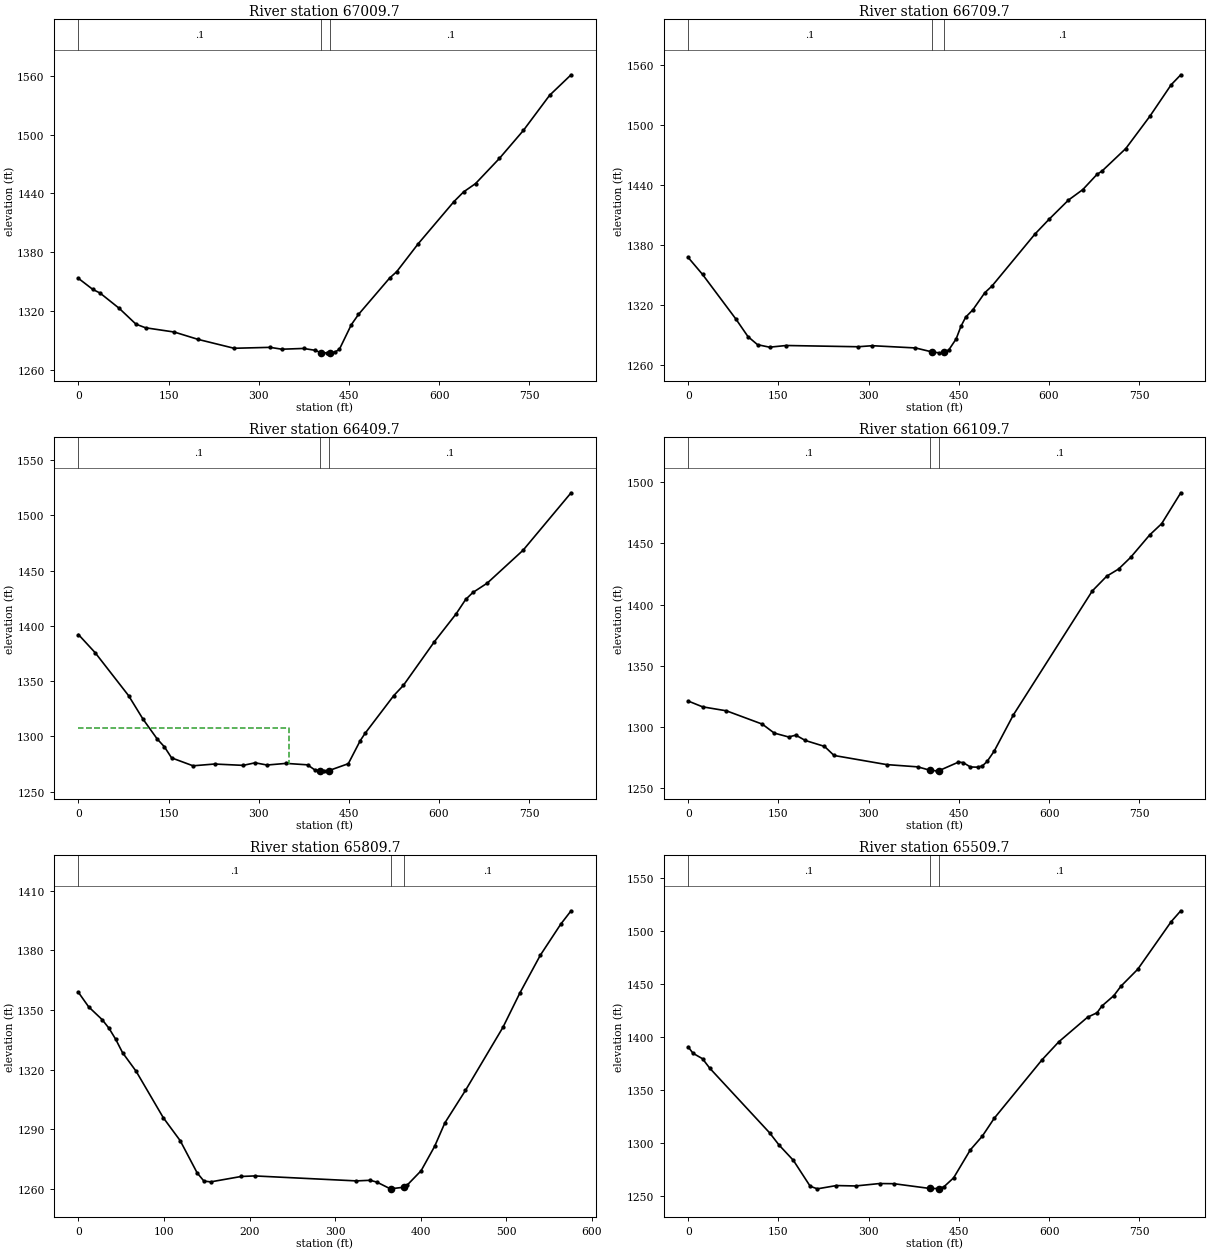
Type RM Length L Ch R = 1 ,67009.7 ,302.3,300,296.6
XS GIS Cut Line= 3
     1751882.558      310066.829     1752204.774      310320.563
     1752521.622      310579.481
#Sta/Elev= 30
       0 1353.26    23.9 1341.99    35.8 1338.36    67.7 1322.76    95.6 1306.58
   111.5 1302.91   159.3 1298.55   199.1 1291.02   258.8 1281.99   318.6 1282.93
   338.4 1281.03   374.3 1281.81   394.2 1279.84   402.6 1277.49   414.1 1277.33
   417.6 1277.44     426 1277.91     434    1281   453.8 1306.03   465.7 1316.51
   517.4 1353.56   529.3 1360.15   565.1 1388.68   624.6  1431.7   640.5  1441.5
   660.4    1450   700.1 1475.68   739.9 1504.18   783.6 1540.09   819.3 1561.01
#Mann= 3 , 0 , 0
       0      .1       0   402.6    .045       0   417.6      .1       0
Bank Sta=402.6,417.6
XS Rating Curve= 0 ,0
Exp/Cntr=0.3,0.1

Type RM Length L Ch R = 1 ,66709.7 ,302.1,300,298.5
XS GIS Cut Line= 3
     1751688.309      310343.249     1752033.883      310563.475
     1752385.654       310773.02
#Sta/Elev= 30
       0 1367.75    23.9  1350.8    79.6 1306.05    99.5 1288.67   115.4 1280.64
   135.3 1278.16   163.1 1279.84   282.5  1278.6   306.3 1279.63     378 1277.39
   405.8 1273.38   417.3 1272.51   425.7 1272.86   433.6 1275.62   445.6 1286.39
   453.5 1298.87   461.5 1308.17   473.4 1315.46   493.3 1332.57   505.2 1339.22
   576.7 1391.17   600.6 1406.19   632.4  1425.1   656.2 1435.54   680.1  1450.9
     688 1453.95   727.8  1476.6   767.6 1508.66   803.3 1540.34   819.2 1550.24
#Mann= 3 , 0 , 0
       0      .1       0   405.8    .045       0   425.7      .1       0
Bank Sta=405.8,425.7
XS Rating Curve= 0 ,0
Exp/Cntr=0.3,0.1

Type RM Length L Ch R = 1 ,66409.7 ,311.5,300,288.6
XS GIS Cut Line= 3
     1751520.015      310629.778     1751882.315      310820.139
     1752246.911      311009.478
#Sta/Elev= 30
       0 1392.19    27.8  1375.8    83.4 1336.96   107.3  1315.8   131.1 1297.68
     143 1290.68     155 1280.64   190.7 1273.46   226.5 1275.06   274.2 1273.85
     294 1276.18   313.9 1274.16   345.7 1275.64   381.4 1274.33   393.4 1269.75
   401.8 1269.07   409.3  1268.9   416.8  1269.1   449.2 1275.36   469.1 1296.22
   477.1 1302.81   524.9 1336.98   540.9 1346.23   592.7 1385.88   628.6 1410.88
   644.6    1424   656.6 1430.29   680.5 1438.76   740.3  1468.6   820.1 1520.53
#Mann= 3 , 0 , 0
       0      .1       0   401.8    .045       0   416.8      .1       0
#XS Ineff= 2 , 0
          349.92  1307.5
Permanent Ineff=
       F       F
Bank Sta=401.8,416.8
XS Rating Curve= 0 ,0
Exp/Cntr=0.3,0.1

Type RM Length L Ch R = 1 ,66109.7 ,300.3,300,299.6
XS GIS Cut Line= 3
     1751408.783      311119.285     1751818.142      311108.512
       1752227.5       311097.74
#Sta/Elev= 30
       0 1321.26    23.8 1316.53    63.6 1313.26   123.2 1302.39   143.1 1295.06
     167  1291.9   178.9 1293.39   194.8 1289.03   226.6 1284.21   242.5 1276.78
     330 1269.33   381.7 1267.48     402 1264.72   413.5 1264.23     417 1264.38
   449.3 1271.34   457.2 1270.99   469.1  1267.4   481.1 1267.22     489 1268.19
     497  1271.9   508.9 1280.46   540.7 1309.95   671.9 1411.22   695.8 1423.22
   715.6  1429.1   735.5 1438.56   767.3 1456.94   787.2 1466.15     819 1491.39
#Mann= 3 , 0 , 0
       0      .1       0     402    .045       0     417      .1       0
Bank Sta=402,417
XS Rating Curve= 0 ,0
Exp/Cntr=0.3,0.1

Type RM Length L Ch R = 1 ,65809.7 ,300.9,300,299.1
XS GIS Cut Line= 3
     1751501.217      311417.662     1751873.341      311401.872
     1752076.304      311391.621
#Sta/Elev= 30
       0 1358.79    11.9 1351.55    27.7 1345.11    35.7 1340.76    43.6 1335.17
    51.5 1328.52    67.4 1319.15    99.1 1295.83   118.9 1284.26   138.7 1268.07
   146.6 1263.96   154.5 1263.56   190.2 1266.28     206 1266.55   324.9 1264.05
   340.8 1264.36   348.7 1263.45   364.5 1260.06     365 1260.09     380 1260.86
   384.4 1262.05   400.4 1269.15   416.3 1281.48   428.2 1293.22   452.2  1309.5
     496 1341.21   515.9 1358.56   539.8 1377.54   563.7 1393.17   575.7 1399.85
#Mann= 3 , 0 , 0
       0      .1       0     365    .045       0     380      .1       0
Bank Sta=365,380
XS Rating Curve= 0 ,0
Exp/Cntr=0.3,0.1

Type RM Length L Ch R = 1 ,65509.7 ,301.5,300,295.2
XS GIS Cut Line= 3
     1751486.885      311733.727     1751895.021      311700.335
     1752303.157      311666.943
#Sta/Elev= 30
       0 1390.84       8  1384.8    23.8 1379.66    35.8 1370.77   135.2  1309.9
   151.1 1298.26   174.9 1283.82   202.8 1259.44   214.7 1256.98   246.5 1260.08
   278.3 1259.69   318.1 1261.97   341.9 1261.83     402 1257.32     417 1257.26
   425.4 1259.03   441.3 1267.34   469.1 1293.72     489 1306.66   508.9 1323.56
   588.4 1378.69   616.2 1395.62     664 1418.79   679.8 1423.01   687.8 1429.32
   707.7 1439.14   719.6  1448.1   747.4 1463.98   803.1 1508.93     819 1519.14
#Mann= 3 , 0 , 0
       0      .1       0     402    .045       0     417      .1       0
Bank Sta=402,417
XS Rating Curve= 0 ,0
Exp/Cntr=0.3,0.1

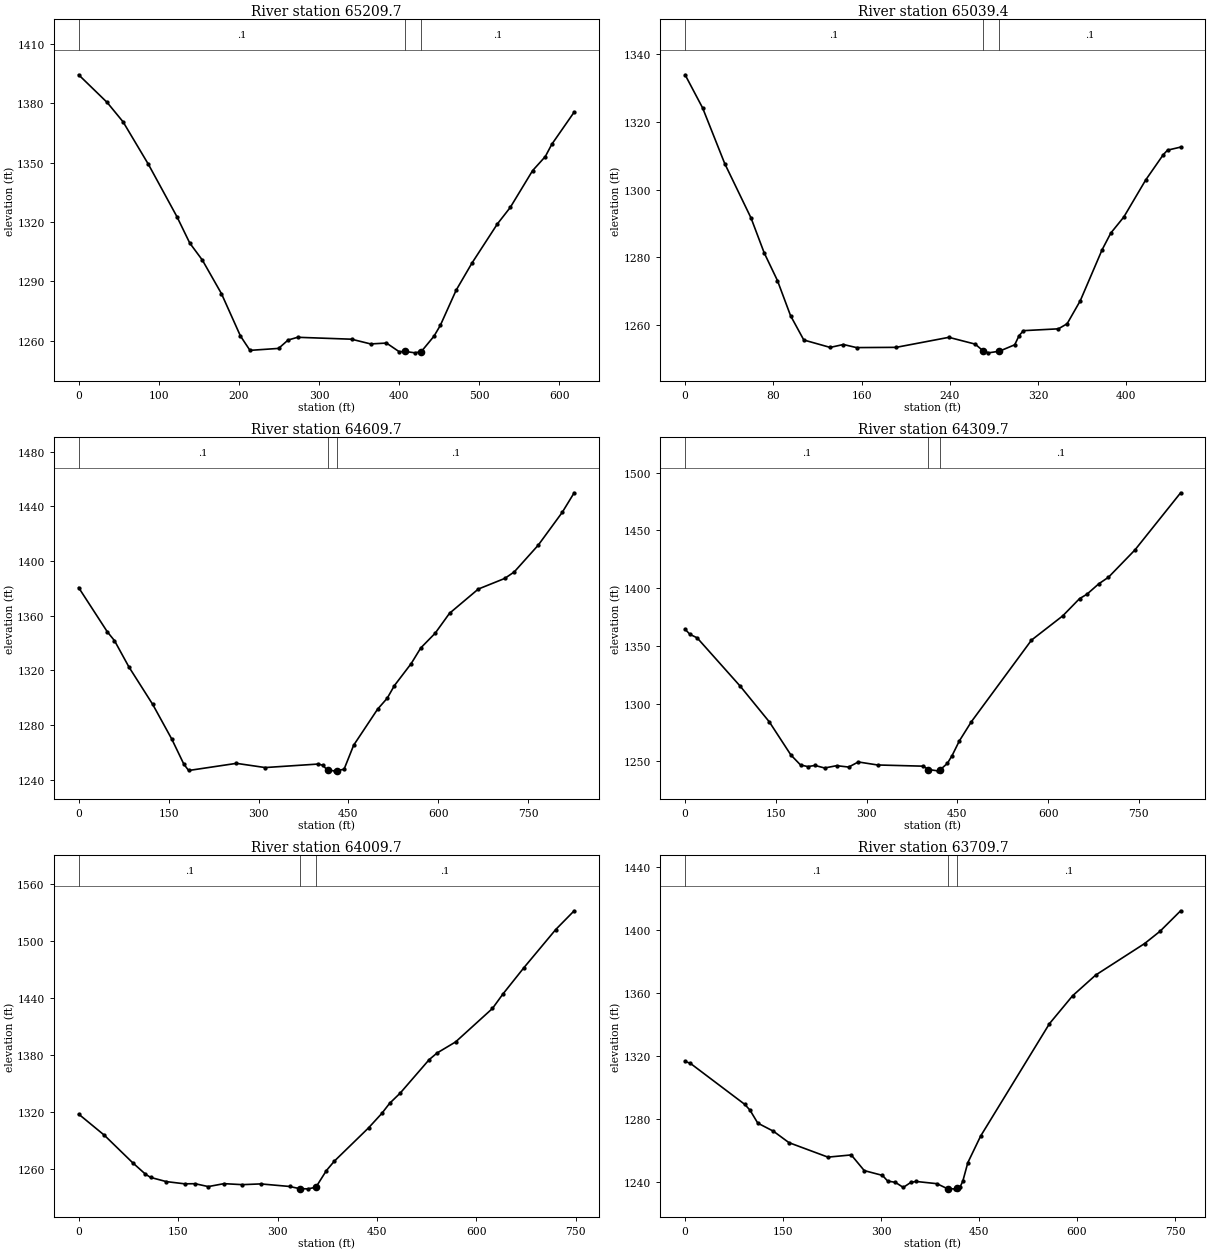
Type RM Length L Ch R = 1 ,65209.7 ,172.3,170.2,169.8
XS GIS Cut Line= 4
     1751536.934      312056.822     1751944.293      311995.116
     1752042.753       311965.55     1752130.558      311910.284
#Sta/Elev= 30
       0 1394.43    35.6 1380.45    55.5 1370.63    87.2  1349.1   122.8 1322.64
   138.7 1309.39   154.5 1300.74   178.3  1283.8     202  1262.4   213.9 1255.14
   249.6 1256.13   261.5 1260.37   273.4 1261.75   340.7 1260.78   364.5 1258.39
   384.3 1258.83   400.1 1254.48     408 1254.57   419.9 1253.89   427.8 1254.55
   443.6  1262.3   451.5 1267.76   471.3 1285.58   491.1 1299.32   522.8 1319.08
   538.8 1327.37   566.7 1345.99   582.6 1353.12   590.6 1359.26   618.6 1375.57
#Mann= 3 , 0 , 0
       0      .1       0     408    .045       0   427.8      .1       0
Bank Sta=408,427.8
XS Rating Curve= 0 ,0
Exp/Cntr=0.3,0.1

Type RM Length L Ch R = 1 ,65039.4 ,427.5,429.8,434.3
XS GIS Cut Line= 3
     1751674.828      312227.124     1751946.096       312162.02
     1752108.856      312112.107
#Sta/Elev= 30
       0 1333.93    15.9 1324.13    35.9 1307.73    59.8 1291.62    71.7 1281.35
    83.7 1273.18    95.6  1262.8   107.6 1255.62   131.5 1253.43   143.5 1254.29
   155.4 1253.38   191.3 1253.45   239.1 1256.41     263  1254.4   269.9 1252.47
     275 1251.83   284.9 1252.31   298.8 1254.21   302.7 1256.88   306.7 1258.38
   338.4 1258.92   346.3 1260.42   358.2  1267.2     378 1282.26   385.9  1287.2
   397.7 1291.94   417.5 1302.86   433.4 1310.31   437.3 1311.67   449.2 1312.58
#Mann= 3 , 0 , 0
       0      .1       0   269.9    .045       0   284.9      .1       0
Bank Sta=269.9,284.9
XS Rating Curve= 0 ,0
Exp/Cntr=0.3,0.1

Type RM Length L Ch R = 1 ,64609.7 ,294.8,300,304.4
XS GIS Cut Line= 3
     1751677.057      312583.228     1752096.124      312527.561
     1752497.999      312488.921
#Sta/Elev= 30
       0 1380.49    47.9 1348.07    59.8 1341.66    83.8 1322.45   123.6 1294.95
   155.5 1269.47   175.5 1251.23   183.5 1246.61   263.2 1251.84   311.1 1248.76
   398.8 1251.31   406.8 1250.53   415.2 1246.83   426.8 1246.36   430.2 1246.46
   442.7  1247.5   458.7 1265.11   498.7 1291.53   514.7 1299.53   526.7 1308.77
   554.7 1324.89   570.6 1336.29   594.6 1347.06   618.6 1361.67   666.6 1379.41
   710.6 1387.17   726.5 1391.93   766.5 1411.51   806.5  1435.5   826.5 1449.88
#Mann= 3 , 0 , 0
       0      .1       0   415.2    .045       0   430.2      .1       0
Bank Sta=415.2,430.2
XS Rating Curve= 0 ,0
Exp/Cntr=0.3,0.1

Type RM Length L Ch R = 1 ,64309.7 ,290.6,300,309.3
XS GIS Cut Line= 3
     1751661.065      312785.903     1752068.685      312825.094
      1752476.15      312865.904
#Sta/Elev= 30
       0 1364.34       8 1359.95    19.9 1356.92    91.4 1314.86   139.2 1284.14
   174.9 1255.43   190.8  1246.8   202.8 1245.42   214.7  1246.4   230.6  1244.2
   250.5  1246.2   270.4    1245   286.2 1249.42   318.1 1246.81   393.6 1245.77
     402 1242.87   417.4 1241.73   421.4 1242.59   433.4 1248.14   441.3 1254.96
   453.2  1267.6   473.1 1284.24   572.5 1354.95   624.2 1375.97     652  1390.9
     664 1394.62   683.8 1403.75   699.7 1409.38   743.5 1433.06     819 1482.55
#Mann= 3 , 0 , 0
       0      .1       0     402    .045       0   421.4      .1       0
Bank Sta=402,421.4
XS Rating Curve= 0 ,0
Exp/Cntr=0.3,0.1

Type RM Length L Ch R = 1 ,64009.7 ,301.8,300,298.1
XS GIS Cut Line= 4
     1751690.019      312925.909     1751774.497      312993.936
      1751974.59      313106.183     1752331.733      313306.532
#Sta/Elev= 30
       0 1317.67    38.7 1295.46    81.4  1266.5   100.7 1254.46   108.5    1251
   132.2 1246.59   159.9 1244.24   175.7 1244.36   195.5 1241.34   219.2 1244.41
   246.9 1243.37   274.6 1244.15   318.1 1241.46   333.9 1239.07   345.8 1238.96
   357.8 1240.59   373.7 1258.18   385.6 1268.06   437.3 1303.17   457.2 1318.31
   469.1 1329.02     485 1339.74   528.7 1374.99   540.6 1381.98   568.5  1393.6
   624.1 1428.84     640 1444.13   671.8 1471.97   719.6 1511.97   747.4 1531.71
#Mann= 3 , 0 , 0
       0      .1       0   333.9    .045       0   357.8      .1       0
Bank Sta=333.9,357.8
XS Rating Curve= 0 ,0
Exp/Cntr=0.3,0.1

Type RM Length L Ch R = 1 ,63709.7 ,304.6,300,295.4
XS GIS Cut Line= 4
     1751470.506      313205.751     1751843.097      313375.652
     1751985.241       313440.47      1752176.13       313412.02
#Sta/Elev= 30
       0 1316.46       8 1315.27    91.4 1289.19    99.4  1285.5   111.3 1277.29
   135.2 1272.17     159 1264.91   218.7 1255.71   254.4 1257.11   274.3 1247.16
   302.2 1244.11   310.1 1240.54     322 1239.69     334 1236.48   345.9 1239.73
   353.8 1240.26   385.6 1238.85     402  1235.6   413.4 1235.58     417 1235.81
   421.2 1236.98   425.1 1240.33   432.9 1252.24   452.5 1269.09   557.9 1340.47
   593.3 1358.16   628.7 1371.32   703.6 1391.32   727.2 1399.12   758.7 1412.11
#Mann= 3 , 0 , 0
       0      .1       0     402    .045       0     417      .1       0
Bank Sta=402,417
XS Rating Curve= 0 ,0
Exp/Cntr=0.3,0.1

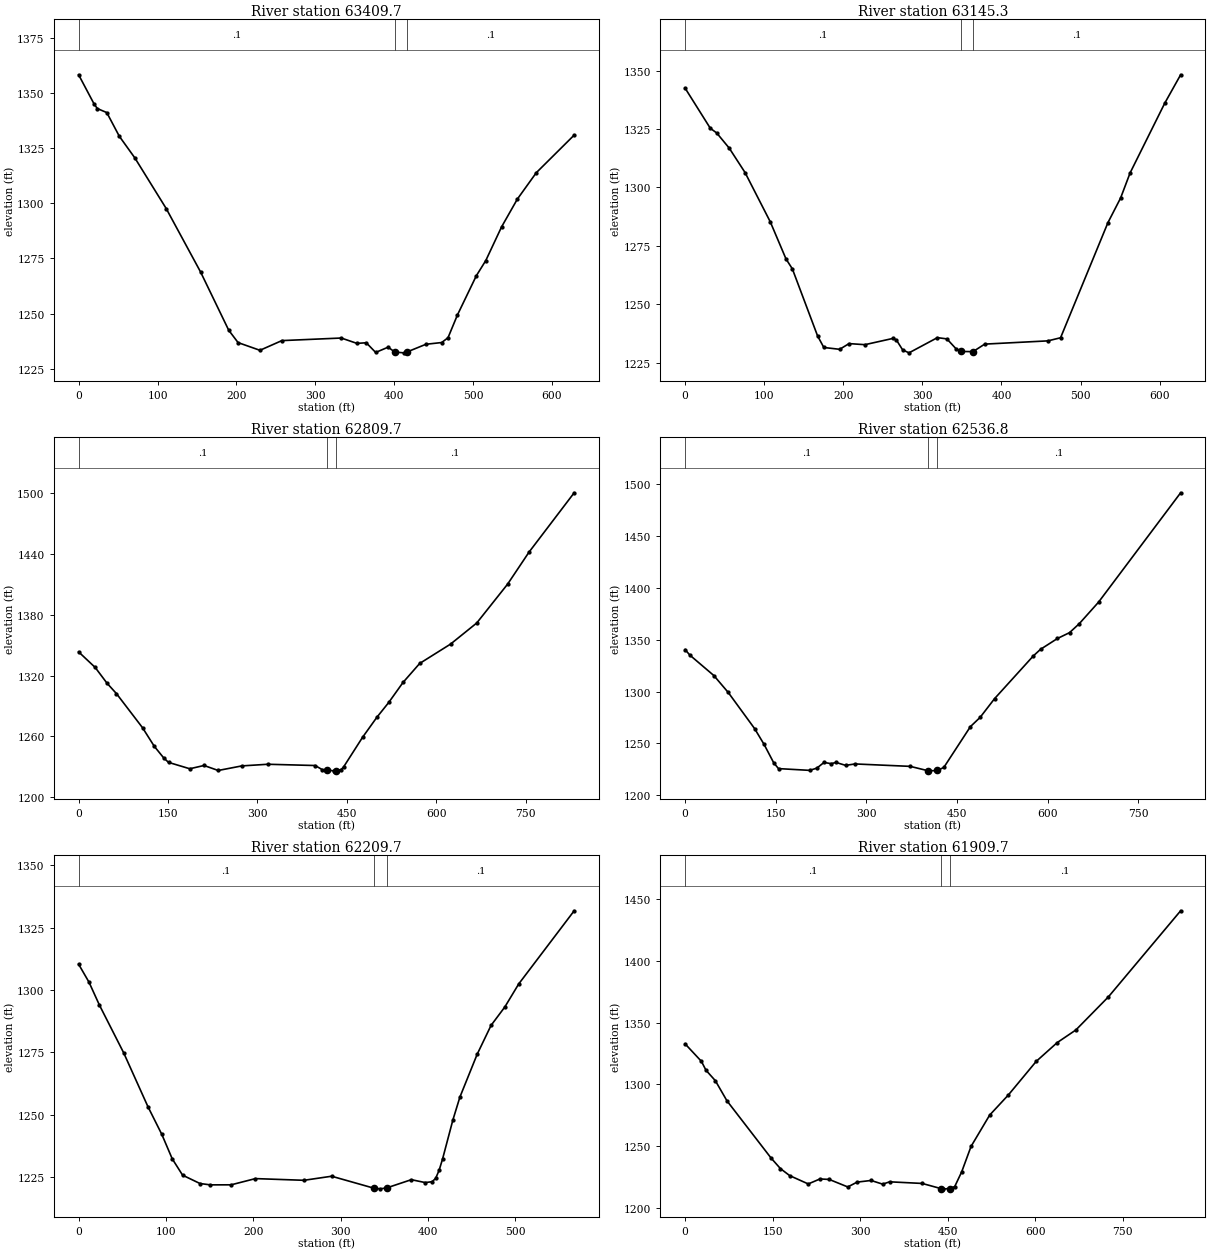
Type RM Length L Ch R = 1 ,63409.7 ,266.9,264.4,261.4
XS GIS Cut Line= 3
     1751292.504      313539.223     1751690.382      313630.304
     1751904.863      313678.947
#Sta/Elev= 30
       0  1358.2    19.8 1344.82    23.8 1342.89    35.7 1341.07    51.5 1330.38
    71.3 1320.51     111  1297.6   154.6 1268.84   190.2  1242.5   202.1 1236.87
   229.8 1233.38   257.6 1237.77   332.9 1238.94   352.7 1236.52   364.6 1236.79
   376.5 1232.41   392.3  1234.8   400.7 1232.58   412.2 1232.23   415.7 1232.55
   440.2 1236.11   460.2  1236.9   468.2 1239.08   480.2 1249.44   504.1 1267.16
   516.1 1274.06   536.1  1289.3   556.1 1301.89   580.1 1313.84   628.1 1330.87
#Mann= 3 , 0 , 0
       0      .1       0   400.7    .045       0   415.7      .1       0
Bank Sta=400.7,415.7
XS Rating Curve= 0 ,0
Exp/Cntr=0.3,0.1

Type RM Length L Ch R = 1 ,63145.3 ,336.7,335.6,337.2
XS GIS Cut Line= 3
     1751251.651      313837.367     1751611.894       313880.77
     1751874.481      313904.642
#Sta/Elev= 30
       0 1342.49    31.9 1325.31    39.9 1323.34    55.8 1316.83    75.8 1306.39
   107.7 1285.31   127.6 1269.43   135.6  1265.2   167.5 1236.52   175.4 1231.58
   195.4  1230.8   207.3 1233.24   227.3 1232.78   263.2 1235.49   267.2 1234.75
   275.1 1230.52   283.1 1229.29     319 1235.79     331 1235.25   342.9  1230.9
     349 1229.87     364 1229.81   378.8 1233.02   458.7 1234.41   474.7 1235.74
   534.6 1284.98   550.6  1295.5   562.6 1306.23   606.5 1336.11   626.5  1348.2
#Mann= 3 , 0 , 0
       0      .1       0     349    .045       0     364      .1       0
Bank Sta=349,364
XS Rating Curve= 0 ,0
Exp/Cntr=0.3,0.1

Type RM Length L Ch R = 1 ,62809.7 ,269.1,272.9,275.1
XS GIS Cut Line= 3
     1751220.348      314170.983     1751643.677        314204.9
     1752044.962       314271.78
#Sta/Elev= 30
       0 1343.37    27.8 1328.03    47.6 1312.52    63.5  1302.2   107.2  1268.6
     127 1250.21   142.9 1238.71   150.8 1234.42   186.5 1228.12   210.4 1231.35
   234.2 1226.43   273.9 1230.94   317.5 1232.56   396.9 1231.31   408.8 1227.23
   417.2 1226.77   428.7 1226.07   432.2 1226.22   440.6 1227.39   444.6  1229.9
   476.5 1259.21   500.5 1278.93   520.4 1293.55   544.3 1313.23   572.3 1331.99
   624.1 1351.08     668 1371.87   719.8  1410.2   755.7 1441.74   831.5  1500.3
#Mann= 3 , 0 , 0
       0      .1       0   417.2    .045       0   432.2      .1       0
Bank Sta=417.2,432.2
XS Rating Curve= 0 ,0
Exp/Cntr=0.3,0.1

Type RM Length L Ch R = 1 ,62536.8 ,319.6,327.1,333.7
XS GIS Cut Line= 3
     1751163.399      314367.843     1751564.151      314464.537
     1751956.934       314574.33
#Sta/Elev= 30
       0 1340.51     7.9 1335.17    47.6 1315.47    71.4 1299.15     115 1264.31
   130.8 1248.96   146.7 1231.23   154.6 1225.68   206.1 1223.99     218 1226.13
   229.9 1231.63   241.8 1230.44   249.7 1231.64   265.6 1228.82   281.4 1230.18
   372.6 1227.84   402.6 1223.55   404.3 1223.53   417.6 1223.88   428.2 1226.84
   472.2 1266.19   488.2 1275.07   512.2 1293.21   576.2 1334.35   588.2 1340.77
   616.2 1351.22   636.2 1356.86   652.2 1365.42   684.2 1386.25   820.1 1491.82
#Mann= 3 , 0 , 0
       0      .1       0   402.6    .045       0   417.6      .1       0
Bank Sta=402.6,417.6
XS Rating Curve= 0 ,0
Exp/Cntr=0.3,0.1

Type RM Length L Ch R = 1 ,62209.7 ,301.3,300,302.3
XS GIS Cut Line= 3
     1751114.933      314549.173     1751403.392      314739.162
     1751590.193      314859.503
#Sta/Elev= 30
       0  1310.3    11.9  1303.1    23.8 1293.95    51.6 1274.82    79.4 1253.24
    95.3 1242.14   107.2 1232.38   119.1 1225.82     139 1222.48   150.9 1221.94
   174.7 1221.96   202.5 1224.45   258.1 1223.77   289.8  1225.4   337.9 1220.64
   345.4 1220.35   352.9 1220.73   381.1 1224.02     397 1222.86   404.9 1223.21
   408.9 1224.53   412.9 1227.78   416.8 1232.23   428.7 1247.96   436.7 1257.09
   456.5 1274.25   472.4 1285.81   488.2  1293.2   504.1 1302.42   567.6 1331.71
#Mann= 3 , 0 , 0
       0      .1       0   337.9    .045       0   352.9      .1       0
Bank Sta=337.9,352.9
XS Rating Curve= 0 ,0
Exp/Cntr=0.3,0.1

Type RM Length L Ch R = 1 ,61909.7 ,294.6,300,300.6
XS GIS Cut Line= 3
     1750919.922      314768.521     1751306.128      314991.562
     1751624.713      315238.467
#Sta/Elev= 30
       0 1332.82    27.9 1318.72    35.8  1311.5    51.8  1303.1    71.7 1286.83
   147.3 1240.62   163.3 1232.12   179.2 1226.43     211 1219.71     231 1223.73
   246.9 1223.36   278.7 1217.29   294.7 1221.19   318.6 1222.52   338.5 1219.54
   350.4 1221.43   406.2 1220.12   438.5 1215.94     442 1215.76   453.5 1215.87
     462 1217.64   473.9  1229.5   489.9    1250   521.8 1275.29   553.7 1291.47
   601.6 1318.68   637.5 1333.82   669.5 1344.02   725.3 1370.78     849 1440.25
#Mann= 3 , 0 , 0
       0      .1       0   438.5    .045       0   453.5      .1       0
Bank Sta=438.5,453.5
XS Rating Curve= 0 ,0
Exp/Cntr=0.3,0.1

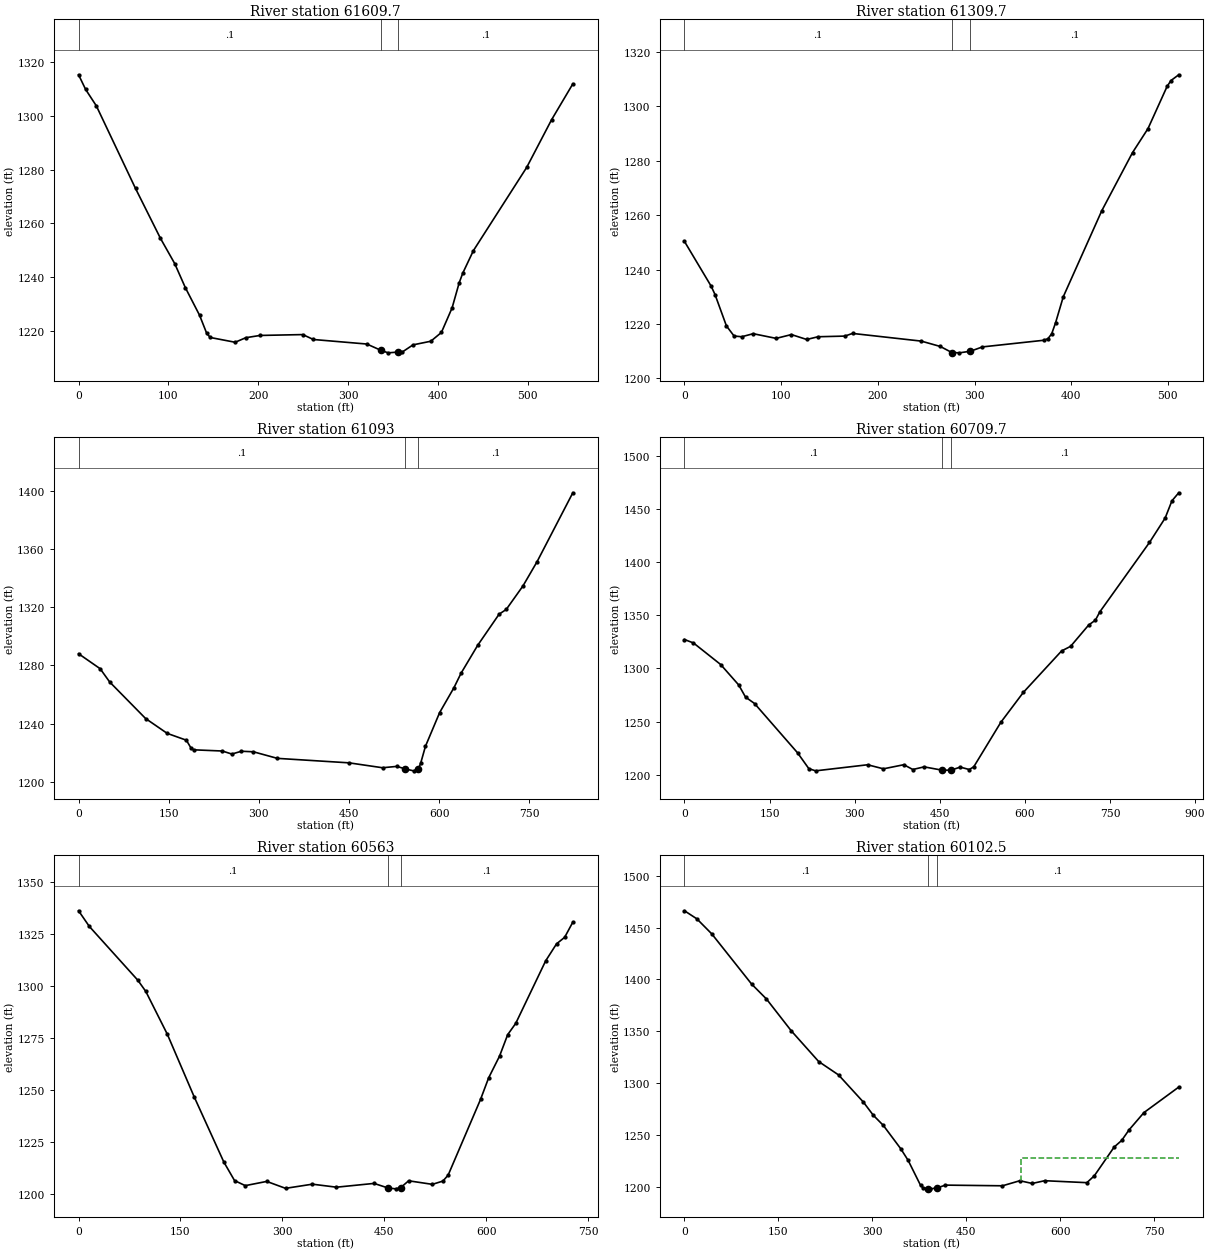
Type RM Length L Ch R = 1 ,61609.7 ,299.3,300,301.3
XS GIS Cut Line= 3
     1750817.624      314935.458     1751071.701      315174.125
      1751225.61      315304.381
#Sta/Elev= 30
       0 1315.39     7.9 1309.91    19.8  1303.8    63.4 1273.03    91.1 1254.49
     107 1245.07   118.8 1236.13   134.7  1225.8   142.6  1219.1   146.6 1217.52
   174.3 1215.74   186.2 1217.44     202 1218.28   249.6  1218.6   261.4 1216.77
   320.9 1215.08   336.7 1212.72   344.6  1211.8   356.1  1212.1   360.4 1212.12
   372.3 1214.77   392.1 1216.12   403.9 1219.39   415.8 1228.54   423.7  1237.9
   427.7  1241.5   439.5 1249.87   498.8 1280.86   526.5 1298.61   550.2    1312
#Mann= 3 , 0 , 0
       0      .1       0   336.7    .045       0   356.1      .1       0
Bank Sta=336.7,356.1
XS Rating Curve= 0 ,0
Exp/Cntr=0.3,0.1

Type RM Length L Ch R = 1 ,61309.7 ,218.9,216.6,213
XS GIS Cut Line= 3
     1750646.183      315172.003     1750851.188      315374.735
     1751015.106      315525.735
#Sta/Elev= 30
       0 1250.32    27.6 1233.89    31.6 1230.82    43.4 1219.29    51.3 1215.59
    59.2 1215.32    71.1 1216.44    94.8 1214.72   110.6 1216.12   126.4 1214.32
   138.2 1215.32   165.9 1215.56   173.8 1216.54   244.9 1213.72   264.6 1211.75
   276.5 1209.53   284.4 1209.41   295.8 1210.01   308.2 1211.59   371.9 1214.04
   375.9 1214.61   379.8  1216.4   383.8 1220.43   391.8 1230.02   431.6  1261.6
   463.4 1282.96   479.4 1291.77   499.2  1307.3   503.2 1309.43   511.2 1311.54
#Mann= 3 , 0 , 0
       0      .1       0   276.5    .045       0   295.8      .1       0
Bank Sta=276.5,295.8
XS Rating Curve= 0 ,0
Exp/Cntr=0.3,0.1

Type RM Length L Ch R = 1 ,61093   ,386.4,383.4,377.5
XS GIS Cut Line= 4
     1750596.269      315111.239     1750578.908      315397.697
     1750776.391      315564.798     1751006.426      315718.878
#Sta/Elev= 30
       0    1288    35.9 1277.72    51.8 1268.59   111.6  1243.5   147.5 1233.32
   179.4 1228.62   187.3 1223.13   191.3 1222.03   239.2  1221.2   255.1 1219.12
     271 1221.04     291 1220.67   330.8 1216.16   450.2 1213.08   505.9 1209.71
   529.8 1210.65   543.2 1208.95   557.5 1207.59   565.4 1208.76   569.4 1212.84
   577.3 1224.43     601 1247.64   624.8 1264.71   636.6 1274.63   664.3 1293.81
   699.9 1315.15   711.8 1318.41   739.5 1334.47   763.2 1351.28   822.6 1398.51
#Mann= 3 , 0 , 0
       0      .1       0   543.2    .045       0   565.4      .1       0
Bank Sta=543.2,565.4
XS Rating Curve= 0 ,0
Exp/Cntr=0.3,0.1

Type RM Length L Ch R = 1 ,60709.7 ,151.1,146.7,146.6
XS GIS Cut Line= 3
     1750195.374      315641.644     1750621.134      315821.734
      1751015.23       315930.65
#Sta/Elev= 30
       0 1327.23    15.9 1323.98    63.8 1303.68    95.6 1284.43   107.6 1273.02
   123.5 1266.97   199.3 1220.55   219.2 1205.63   231.1 1203.56   322.8 1209.28
   350.7 1205.46   386.6 1209.32   402.5 1204.82   422.4  1207.3   454.8 1204.13
   469.8 1204.22   486.1 1207.06     502  1204.8   509.9 1207.35   557.6 1249.24
   597.2 1277.38   664.7 1316.47   680.6 1320.81   712.4 1340.85   724.3 1345.46
   732.2 1353.33   819.6 1418.62   847.3 1441.69   859.2 1457.85   871.2 1465.43
#Mann= 3 , 0 , 0
       0      .1       0   454.8    .045       0   469.8      .1       0
Bank Sta=454.8,469.8
XS Rating Curve= 0 ,0
Exp/Cntr=0.3,0.1

Type RM Length L Ch R = 1 ,60563   ,471.7,460.5,448.1
XS GIS Cut Line= 5
     1750157.901      315783.982     1750331.512      315870.787
     1750589.759      315957.593     1750674.394      315985.805
     1750845.835      315974.954
#Sta/Elev= 30
       0 1336.37    15.8 1328.86    87.2 1302.99      99 1297.57   130.7 1276.97
   170.3 1246.81   213.8 1215.57   229.6 1206.63   245.4 1204.19     277 1206.22
   304.7 1202.89   344.2 1204.89   379.7 1203.44     435 1205.26   455.2  1203.1
   466.6 1202.65   474.3 1203.28   485.9 1206.52   520.8 1204.81   536.4 1206.39
   544.1 1209.28   591.7 1245.62   603.7 1256.05   619.7 1266.46   631.7 1276.79
   643.6 1282.25   687.6 1312.28   703.6 1320.46   715.6 1323.62   727.6 1330.91
#Mann= 3 , 0 , 0
       0      .1       0   455.2    .045       0   474.3      .1       0
Bank Sta=455.2,474.3
XS Rating Curve= 0 ,0
Exp/Cntr=0.3,0.1

Type RM Length L Ch R = 1 ,60102.5 ,294.7,292.9,289
XS GIS Cut Line= 3
     1750032.732      316343.468     1750413.978      316233.201
     1750800.262      316163.756
#Sta/Elev= 30
       0 1466.17    19.8 1458.39    43.7 1443.82   107.2  1395.5     131 1381.04
   170.6 1350.36   214.3 1320.79   246.1 1307.85   285.8 1281.61   301.6 1268.94
   317.5 1259.24   345.3 1236.76   357.2 1225.48     377 1201.44     381 1199.06
   389.1 1198.05   392.9 1197.99   404.1 1198.97   416.7 1201.58   507.9 1200.93
   535.6 1205.81   555.4 1203.18   575.3 1205.83   642.7 1203.94   654.6 1210.59
   686.3 1238.32   698.2 1244.63   710.1 1254.87   733.8 1271.52   789.4 1296.12
#Mann= 3 , 0 , 0
       0      .1       0   389.1    .045       0   404.1      .1       0
#XS Ineff= 2 , 0
                           536.8          1227.5
Permanent Ineff=
       F       F
Bank Sta=389.1,404.1
XS Rating Curve= 0 ,0
Exp/Cntr=0.3,0.1

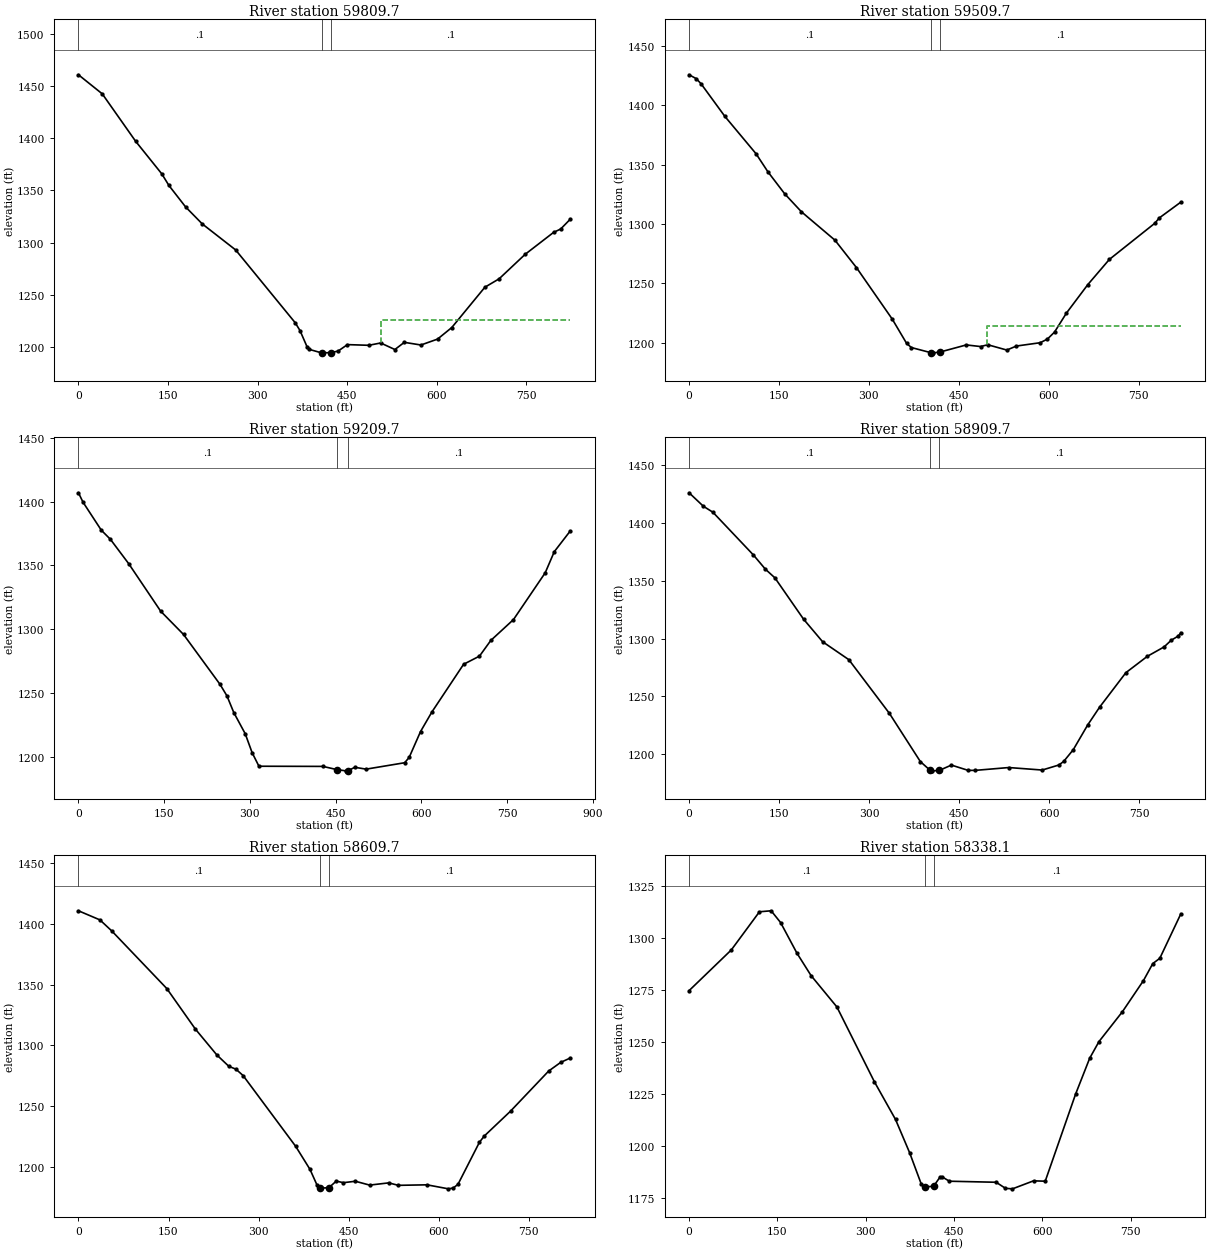
Type RM Length L Ch R = 1 ,59809.7 ,307.3,300,291.2
XS GIS Cut Line= 3
     1750152.508      316639.416     1750540.243      316492.243
     1750924.794      316354.199
#Sta/Elev= 30
       0 1460.84    39.9 1442.56    95.7 1397.17   139.6 1365.87   151.5 1354.77
   179.4 1334.23   207.4 1317.91   263.2 1293.02   362.9 1223.28   370.9 1215.82
   382.8 1200.16   386.8  1197.7   406.8 1194.43   407.2 1194.43   422.2  1194.6
   434.6 1196.08   450.4 1202.31   486.1 1201.65     506 1203.88   529.8  1197.6
   545.6 1204.49   573.4 1201.94   601.2 1207.58     625 1218.64   680.5  1257.3
   704.3 1265.34   747.9 1288.82   795.5 1309.83   807.4 1313.08   823.3 1322.38
#Mann= 3 , 0 , 0
       0      .1       0   407.2    .045       0   422.2      .1       0
#XS Ineff= 2 , 0
                          507.07         1225.42
Permanent Ineff=
       F       F
Bank Sta=407.2,422.2
XS Rating Curve= 0 ,0
Exp/Cntr=0.3,0.1

Type RM Length L Ch R = 1 ,59509.7 ,289.3,300,310.2
XS GIS Cut Line= 3
     1750356.843      317007.032     1750678.717      316751.609
     1750987.646      316482.448
#Sta/Elev= 30
       0 1425.86      12 1422.59      20 1418.26    59.8 1390.72   111.7  1359.3
   131.6    1344   159.6 1325.46   187.5 1310.32   243.4  1286.4   279.3 1263.28
   339.1 1219.78     363 1199.37     371 1195.85   403.4 1191.55   406.9  1191.4
   418.4 1192.03   462.6 1198.07   486.5  1196.7   498.4 1198.23   530.2 1193.75
   546.2 1197.13   585.9 1199.93   597.9 1202.98   609.8 1208.87   629.7 1224.92
   665.5 1249.01   701.3 1270.15   776.9 1300.54   784.8  1305.2   820.6 1318.48
#Mann= 3 , 0 , 0
       0      .1       0   403.4    .045       0   418.4      .1       0
#XS Ineff= 2 , 0
                          496.33         1214.29
Permanent Ineff=
       F       F
Bank Sta=403.4,418.4
XS Rating Curve= 0 ,0
Exp/Cntr=0.3,0.1

Type RM Length L Ch R = 1 ,59209.7 ,293.4,300,307.8
XS GIS Cut Line= 3
     1750399.948      317080.542     1750850.927       316991.27
     1751237.631      316886.537
#Sta/Elev= 30
       0 1406.91       8 1399.53      40 1377.56      56 1370.36      88 1351.25
   143.9    1314   183.9 1295.73   247.8 1256.55   259.8  1247.6   271.8 1234.49
   291.8 1217.87   303.8  1203.1   315.8 1192.36   427.8 1192.23   452.2 1189.72
   467.7 1188.75   471.6 1188.82   483.5 1191.53   503.4 1190.08   570.8 1195.11
   578.7 1199.32   598.6  1219.6   618.4  1234.9   673.9 1272.35   701.7 1278.75
   721.5 1291.04   761.2 1307.44   816.7 1344.12   832.6 1360.71   860.4 1376.87
#Mann= 3 , 0 , 0
       0      .1       0   452.2    .045       0   471.6      .1       0
Bank Sta=452.2,471.6
XS Rating Curve= 0 ,0
Exp/Cntr=0.3,0.1

Type RM Length L Ch R = 1 ,58909.7 ,299.8,300,300.4
XS GIS Cut Line= 3
     1750380.731      317235.841     1750788.018      317275.956
     1751196.661      317310.591
#Sta/Elev= 30
       0 1425.93    23.8 1414.29    39.7 1409.11   107.3 1372.12   127.2 1359.88
     143 1352.43   190.7 1316.77   222.5 1297.24   266.2 1281.74   333.8 1235.34
   385.4 1193.67   401.8 1186.09   405.3  1185.7   416.8 1186.03   437.1 1190.67
     465 1186.11     477 1186.11   532.7 1188.55   588.4 1186.39   616.3 1190.76
   624.3 1193.88   640.2    1204   664.1 1225.25     684 1240.67   727.8 1270.49
   763.6 1284.64   791.5 1292.76   803.4 1298.53   815.4 1302.24   819.4 1305.03
#Mann= 3 , 0 , 0
       0      .1       0   401.8    .045       0   416.8      .1       0
Bank Sta=401.8,416.8
XS Rating Curve= 0 ,0
Exp/Cntr=0.3,0.1

Type RM Length L Ch R = 1 ,58609.7 ,273.4,271.6,267.9
XS GIS Cut Line= 3
     1750360.868      317532.802     1750768.164      317575.228
      1751175.46      317617.655
#Sta/Elev= 30
       0  1410.7    35.8  1403.2    55.7 1394.04   147.1 1346.83   194.8 1313.46
   230.6 1292.18   250.5 1282.89   262.4 1280.51   274.3 1275.26   361.8 1217.14
   385.6 1198.24   397.6 1185.05     402 1182.84     417 1183.09   429.4 1188.57
   441.3 1187.27   461.2 1188.44     485 1185.28   516.8 1187.11   532.8 1185.09
   580.5 1185.51   616.2 1182.21   624.2  1182.9   632.1 1185.89   667.9 1220.52
   675.9 1225.59   719.6 1246.02   783.2 1279.03   803.1 1286.09     819 1289.68
#Mann= 3 , 0 , 0
       0      .1       0     402    .045       0     417      .1       0
Bank Sta=402,417
XS Rating Curve= 0 ,0
Exp/Cntr=0.3,0.1

Type RM Length L Ch R = 1 ,58338.1 ,417.7,414.8,412.8
XS GIS Cut Line= 3
     1750329.001      317831.718     1750735.158      317843.444
     1751163.401       317819.56
#Sta/Elev= 30
       0 1274.78    71.7 1294.38   119.5 1312.76   139.4 1313.24   155.4 1307.58
   183.2 1292.82   207.2 1282.02     251 1266.94   314.7  1230.9   350.6 1212.75
   374.5 1196.77   394.4 1181.58   400.3 1180.22   415.3 1180.57   426.2 1184.98
   430.2 1185.02   442.1 1182.99   521.5 1182.49   537.4 1179.56   549.3 1179.32
     585 1183.17   604.9    1183   656.5 1224.97   680.4 1242.22   696.2 1250.25
     736 1264.63   771.7 1279.61   787.6 1287.82   799.5 1290.35   835.2 1311.75
#Mann= 3 , 0 , 0
       0      .1       0   400.3    .045       0   415.3      .1       0
Bank Sta=400.3,415.3
XS Rating Curve= 0 ,0
Exp/Cntr=0.3,0.1

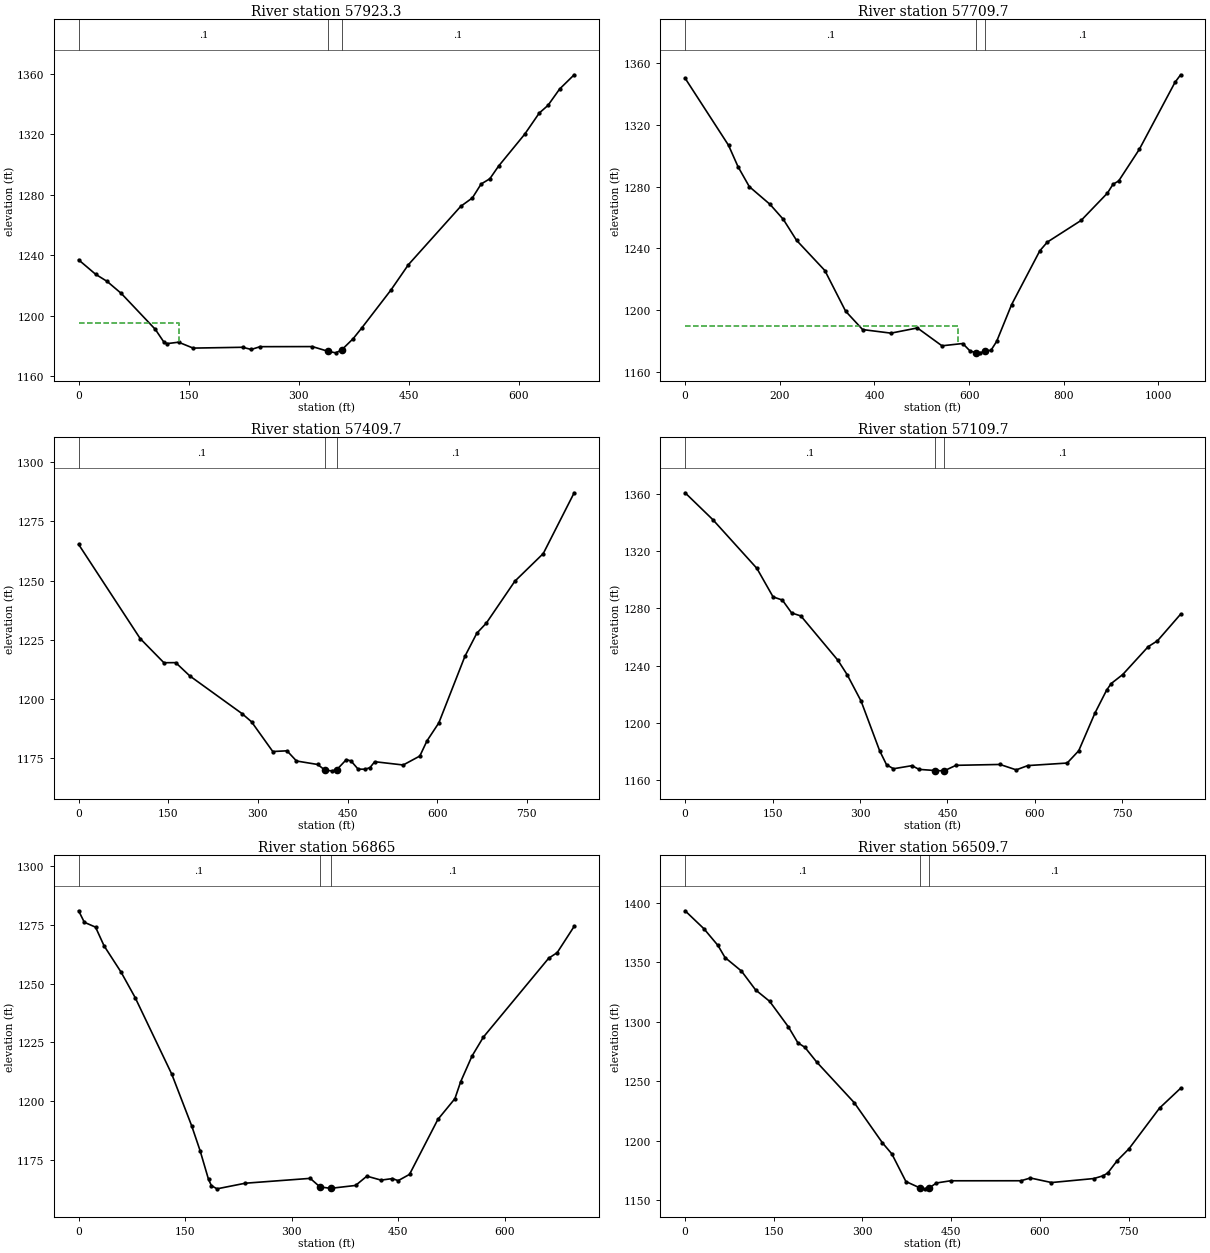
Type RM Length L Ch R = 1 ,57923.3 ,214.3,213.6,214.5
XS GIS Cut Line= 4
     1750557.207      318138.583     1750626.651      318216.708
     1750871.877      318201.517     1751195.228      318168.964
#Sta/Elev= 30
       0 1236.85    23.2 1227.28    38.7 1222.62    58.1 1214.62   104.5 1190.81
   116.4 1182.24   120.4 1181.38   136.2 1182.32     156 1178.42   223.4 1178.96
   235.3 1177.52   247.2 1179.36   318.5 1179.42     340 1176.27   350.2 1175.28
   358.2 1177.12     374 1184.63   385.9 1191.83   425.5 1216.85   449.3 1233.63
   520.6 1272.26   536.5 1277.86   548.4 1287.05   560.3 1290.55   572.2 1298.91
   607.8 1320.04   627.6 1334.03   639.5 1339.12   655.4 1349.97   675.2 1359.38
#Mann= 3 , 0 , 0
       0      .1       0     340    .045       0   358.2      .1       0
#XS Ineff= 2 , 0
          136.52 1194.94
Permanent Ineff=
       F       F
Bank Sta=340,358.2
XS Rating Curve= 0 ,0
Exp/Cntr=0.3,0.1

Type RM Length L Ch R = 1 ,57709.7 ,296.2,300,303
XS GIS Cut Line= 3
     1750214.325      318481.464     1750836.659      318410.539
     1751255.723      318376.567
#Sta/Elev= 30
       0 1350.32    91.8 1306.83   111.7 1293.05   135.6 1280.08   179.5 1268.55
   207.5 1258.85   235.4  1245.3   295.2 1225.72   339.1 1199.36     375 1187.45
   434.9 1185.14   490.7 1188.51   542.6 1176.94   586.5 1178.42   602.4 1173.43
   614.4 1172.59   622.4 1172.38   633.9 1173.44   646.2 1174.04   658.1 1179.77
   689.8 1203.68   749.3 1238.49   765.2 1244.14   836.6 1258.18   892.1 1275.86
     904 1281.62   915.9 1283.74   959.5 1304.23  1034.9 1347.66  1046.8 1352.54
#Mann= 3 , 0 , 0
       0      .1       0   614.4    .045       0   633.9      .1       0
#XS Ineff= 2 , 0
          577.28 1189.58
Permanent Ineff=
       F       F
Bank Sta=614.4,633.9
XS Rating Curve= 0 ,0
Exp/Cntr=0.3,0.1

Type RM Length L Ch R = 1 ,57409.7 ,310.7,300,289.9
XS GIS Cut Line= 3
     1750463.239      318677.558     1750882.996      318693.211
     1751291.547      318716.767
#Sta/Elev= 30
       0 1265.25     103 1225.47   142.7 1215.26   162.5  1215.3   186.2 1209.65
   273.4 1193.77   289.3 1190.32   324.9 1177.74   348.7 1178.04   364.6 1173.74
   400.2 1172.26   412.5  1169.8     424 1169.58     432 1170.06   447.9  1174.3
   455.8 1173.78   467.7  1170.3   479.6 1170.26   487.6 1170.95   495.5 1173.44
   543.2 1172.05     571 1175.84     583 1182.26   602.8 1189.84   646.5    1218
   666.4 1227.73   682.3 1232.01     730  1249.7   777.6  1261.4   829.3 1287.07
#Mann= 3 , 0 , 0
       0      .1       0   412.5    .045       0     432      .1       0
Bank Sta=412.5,432
XS Rating Curve= 0 ,0
Exp/Cntr=0.3,0.1

Type RM Length L Ch R = 1 ,57109.7 ,243.2,244.6,246.9
XS GIS Cut Line= 3
      1750520.52      319133.468     1750918.813      318954.048
     1751300.612      318796.474
#Sta/Elev= 30
       0 1360.95    47.7 1342.08   123.1 1308.04   150.9 1288.04   166.8 1285.82
   182.7 1276.81   198.6 1274.69   262.1 1243.66     278 1233.54   301.8 1215.12
   333.6 1180.38   345.5 1170.49   357.4  1167.7   389.2 1169.87   401.1 1167.27
   429.3 1166.44   444.3 1166.24   464.6  1170.1   540.1 1170.71   567.9 1166.92
   587.8 1169.92   655.3  1171.7   675.1  1180.3   702.9 1206.66   722.8 1222.63
   730.7 1227.34   750.6 1233.68   794.3 1253.21   810.2 1257.31   849.9 1275.96
#Mann= 3 , 0 , 0
       0      .1       0   429.3    .045       0   444.3      .1       0
Bank Sta=429.3,444.3
XS Rating Curve= 0 ,0
Exp/Cntr=0.3,0.1

Type RM Length L Ch R = 1 ,56865   ,351.8,355.4,358.6
XS GIS Cut Line= 3
     1750726.478      319271.395     1751056.446       319155.57
      1751392.71      319067.402
#Sta/Elev= 30
       0 1280.91       8 1276.03    23.8 1273.96    35.8 1266.02    59.6 1254.91
    79.5 1244.06   131.1 1211.49     159 1189.63   170.9 1179.04   182.8 1166.79
   186.8 1164.19   194.7 1162.81   234.5  1165.2   325.9 1167.26   339.5 1163.64
   354.5 1163.02   389.7 1164.25   405.6  1168.2   425.6 1166.51   441.6 1167.17
   449.6 1166.28   465.6 1168.95   505.5 1192.29   529.5 1201.12   537.5 1208.24
   553.5 1219.18   569.5 1227.24   661.4 1260.75   673.4 1263.13   697.3 1274.29
#Mann= 3 , 0 , 0
       0      .1       0   339.5    .045       0   354.5      .1       0
Bank Sta=339.5,354.5
XS Rating Curve= 0 ,0
Exp/Cntr=0.3,0.1

Type RM Length L Ch R = 1 ,56509.7 ,297.6,300,301.4
XS GIS Cut Line= 3
     1750545.039      319418.075     1750943.266       319343.21
     1751373.179      319293.096
#Sta/Elev= 30
       0 1393.38    31.8  1378.3    55.6 1364.21    67.5 1354.08    95.3 1342.71
   119.2 1326.86     143 1317.25   174.8 1295.69   190.7  1282.4   202.6 1278.59
   222.5 1266.24     286 1232.08   333.7 1198.29   349.6 1189.01   373.4 1165.77
   397.7 1160.27   405.2 1159.62   412.7 1160.38   425.1 1164.55   448.9 1166.39
     568 1166.42   583.9 1168.74   619.6 1164.91   691.1 1168.27     707  1170.6
   714.9 1173.03   730.8 1183.36   750.7 1193.34   802.3  1227.5     838  1244.2
#Mann= 3 , 0 , 0
       0      .1       0   397.7    .045       0   412.7      .1       0
Bank Sta=397.7,412.7
XS Rating Curve= 0 ,0
Exp/Cntr=0.3,0.1