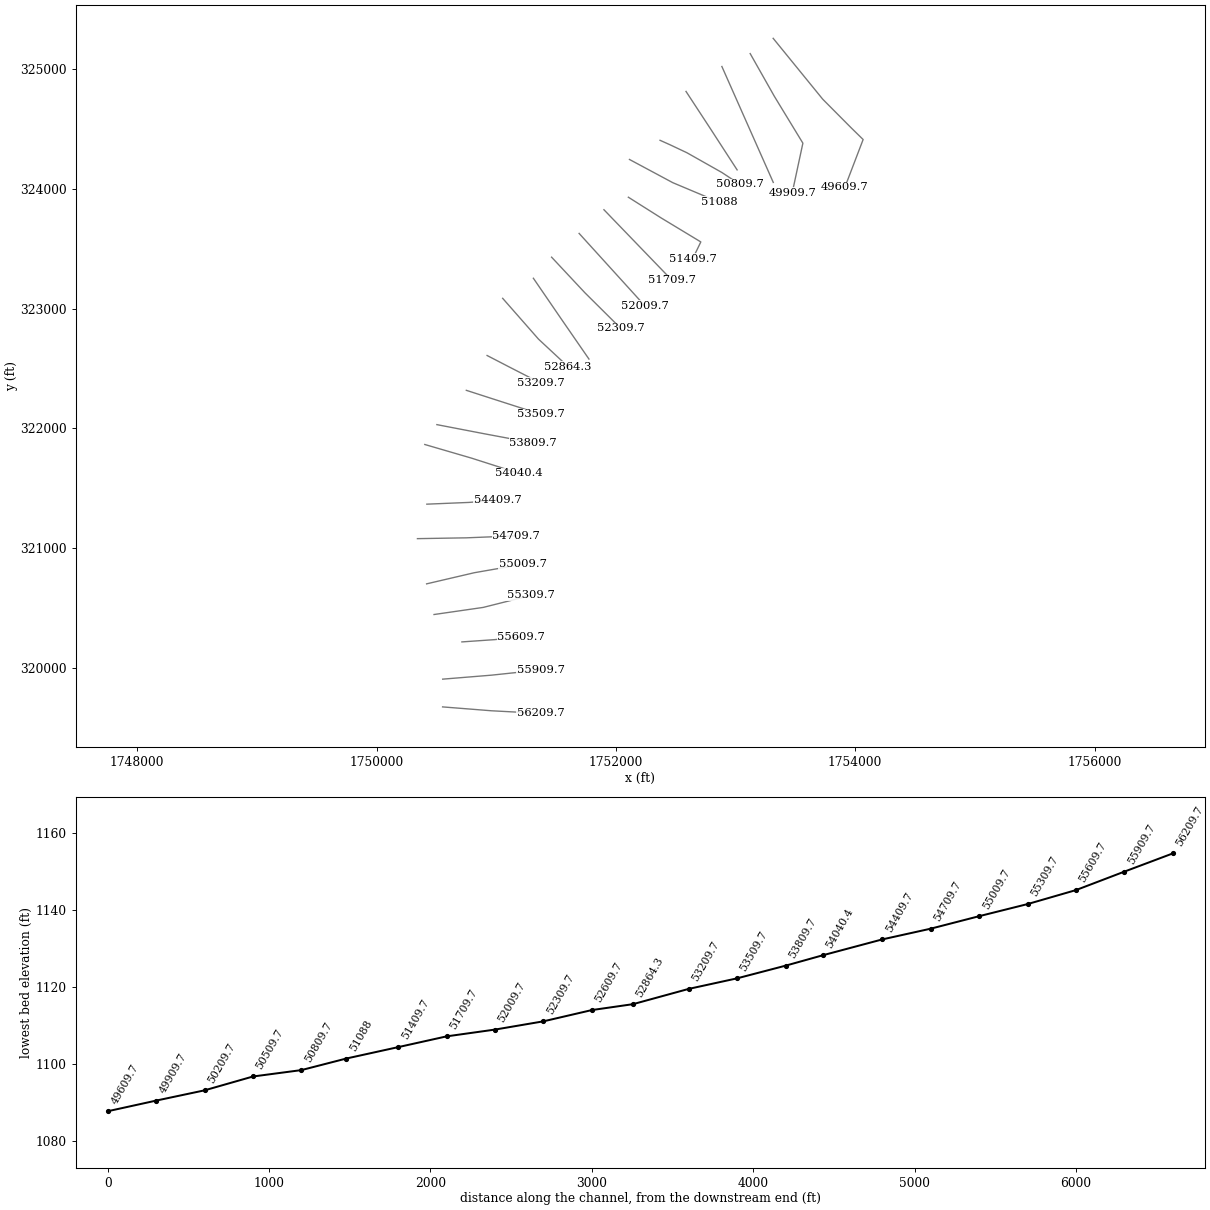
HEC-RAS study SPLAURFK.prj: SPLAURFK

--- SPLAURFK.g01 (geometry) --- (continued)

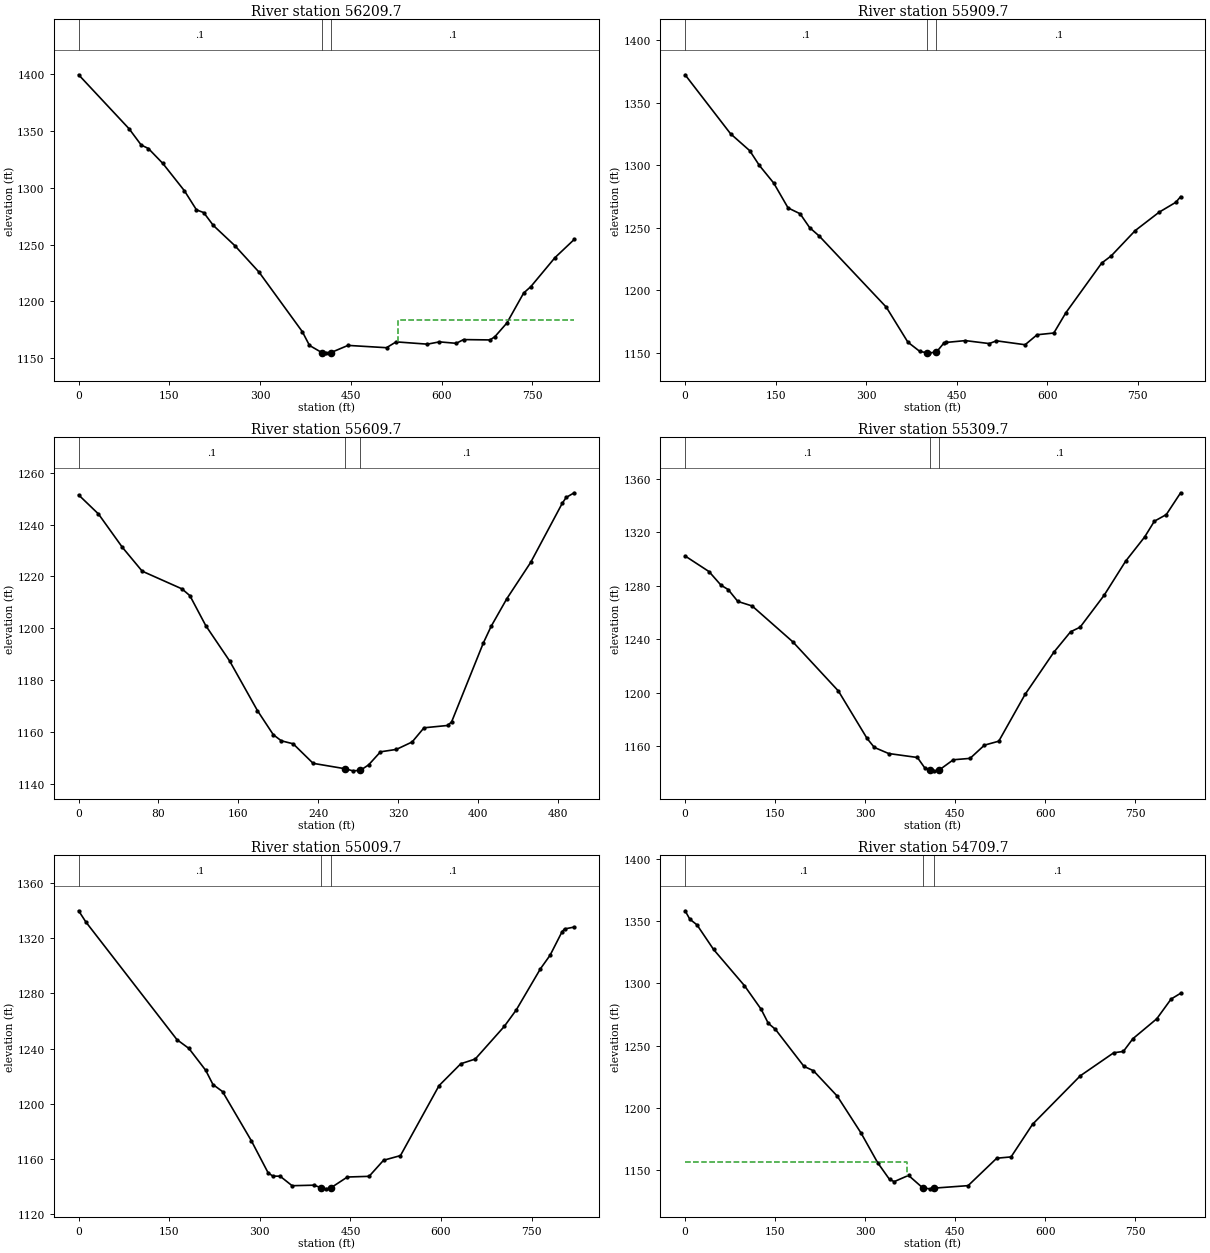
Type RM Length L Ch R = 1 ,56209.7 ,296.4,300,303.6
XS GIS Cut Line= 3
     1750552.193      319674.894     1750960.384      319642.562
     1751369.474      319620.815
#Sta/Elev= 30
       0  1399.7    83.5 1352.05   103.4 1337.79   115.3 1334.71   139.1  1321.6
   174.9 1297.42   194.8 1280.63   206.7 1278.24   222.6 1266.92   258.4 1248.99
   298.2 1225.74   369.7  1173.3   381.6 1161.12     402 1154.82   409.5  1154.6
     417 1154.83   445.3 1161.16   508.9 1159.12   524.8 1164.27   576.5 1162.25
   596.4 1164.27   624.2 1162.99   636.2 1166.28   679.9 1165.98   687.9 1168.76
   707.8 1180.85   735.6 1207.31   747.6 1213.05   787.3 1238.48   819.1 1254.52
#Mann= 3 , 0 , 0
       0      .1       0     402    .045       0     417      .1       0
#XS Ineff= 2 , 0
                          527.42         1183.33
Permanent Ineff=
       F       F
Bank Sta=402,417
XS Rating Curve= 0 ,0
Exp/Cntr=0.3,0.1

Type RM Length L Ch R = 1 ,55909.7 ,300.3,300,299.9
XS GIS Cut Line= 3
      1750552.94      319906.612     1750960.569      319939.887
     1751370.697      319983.277
#Sta/Elev= 30
       0 1372.44    75.4 1325.21   107.2 1311.66   123.1 1299.88   146.9 1285.77
   170.7 1265.87   190.6 1261.21   206.5 1250.07   222.4 1243.34   333.5 1186.43
   369.3 1158.41   389.1    1151   401.5 1149.91     405 1149.88   416.5 1150.45
   428.8 1157.61   432.8 1158.21   464.5 1159.67   504.2  1157.3   516.1  1159.5
   563.6 1156.36   583.5 1164.36   611.2 1165.75   631.1 1181.93   690.5 1221.72
   706.4 1227.51   746.1 1247.73   785.7 1262.44   813.5  1270.4   821.4 1274.92
#Mann= 3 , 0 , 0
       0      .1       0   401.5    .045       0   416.5      .1       0
Bank Sta=401.5,416.5
XS Rating Curve= 0 ,0
Exp/Cntr=0.3,0.1

Type RM Length L Ch R = 1 ,55609.7 ,297.9,300,303.3
XS GIS Cut Line= 3
     1750713.457      320217.576      1750987.59      320236.559
     1751208.249      320258.808
#Sta/Elev= 30
       0 1251.44    19.9 1244.09    43.8 1231.26    63.7 1222.05   103.5 1215.24
   111.5 1212.61   127.4 1201.07   151.3 1187.46   179.2  1168.3   195.1 1159.01
   203.1 1156.67     215 1155.51     235 1147.98   267.3 1145.88   274.8 1145.09
   282.3 1145.27   290.6 1147.39   302.5 1152.42   318.4 1153.35   334.2 1156.21
   346.1 1161.68   369.8 1162.58   373.8 1163.99   405.5 1194.31   413.4  1200.8
   429.2  1211.5     453 1225.42   484.7 1248.25   488.6 1250.47   496.6 1252.27
#Mann= 3 , 0 , 0
       0      .1       0   267.3    .045       0   282.3      .1       0
Bank Sta=267.3,282.3
XS Rating Curve= 0 ,0
Exp/Cntr=0.3,0.1

Type RM Length L Ch R = 1 ,55309.7 ,298,300,298.3
XS GIS Cut Line= 3
     1750480.624      320446.293     1750891.186      320505.531
     1751289.289      320605.576
#Sta/Elev= 30
       0 1302.23    39.9 1290.53    59.8 1280.36    71.8 1277.09    87.8 1268.22
   111.7 1264.81   179.5 1237.95   255.3  1201.2   303.1 1165.68   315.1    1159
     339 1154.42   386.9 1151.45   398.9 1143.82   407.3 1142.25   414.8 1141.46
   422.3 1141.79   446.7 1149.75   474.6 1150.78   498.5 1160.68   522.4 1163.64
   566.2 1198.64   614.1  1230.2     642  1245.5   657.9 1248.95   697.8 1272.77
   733.6 1298.28   765.5 1316.52   781.5 1328.22   801.4 1333.19   825.3 1349.51
#Mann= 3 , 0 , 0
       0      .1       0   407.3    .045       0   422.3      .1       0
Bank Sta=407.3,422.3
XS Rating Curve= 0 ,0
Exp/Cntr=0.3,0.1

Type RM Length L Ch R = 1 ,55009.7 ,304.8,300,297
XS GIS Cut Line= 3
      1750418.66      320702.351     1750816.938      320795.217
     1751222.252      320866.075
#Sta/Elev= 30
       0 1339.95    11.9 1331.88   162.8  1246.5   182.6 1240.12   210.4 1224.25
   222.4 1213.96   238.2 1208.87   285.9 1173.23   313.7 1149.94   321.6 1147.51
   333.5 1147.51   353.4 1140.59   389.1 1140.97   401.5 1139.19     409 1138.32
     417 1138.88   444.9 1146.89   480.9 1147.39   504.8 1159.04   532.8 1162.42
   596.7 1213.17   632.7 1229.02   656.6 1232.44   704.6 1256.06   724.6  1268.1
   764.5 1297.86   780.5  1307.7   800.4  1324.8   804.4 1326.76   820.4 1328.14
#Mann= 3 , 0 , 0
       0      .1       0   401.5    .045       0     417      .1       0
Bank Sta=401.5,417
XS Rating Curve= 0 ,0
Exp/Cntr=0.3,0.1

Type RM Length L Ch R = 1 ,54709.7 ,299.4,300,300.7
XS GIS Cut Line= 3
     1750341.967      321079.822     1750749.937      321086.621
     1751167.447      321103.368
#Sta/Elev= 30
       0 1358.16     7.9  1351.4    19.8 1346.87    47.5  1327.1      99 1298.05
   126.8 1279.11   138.6 1267.92   150.5 1263.06   198.1 1233.34   213.9 1229.84
   253.5 1209.52   293.2  1179.9   320.9 1156.08   340.7 1142.64   348.6 1140.88
   372.4 1145.87   396.1 1135.82     408 1135.08   415.5 1135.67   471.7 1137.65
   519.4 1159.65   543.3  1160.7   579.1 1186.88   658.7 1225.78   714.4 1244.25
   730.4  1245.3   746.3 1255.52   786.1  1271.5     810 1287.35   825.9 1291.99
#Mann= 3 , 0 , 0
       0      .1       0   396.1    .045       0   415.5      .1       0
#XS Ineff= 2 , 0
          369.14 1156.79
Permanent Ineff=
       F       F
Bank Sta=396.1,415.5
XS Rating Curve= 0 ,0
Exp/Cntr=0.3,0.1

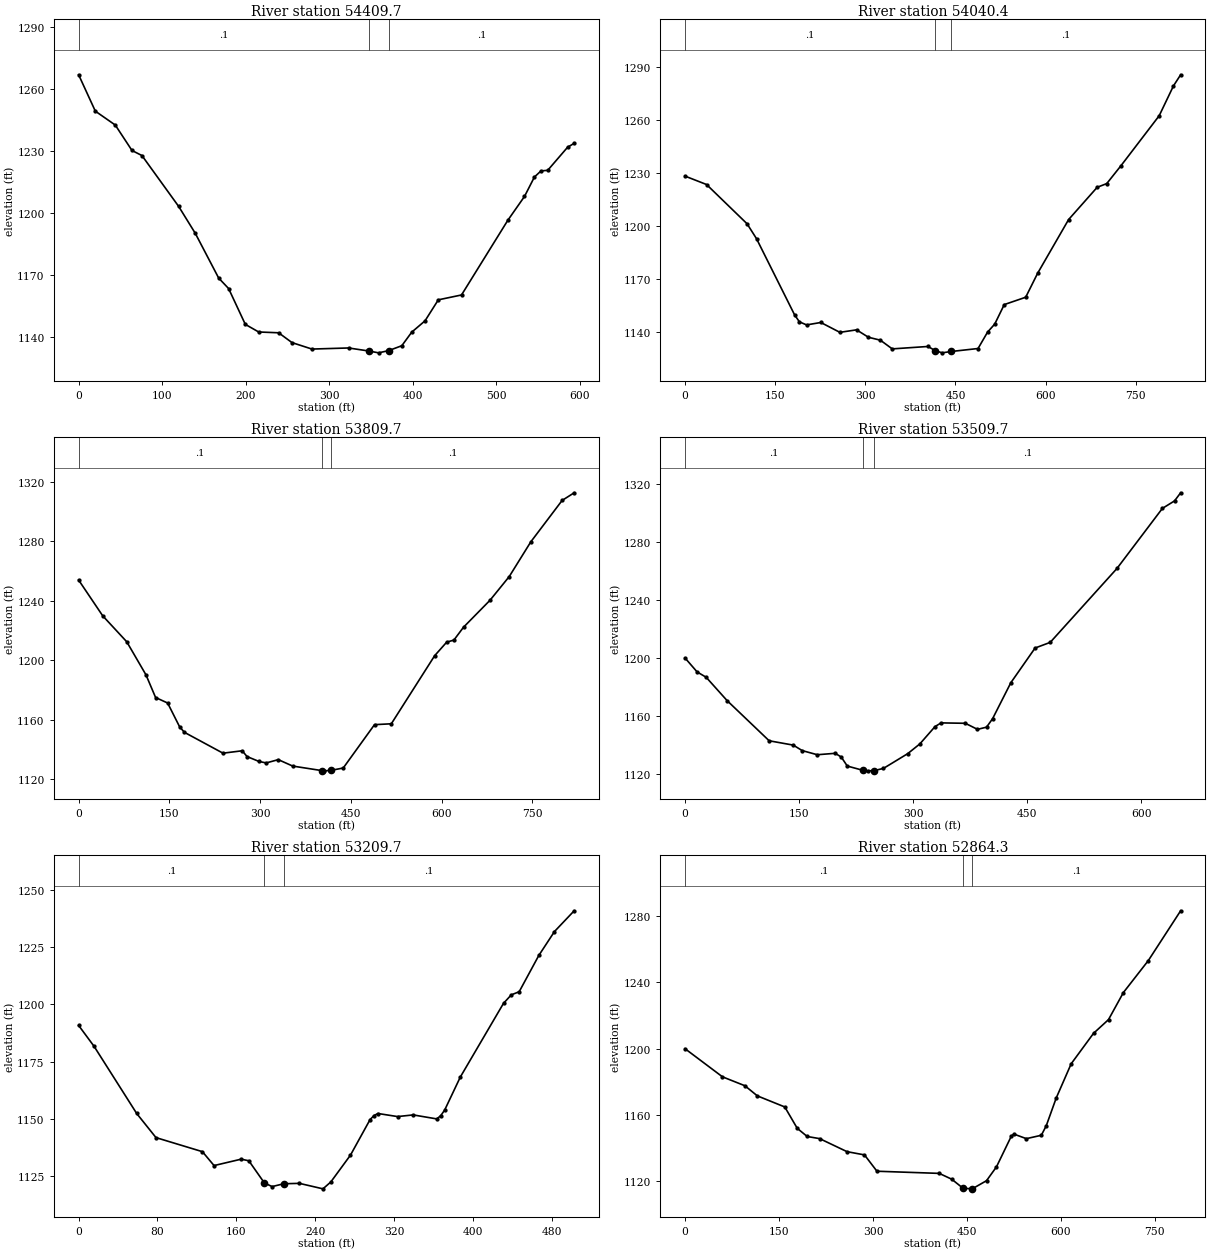
Type RM Length L Ch R = 1 ,54409.7 ,377,369.2,360.7
XS GIS Cut Line= 3
     1750420.488      321367.749     1750771.468      321382.271
     1751012.936      321400.301
#Sta/Elev= 30
       0 1267.07      20 1249.44    43.9  1242.7    63.9 1230.37    75.8 1227.93
   119.8 1203.26   139.7 1190.22   167.7 1168.54   179.6 1163.46   199.6  1146.1
   215.6 1142.41   239.5 1142.02   255.5 1137.26   279.4 1134.13   323.3 1134.66
   347.3  1133.2   359.2  1132.3   371.1 1133.36     387 1135.75   398.9 1142.33
   414.8 1147.81   430.7 1157.99   458.5 1160.35     514 1196.58   533.9 1208.09
   545.8 1217.52   553.7 1220.48   561.7 1220.76   585.5 1231.94   593.4 1233.86
#Mann= 3 , 0 , 0
       0      .1       0   347.3    .045       0   371.1      .1       0
Bank Sta=347.3,371.1
XS Rating Curve= 0 ,0
Exp/Cntr=0.3,0.1

Type RM Length L Ch R = 1 ,54040.4 ,228.2,230.8,233.4
XS GIS Cut Line= 3
     1750403.437      321865.954     1750795.368       321751.64
     1751192.097      321624.791
#Sta/Elev= 30
       0 1228.32    35.7 1223.57   103.1 1201.34   118.9 1192.86   182.3 1149.66
   190.3 1145.74   202.2 1144.01   225.9 1145.38   257.6  1139.8   285.4 1141.21
   305.2    1137     325 1135.35   344.8 1130.42   404.3 1131.79   416.2 1129.44
   427.8 1128.18   442.8 1128.94   487.6 1130.63   503.5 1139.96   515.4 1144.49
   531.2 1155.52   566.9 1159.69   586.8 1173.29   638.3  1203.7   685.9    1222
   701.8 1224.09   725.6 1234.28   789.1 1262.55   812.9 1279.49   824.8 1285.76
#Mann= 3 , 0 , 0
       0      .1       0   416.2    .045       0   442.8      .1       0
Bank Sta=416.2,442.8
XS Rating Curve= 0 ,0
Exp/Cntr=0.3,0.1

Type RM Length L Ch R = 1 ,53809.7 ,302.4,300,296.8
XS GIS Cut Line= 3
     1750504.411      322031.814     1750906.541       321954.44
     1751309.069      321879.201
#Sta/Elev= 30
       0 1253.93    39.8 1229.85    79.5 1212.39   111.3 1190.11   127.2 1174.85
   147.1 1171.14     167 1155.04   174.9 1151.39   238.6 1137.37   270.4 1138.99
   278.3  1135.1   298.2 1131.78   310.1 1130.81     330 1133.02   353.8 1128.69
     402 1125.64   405.5 1125.48     417  1125.8   437.3 1127.38     489 1156.57
   516.8 1157.16   588.4 1202.99   608.3 1212.13   620.2 1213.51   636.1 1222.17
   679.9 1240.33   711.7  1256.3   747.4  1279.7   799.1 1307.54     819 1312.69
#Mann= 3 , 0 , 0
       0      .1       0     402    .045       0     417      .1       0
Bank Sta=402,417
XS Rating Curve= 0 ,0
Exp/Cntr=0.3,0.1

Type RM Length L Ch R = 1 ,53509.7 ,303.6,300,296.2
XS GIS Cut Line= 3
     1750750.349       322318.27     1750979.764      322244.259
     1751370.989      322118.595
#Sta/Elev= 30
       0 1200.05    15.8 1190.49    27.7  1186.8    55.3 1170.66   110.6 1142.95
   142.3 1139.96   154.1 1136.17   173.9 1133.32   197.6  1134.3   205.5  1131.7
   213.4  1125.5   233.6 1122.62   241.1  1122.2   248.6 1122.33     261 1123.89
   292.9 1134.06   308.9  1140.8   328.8 1152.73   336.8  1155.3   368.7 1155.02
   384.7 1150.84   396.6 1152.34   404.6 1158.21   428.6 1183.04   460.5 1206.98
   480.4 1210.88   568.2 1261.88     628 1303.36     644 1308.55     652 1314.14
#Mann= 3 , 0 , 0
       0      .1       0   233.6    .045       0   248.6      .1       0
Bank Sta=233.6,248.6
XS Rating Curve= 0 ,0
Exp/Cntr=0.3,0.1

Type RM Length L Ch R = 1 ,53209.7 ,353.8,345.3,338.7
XS GIS Cut Line= 3
      1750923.96      322609.069     1751105.241       322515.22
     1751371.009      322379.034
#Sta/Elev= 30
       0 1190.73    15.7  1181.6    58.9 1152.33    78.5  1141.8   125.6 1135.67
   137.4 1129.61   164.9  1132.4   172.7  1131.7   188.4 1122.07   196.3 1120.44
   208.1 1121.68     224 1121.85   247.9 1119.46   255.9 1122.47   275.8 1134.15
   295.7 1149.66   299.7 1151.42   303.7 1152.32   323.6 1150.98   339.5  1151.7
   363.4 1149.96   367.4 1151.37   371.4 1153.82   387.3 1168.24   431.1 1200.37
     439 1204.07     447 1205.43   466.9 1221.24   482.8 1231.68   502.8 1240.74
#Mann= 3 , 0 , 0
       0      .1       0   188.4    .045       0   208.1      .1       0
Bank Sta=188.4,208.1
XS Rating Curve= 0 ,0
Exp/Cntr=0.3,0.1

Type RM Length L Ch R = 1 ,52864.3 ,257.4,254.7,250.1
XS GIS Cut Line= 3
     1751054.169      323086.499     1751353.648      322745.787
     1751601.044      322515.753
#Sta/Elev= 30
       0  1199.9    59.7 1182.99    95.5 1177.62   115.4 1171.51   159.2 1164.84
   179.1 1151.96     195 1147.04   214.9 1145.75   258.6  1137.9   286.5 1135.95
   306.4 1126.11   405.9 1124.81   425.8 1121.31   443.8 1115.88   457.6  1115.5
   458.8 1115.55   481.4 1120.41   497.3 1128.76   521.2 1147.41   525.2 1148.47
     545 1145.74   568.9 1147.77   576.8 1153.51   592.7 1170.24   616.6 1190.86
   652.3 1209.21   676.2 1217.47     700 1233.79   739.8 1253.05   791.4 1283.04
#Mann= 3 , 0 , 0
       0      .1       0   443.8    .045       0   458.8      .1       0
Bank Sta=443.8,458.8
XS Rating Curve= 0 ,0
Exp/Cntr=0.3,0.1

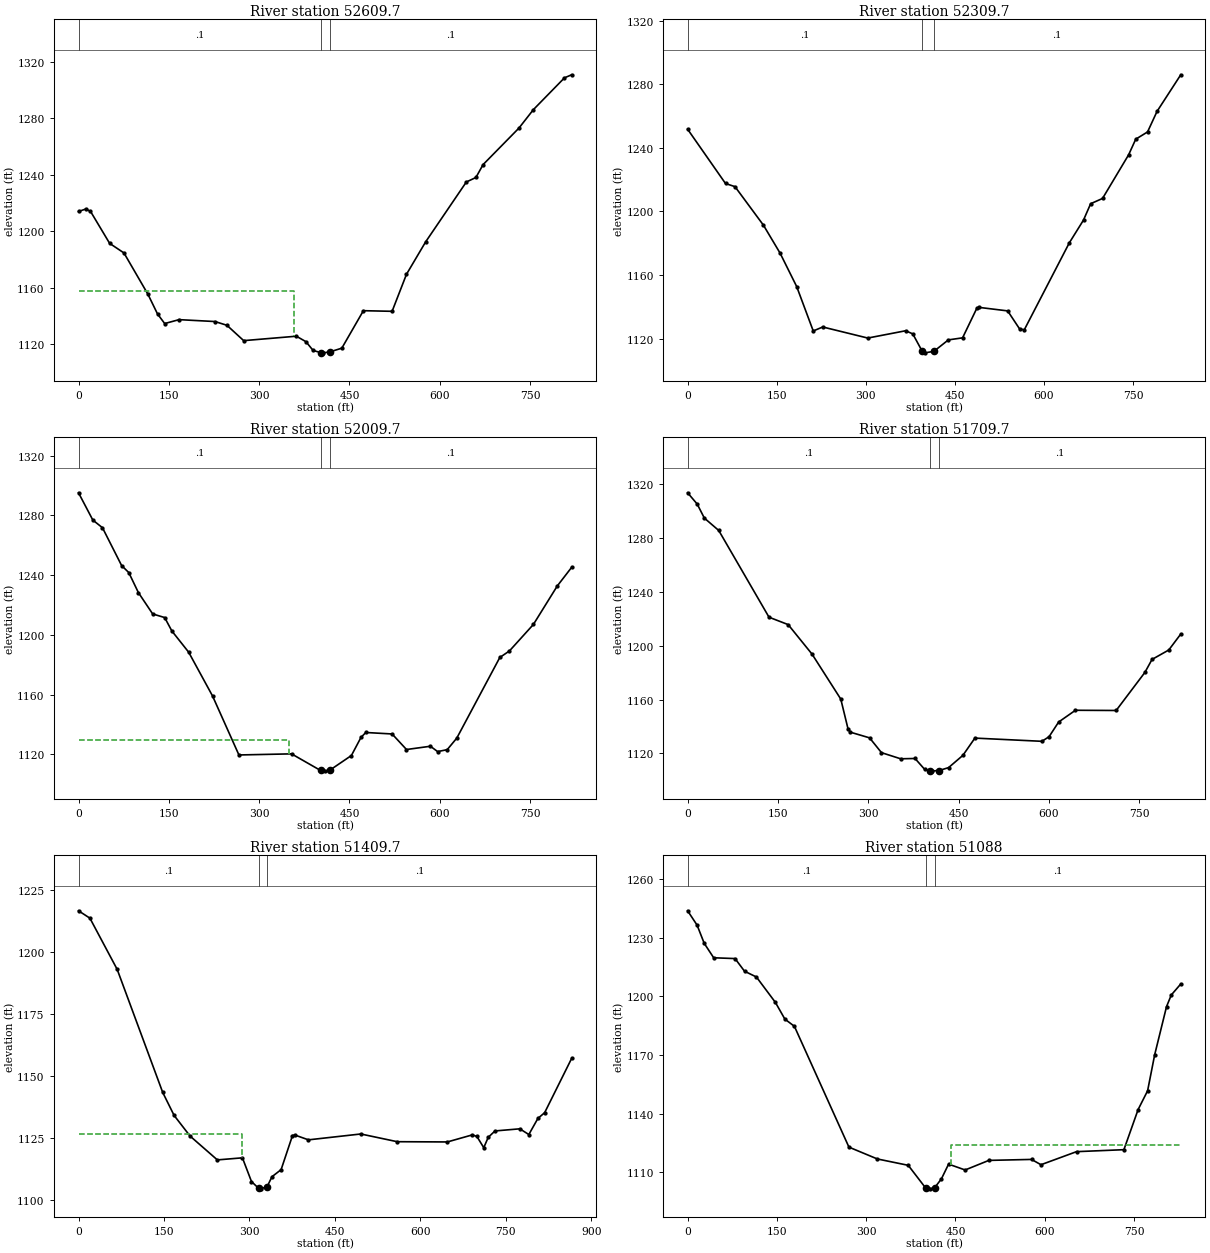
Type RM Length L Ch R = 1 ,52609.7 ,296.7,300,303.9
XS GIS Cut Line= 3
     1751310.758       323254.09     1751542.343      322916.366
     1751775.124      322579.459
#Sta/Elev= 30
       0 1213.94    11.9 1215.67    19.9 1214.05    51.7  1191.4    75.5 1184.61
   115.3  1155.4   131.2 1141.48   143.1 1134.69     167 1137.45   226.6 1136.11
   246.5 1133.45   274.3  1122.6   361.8 1125.73   377.7 1121.87   389.6 1115.67
     402 1114.15   405.5 1113.97     417 1114.58   437.3 1117.28   473.1 1143.78
   520.8 1143.34   544.7 1169.55   576.5 1192.46   644.1 1234.82     660 1237.99
   671.9 1247.11   731.5 1272.96   755.4 1285.97   807.1  1308.5     819 1310.64
#Mann= 3 , 0 , 0
       0      .1       0     402    .045       0     417      .1       0
#XS Ineff= 2 , 0
          357.83 1157.74
Permanent Ineff=
       F       F
Bank Sta=402,417
XS Rating Curve= 0 ,0
Exp/Cntr=0.3,0.1

Type RM Length L Ch R = 1 ,52309.7 ,300.3,300,298.8
XS GIS Cut Line= 3
     1751462.974       323430.13     1751741.225      323133.044
     1752041.615      322834.976
#Sta/Elev= 30
       0  1251.7    63.8 1217.56    79.8 1215.57   127.7 1191.32   155.6 1173.81
   183.6 1152.76   211.5 1124.81   227.5 1127.31   303.3 1120.35   367.1 1124.94
   379.1 1122.96   395.1 1111.94   399.1 1111.05   414.5 1111.96     439  1119.2
   462.9 1120.48   486.9 1139.11   490.9 1139.63   538.8 1137.43   558.8 1126.14
   566.7 1125.48   642.6 1180.24   666.5 1194.58   678.5 1204.84   698.5 1208.15
   742.4 1235.58   754.4 1245.43   774.3 1249.99   790.3 1262.94   830.2 1285.94
#Mann= 3 , 0 , 0
       0      .1       0   395.1    .045       0   414.5      .1       0
Bank Sta=395.1,414.5
XS Rating Curve= 0 ,0
Exp/Cntr=0.3,0.1

Type RM Length L Ch R = 1 ,52009.7 ,299.3,300,300.7
XS GIS Cut Line= 3
     1751693.047       323628.41     1751968.506      323325.405
     1752243.965      323022.399
#Sta/Elev= 30
       0 1295.12    23.8 1276.83    39.8 1271.71    71.6 1246.38    83.5 1241.68
    99.4  1228.3   123.2 1213.97   143.1 1211.56     155 1202.59   182.9 1188.39
   222.6 1159.04   266.4 1119.54   353.8 1120.28     402 1109.16   409.5 1108.91
     417 1109.25   453.2 1119.17   469.1 1131.28   477.1 1134.59   520.8  1133.6
   544.7 1123.19   584.4 1125.38   596.4  1121.8   612.3 1123.09   628.2 1130.81
   699.7 1184.84   715.6 1189.18   755.4 1206.91   795.2 1232.77     819  1245.2
#Mann= 3 , 0 , 0
       0      .1       0     402    .045       0     417      .1       0
#XS Ineff= 2 , 0
          349.92 1129.29
Permanent Ineff=
       F       F
Bank Sta=402,417
XS Rating Curve= 0 ,0
Exp/Cntr=0.3,0.1

Type RM Length L Ch R = 1 ,51709.7 ,294.5,300,305.8
XS GIS Cut Line= 3
      1751900.45      323826.169     1752184.915      323531.602
     1752469.381      323237.035
#Sta/Elev= 30
       0 1313.18    15.9 1304.84    27.8 1294.43    51.7 1285.26   135.2 1220.98
     167  1215.5   206.7  1193.6   254.4  1160.3   266.4 1138.27   270.4 1135.78
   302.2 1131.59     322 1120.62   353.8 1116.08   377.7  1116.3   393.6 1108.28
     402  1107.2   405.5 1107.15     417 1107.29   433.4 1109.54   457.2 1118.63
   477.1 1131.41   588.4 1129.03   600.3 1132.44   616.2 1143.32   644.1 1152.03
   711.7 1151.87   759.4 1180.06   771.3  1189.7   799.1 1196.69     819 1208.49
#Mann= 3 , 0 , 0
       0      .1       0     402    .045       0     417      .1       0
Bank Sta=402,417
XS Rating Curve= 0 ,0
Exp/Cntr=0.3,0.1

Type RM Length L Ch R = 1 ,51409.7 ,320,321.7,324.8
XS GIS Cut Line= 4
     1752104.516      323930.683     1752378.147      323757.897
     1752709.985      323557.419      1752642.71       323418.53
#Sta/Elev= 30
       0 1216.79      20  1213.8    67.9 1193.08   147.8 1143.34   167.8 1134.04
   195.8  1125.7   243.7 1116.06   287.7  1116.9   303.6 1107.31   316.1 1104.59
   319.6 1104.36   331.1 1105.26   339.6 1109.27   355.6 1112.12   375.6 1125.92
   379.6 1126.13   403.6 1124.17   495.5 1126.54   559.4 1123.42   647.4 1123.32
   691.3 1126.18   699.3 1125.53   711.3    1121   719.2 1125.21   731.1 1127.77
   774.6 1128.63   790.4 1126.32   806.3 1132.82   818.2 1135.16   865.6 1157.11
#Mann= 3 , 0 , 0
       0      .1       0   316.1    .045       0   331.1      .1       0
#XS Ineff= 2 , 0
          287.17 1126.71
Permanent Ineff=
       F       F
Bank Sta=316.1,331.1
XS Rating Curve= 0 ,0
Exp/Cntr=0.3,0.1

Type RM Length L Ch R = 1 ,51088   ,277.2,278.3,275.9
XS GIS Cut Line= 3
     1752113.738      324246.016      1752475.61      324052.211
     1752860.863      323890.287
#Sta/Elev= 30
       0 1243.94    15.9 1236.59    27.9 1227.26    43.8 1219.85    79.7 1219.44
    95.6 1212.96   115.6 1209.99   147.5 1196.96   163.4  1188.4   179.4 1184.71
     271 1122.78   318.8 1116.71   370.6 1113.46   399.9 1101.81   406.5  1101.4
   414.9 1101.94   426.4 1106.54   438.4 1114.07   466.2 1111.07     506 1115.98
   577.7 1116.48   593.6 1113.76   653.3 1120.46   732.9 1121.47   756.8 1142.07
   772.7 1151.66   784.6 1170.15   804.5  1194.8   812.5 1200.78   828.4 1206.41
#Mann= 3 , 0 , 0
       0      .1       0   399.9    .045       0   414.9      .1       0
#XS Ineff= 2 , 0
                          442.62         1123.81
Permanent Ineff=
       F       F
Bank Sta=399.9,414.9
XS Rating Curve= 0 ,0
Exp/Cntr=0.3,0.1

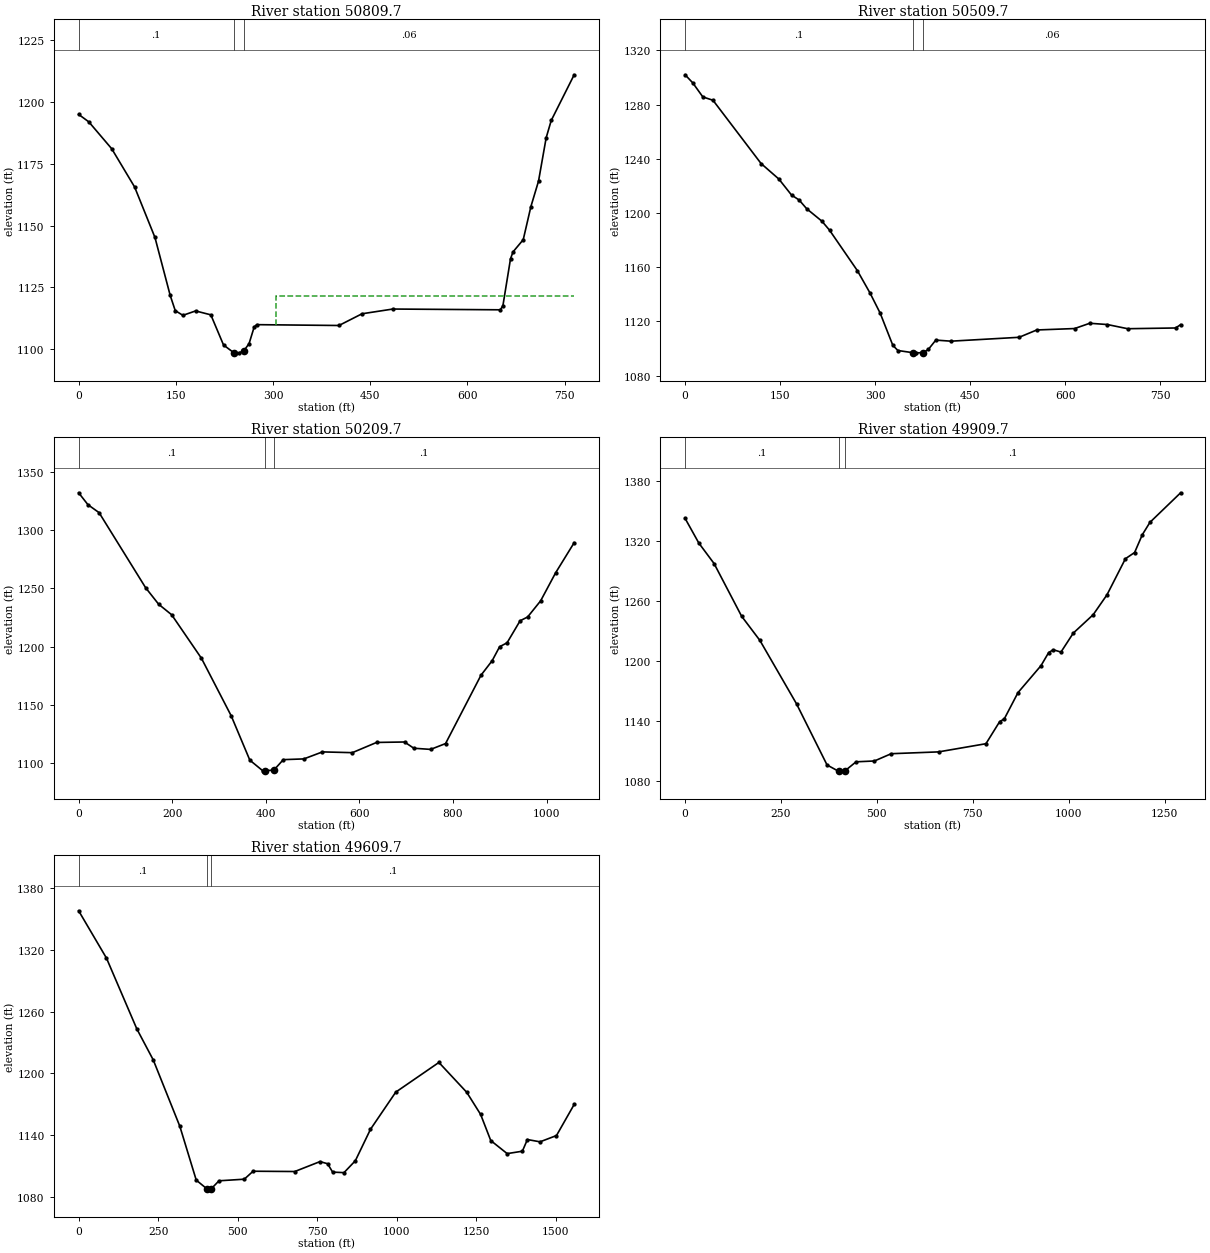
Type RM Length L Ch R = 1 ,50809.7 ,312.7,300,288.8
XS GIS Cut Line= 5
     1752369.273      324405.944     1752451.738      324369.051
     1752593.582       324302.24     1752886.871      324136.633
     1753037.676       324037.02
#Sta/Elev= 30
       0 1195.03    15.7    1192    51.1 1181.09    86.4  1165.6   117.8 1145.14
   141.3 1121.67   149.1  1115.5   160.9  1113.6   180.5 1115.38     204  1113.8
   223.6 1101.58   239.6 1098.42   247.1  1098.4   254.6 1099.12     263 1102.12
   270.9 1108.88   274.9 1109.82   401.7 1109.48   437.3 1114.23   484.9 1116.15
   650.7 1115.84   654.7 1117.46   666.5 1136.57   670.4 1139.33   686.1 1144.26
   697.9 1157.66   709.7 1167.99   721.5 1185.57   729.3 1192.57   764.7 1211.08
#Mann= 3 , 0 , 0
       0      .1       0   239.6    .045       0   254.6     .06       0
#XS Ineff= 2 , 0
                          304.35          1121.5
Permanent Ineff=
       F       F
Bank Sta=239.6,254.6
XS Rating Curve= 0 ,0
Exp/Cntr=0.3,0.1

Type RM Length L Ch R = 1 ,50509.7 ,303.7,300,296.4
XS GIS Cut Line= 3
     1752586.287       324813.93      1752787.91      324506.341
     1753013.308      324158.957
#Sta/Elev= 30
       0 1301.99      12 1296.07      28 1285.64      44 1283.18   119.9 1236.47
   147.9 1225.05   167.9 1213.24   179.9 1209.56   191.9 1203.09   215.9 1193.91
   227.9 1187.28   271.8 1157.43   291.8 1140.89   307.8 1126.04   327.8 1102.25
   335.8 1098.46   360.3 1096.78   363.8 1096.74   375.3 1096.85   383.7 1099.21
   395.6 1106.14   419.5 1105.35     527 1108.21   554.9 1113.62   614.6 1114.67
   638.5 1118.57   666.4 1117.62   698.3 1114.55   773.9 1115.09   781.9 1117.55
#Mann= 3 , 0 , 0
       0      .1       0   360.3    .045       0   375.3     .06       0
Bank Sta=360.3,375.3
XS Rating Curve= 0 ,0
Exp/Cntr=0.3,0.1

Type RM Length L Ch R = 1 ,50209.7 ,297.8,300,302.9
XS GIS Cut Line= 3
     1752885.995      325022.233     1753052.029      324647.903
     1753315.453      324054.381
#Sta/Elev= 30
       0 1332.27    19.9 1322.02    43.7 1315.18   143.1 1250.64     171 1236.41
   198.8 1227.35   262.4 1189.95     326 1140.46   365.8 1102.33   393.6 1093.15
   397.6 1093.25     417 1093.76   437.4 1102.78   481.2 1103.41     521 1109.44
   584.8 1108.78   636.6 1117.57   696.3 1117.96   716.2 1112.58   752.1 1111.59
     784  1116.6   859.7 1175.37   883.6 1187.88   899.5 1199.88   915.4 1203.24
   943.3 1222.22   959.3 1225.44   987.2 1239.38    1019 1263.33  1058.8 1289.37
#Mann= 3 , 0 , 0
       0      .1       0   397.6    .045       0     417      .1       0
Bank Sta=397.6,417
XS Rating Curve= 0 ,0
Exp/Cntr=0.3,0.1

Type RM Length L Ch R = 1 ,49909.7 ,296.2,300,303.1
XS GIS Cut Line= 4
     1753122.499      325129.977     1753324.474      324773.245
     1753562.849      324382.072     1753473.874      323967.576
#Sta/Elev= 30
       0 1342.75    35.8 1318.09    75.6 1297.61   147.3 1245.02     195 1220.82
   290.5 1157.46   370.1 1096.37     398 1090.49   402.4 1090.52   417.4 1090.68
   445.8 1099.51   493.6 1100.34   537.4 1107.61   660.9 1109.43   784.4  1117.6
   820.2  1139.7   832.2  1142.4     868 1168.69     928 1195.63     948 1208.74
     960 1211.48     980 1209.17    1012 1228.08    1064 1246.53    1100 1266.41
    1148 1302.44    1172 1308.67    1192 1326.39    1212 1338.81    1292 1368.35
#Mann= 3 , 0 , 0
       0      .1       0   402.4    .045       0   417.4      .1       0
Bank Sta=402.4,417.4
XS Rating Curve= 0 ,0
Exp/Cntr=0.3,0.1

Type RM Length L Ch R = 1 ,49609.7 ,295.8,300,301.4
XS GIS Cut Line= 6
     1753314.569      325257.403     1753573.239      324939.945
      1753728.69      324749.165     1753966.495       324510.11
     1754066.321      324412.454     1753914.412      324015.319
#Sta/Elev= 30
       0 1358.05    87.5 1312.03   182.9 1243.23   234.6 1213.02   318.1 1148.54
   369.7 1096.19     402 1088.03   405.5 1087.73     417 1087.84   441.2 1095.55
   520.6  1097.1   548.4 1104.85   679.4 1104.57   758.7 1114.22   782.5 1112.14
   798.4 1103.99   834.1 1103.48   869.8 1115.06   917.4 1145.62   996.8 1181.75
  1132.4  1210.6  1219.9 1181.58  1263.6 1160.04  1295.4 1134.68    1347 1121.98
  1394.7  1124.3  1410.6 1135.65  1450.3 1133.44    1502 1139.53  1557.6 1169.77
#Mann= 3 , 0 , 0
       0      .1       0     402    .045       0     417      .1       0
Bank Sta=402,417
XS Rating Curve= 0 ,0
Exp/Cntr=0.3,0.1