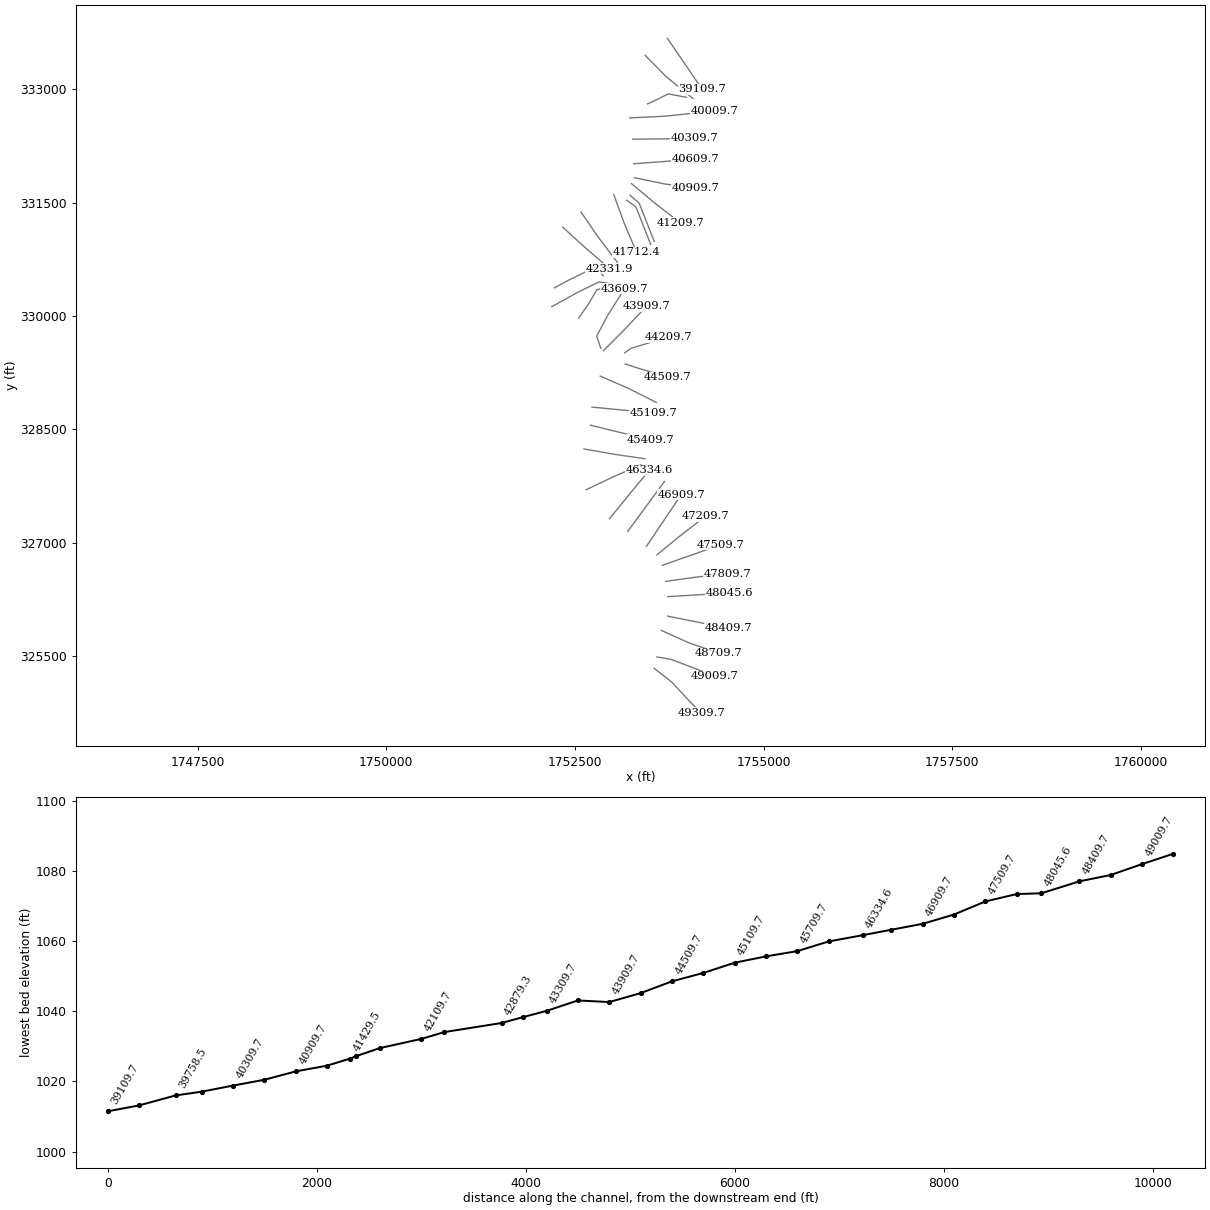
HEC-RAS study SPLAURFK.prj: SPLAURFK

--- SPLAURFK.g01 (geometry) --- (continued)

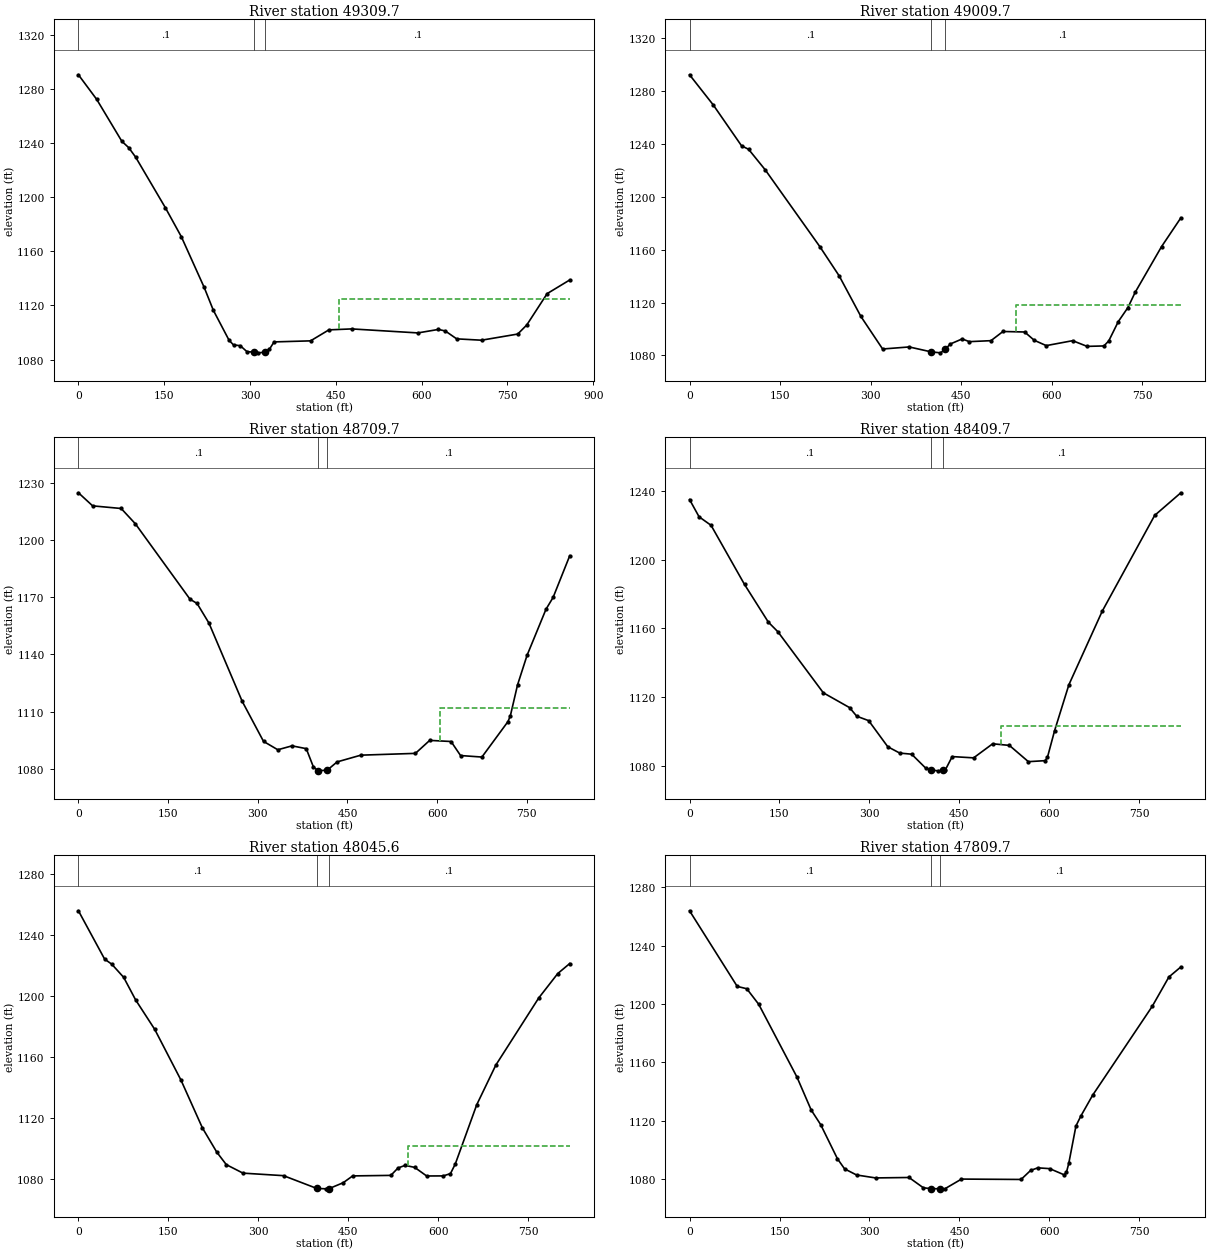
Type RM Length L Ch R = 1 ,49309.7 ,292.4,300,310.4
XS GIS Cut Line= 5
     1753550.913      325333.678     1753740.801      325187.194
     1753797.435      325139.197     1754027.184      324889.643
     1754174.828      324746.655
#Sta/Elev= 30
       0 1290.55      32 1272.34    75.9 1241.38    87.9 1236.68    99.9 1229.73
   151.9 1192.33   179.9 1170.82   219.8 1133.38   235.8 1116.46   263.3 1094.28
   271.1 1090.81   282.8 1090.27   294.5 1085.88   306.6 1085.44   314.1 1084.96
     326 1085.43     334  1087.7     342 1093.04   405.8 1093.82   437.8 1101.94
   477.7 1102.65   593.4 1099.69   629.3 1102.27   641.3 1101.12   661.2  1095.3
   704.6  1094.3   767.9 1098.85   783.7 1105.55   819.3 1128.73   858.8 1138.84
#Mann= 3 , 0 , 0
       0      .1       0   306.6    .045       0     326      .1       0
#XS Ineff= 2 , 0
                          456.19          1124.4
Permanent Ineff=
       F       F
Bank Sta=306.6,326
XS Rating Curve= 0 ,0
Exp/Cntr=0.3,0.1

Type RM Length L Ch R = 1 ,49009.7 ,301.3,300,300.9
XS GIS Cut Line= 4
     1753586.721      325484.503     1753772.268      325454.121
     1753977.644      325375.417      1754357.24      325230.479
#Sta/Elev= 30
       0 1292.42    39.2 1269.66    86.2 1238.67    97.9 1236.02   125.4 1220.51
     216 1162.33     248 1140.25     284 1109.54     320  1084.9     364 1086.46
   400.5 1082.73   415.9    1082   423.9 1084.64   431.9 1088.63   451.8 1092.52
   463.7 1090.47   499.6 1091.21   519.5 1098.16   555.4 1097.77   571.3 1091.51
   591.2 1087.47     635  1091.2   658.9 1086.89   686.8 1087.22   694.8 1091.02
   710.7 1105.71   726.6 1116.27   738.6 1127.81   782.4 1162.45   814.3 1184.15
#Mann= 3 , 0 , 0
       0      .1       0   400.5    .045       0   423.9      .1       0
#XS Ineff= 2 , 0
                          540.42         1118.45
Permanent Ineff=
       F       F
Bank Sta=400.5,423.9
XS Rating Curve= 0 ,0
Exp/Cntr=0.3,0.1

Type RM Length L Ch R = 1 ,48709.7 ,294.9,300,302.8
XS GIS Cut Line= 3
     1753646.577      325835.386       1754019.6      325667.905
     1754410.386      325534.537
#Sta/Elev= 30
       0 1224.88    23.8 1218.01    71.5 1216.63    95.3 1208.58   186.6 1169.02
   198.5 1166.76   218.3 1156.48   273.9 1115.41   309.6 1094.36   333.5 1089.96
   357.3 1092.01   381.1 1090.54     393 1080.98     401 1078.89   401.4 1078.89
   416.4 1079.31   432.7 1083.58   472.4 1087.12   563.7 1088.06   587.6 1094.88
   623.3 1094.29   639.2 1086.92   674.9 1086.13   718.6 1104.79   722.6 1107.93
   734.5 1123.99   750.4 1139.51   782.1 1163.73     794 1169.94   821.8 1191.81
#Mann= 3 , 0 , 0
       0      .1       0   401.4    .045       0   416.4      .1       0
#XS Ineff= 2 , 0
                          604.86         1112.07
Permanent Ineff=
       F       F
Bank Sta=401.4,416.4
XS Rating Curve= 0 ,0
Exp/Cntr=0.3,0.1

Type RM Length L Ch R = 1 ,48409.7 ,358.2,364,369.8
XS GIS Cut Line= 3
     1753730.301      326025.118     1754132.733      325944.335
     1754534.115       325864.06
#Sta/Elev= 30
       0 1235.07    15.9 1225.02    35.9 1220.06    91.7 1185.64   131.5 1163.67
   147.4 1158.08   223.2 1122.53     267  1113.9     279 1108.88   298.9 1106.31
   330.8  1091.1   350.7 1087.43   370.6 1086.77   394.5 1078.51     403 1077.62
   414.4 1077.08   422.4 1077.36   426.4 1077.36   438.3 1085.38     474 1084.64
   505.8 1092.84   533.7 1091.89   565.4 1082.42   593.3 1083.01   597.2 1084.95
   609.2 1100.56     633 1127.24   688.6 1170.05   776.1 1225.83   819.8 1239.01
#Mann= 3 , 0 , 0
       0      .1       0     403    .045       0   422.4      .1       0
#XS Ineff= 2 , 0
                          520.07         1103.29
Permanent Ineff=
       F       F
Bank Sta=403,422.4
XS Rating Curve= 0 ,0
Exp/Cntr=0.3,0.1

Type RM Length L Ch R = 1 ,48045.6 ,234.2,236,237.2
XS GIS Cut Line= 3
     1753730.641      326283.714     1754139.446       326307.56
     1754548.251      326331.407
#Sta/Elev= 30
       0 1256.01    43.7 1224.31    55.7 1220.95    75.5 1212.32    95.4 1197.54
   127.2 1178.25     171 1144.94   206.7 1113.62   230.6 1097.76   246.5 1089.55
   274.3 1083.97   341.9 1082.31   397.2 1073.96   413.5 1073.67   417.4 1073.75
   441.3 1077.66   457.2 1082.15   520.8 1082.49   532.8 1087.36   544.7 1089.07
   560.6 1087.72   580.5  1082.1   608.3 1082.15   620.2 1083.67   628.2 1089.93
     664 1128.82   695.8 1154.81   767.3 1198.82   799.1 1214.87     819 1221.41
#Mann= 3 , 0 , 0
       0      .1       0   397.2    .045       0   417.4      .1       0
#XS Ineff= 2 , 0
                          550.03         1102.08
Permanent Ineff=
       F       F
Bank Sta=397.2,417.4
XS Rating Curve= 0 ,0
Exp/Cntr=0.3,0.1

Type RM Length L Ch R = 1 ,47809.7 ,295.5,300,305
XS GIS Cut Line= 3
      1753707.31      326486.112     1754113.087      326542.114
     1754519.867      326589.049
#Sta/Elev= 30
       0 1263.78    79.5 1212.01    95.4 1210.42   115.3 1199.78     179 1150.02
   202.8 1127.42   218.7 1117.34   246.6 1094.01   258.5 1087.12   278.4 1082.94
   310.2 1080.92   365.9 1081.22   389.7  1074.2   402.1 1073.58   417.1  1073.5
   425.5 1073.45   453.4 1080.13   552.7 1079.87   568.6 1086.04   580.6 1087.82
   600.4 1087.28   624.3 1083.09   628.3 1084.66   632.2  1090.8   644.2 1116.44
   652.1 1123.07     672 1137.52   771.4 1198.38   799.2 1218.48   819.1 1225.33
#Mann= 3 , 0 , 0
       0      .1       0   402.1    .045       0   417.1      .1       0
Bank Sta=402.1,417.1
XS Rating Curve= 0 ,0
Exp/Cntr=0.3,0.1

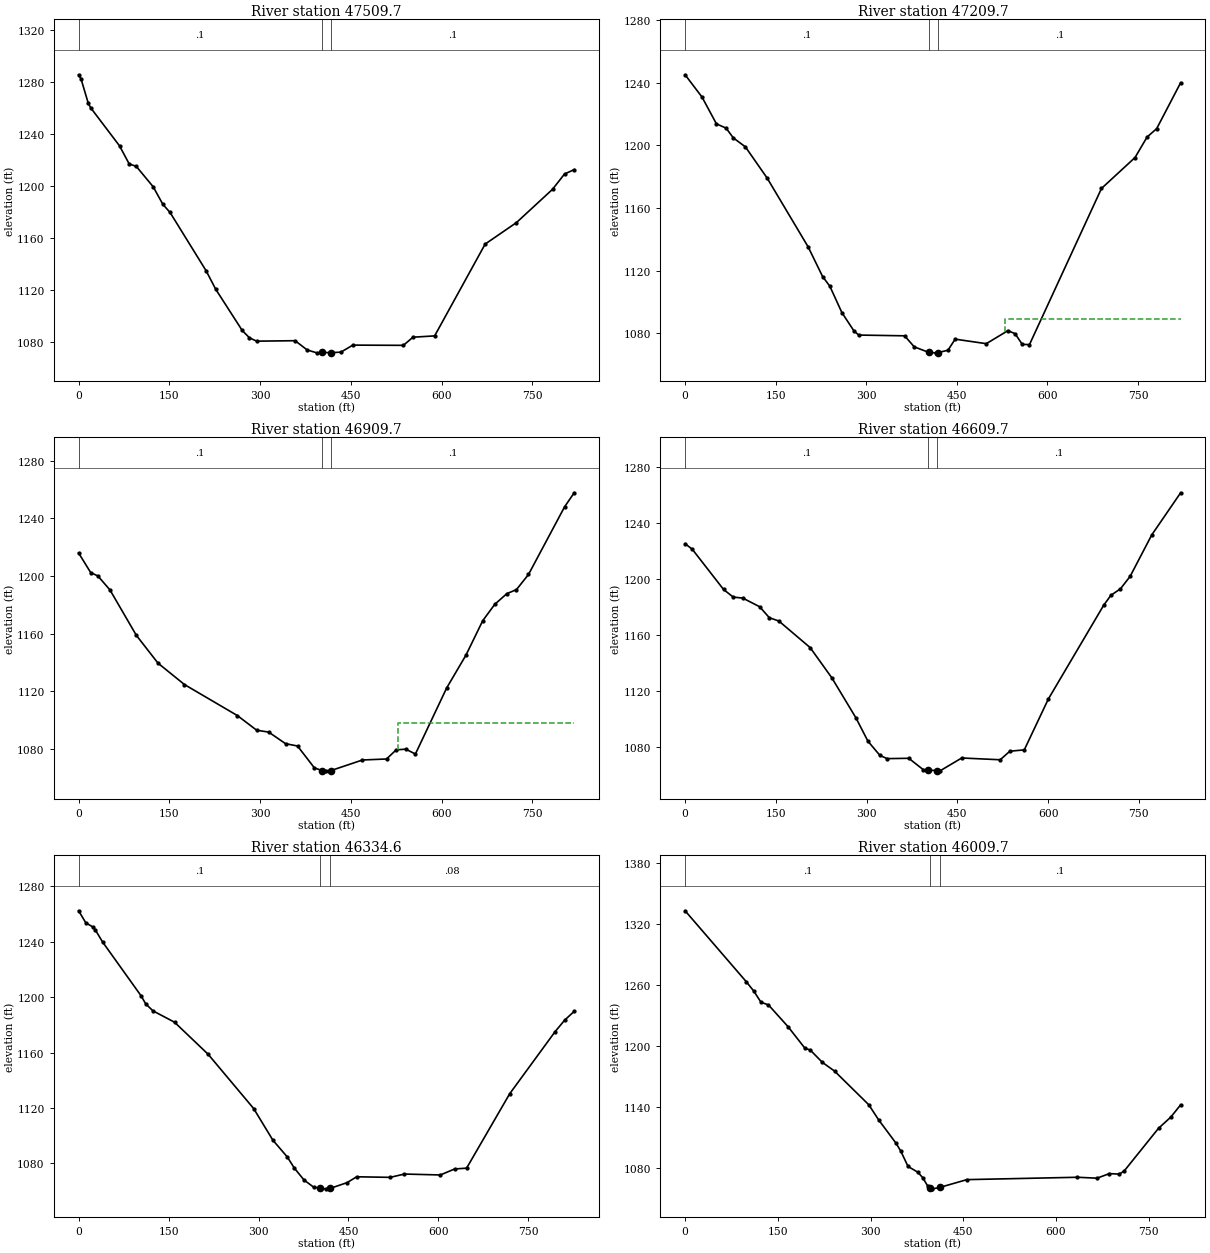
Type RM Length L Ch R = 1 ,47509.7 ,292.2,300,307.1
XS GIS Cut Line= 3
     1753658.837      326697.715     1754045.092      326833.721
     1754431.347      326969.727
#Sta/Elev= 30
       0 1285.43       4 1282.19    15.9 1263.54    19.9 1260.03    67.6  1230.7
    83.5 1216.85    95.4 1214.84   123.2 1199.21   139.2 1185.69   151.1 1179.42
   210.7 1134.52   226.6 1120.26   270.4 1088.55   282.3 1082.92   294.2 1080.33
   357.8 1080.69   377.7 1073.57   393.6 1071.34     402 1071.63     417 1071.47
   433.4 1071.87   453.2 1077.29   536.7 1077.11   552.6 1083.38   588.4 1084.39
   671.9 1155.09   723.6 1171.62   783.2 1197.24   803.1 1209.06     819 1212.39
#Mann= 3 , 0 , 0
       0      .1       0     402    .045       0     417      .1       0
Bank Sta=402,417
XS Rating Curve= 0 ,0
Exp/Cntr=0.3,0.1

Type RM Length L Ch R = 1 ,47209.7 ,293.4,300,307.3
XS GIS Cut Line= 3
     1753587.107      326836.941     1753905.971      327096.944
     1754231.232      327345.171
#Sta/Elev= 30
       0 1244.97      28 1230.77    51.9 1213.66    67.9 1210.94    79.9  1204.7
    99.9 1198.97   135.8 1179.12   203.7 1135.23   227.7 1116.28   239.7  1110.1
   259.6 1093.31   279.6 1081.59   287.6 1078.95   363.5 1078.47   379.5 1071.41
   403.9 1067.85   415.4 1067.61   418.9 1067.78   435.3 1069.27   447.2 1076.34
   498.8 1073.45   534.6 1081.78   546.5  1079.8   558.4 1072.99   570.3 1072.88
   689.5 1172.45   745.1  1192.2     765 1205.24   780.9 1210.59   820.6  1239.9
#Mann= 3 , 0 , 0
       0      .1       0   403.9    .045       0   418.9      .1       0
#XS Ineff= 2 , 0
                          530.24         1089.05
Permanent Ineff=
       F       F
Bank Sta=403.9,418.9
XS Rating Curve= 0 ,0
Exp/Cntr=0.3,0.1

Type RM Length L Ch R = 1 ,46909.7 ,300.9,300,299
XS GIS Cut Line= 3
     1753449.485      326951.335     1753678.588       327290.75
      1753907.69      327630.164
#Sta/Elev= 30
       0 1216.05    19.9 1202.51    31.8 1200.14    51.7  1190.5    95.4 1158.95
   131.2 1139.65   174.9 1124.82   262.4 1103.29   294.2 1093.15   314.1 1091.83
   341.9 1083.82   361.8 1082.18   389.6 1067.03     402 1065.19   409.5 1064.96
     417 1065.14   469.1 1072.49   508.9 1073.18   524.8  1079.5   540.7 1080.01
   556.6 1076.62   608.3 1122.47   640.1 1145.18   667.9 1169.12   687.8 1180.48
   707.7 1187.86   723.6 1190.67   743.5 1201.16   803.1 1248.04     819 1257.84
#Mann= 3 , 0 , 0
       0      .1       0     402    .045       0     417      .1       0
#XS Ineff= 2 , 0
                          527.42         1097.92
Permanent Ineff=
       F       F
Bank Sta=402,417
XS Rating Curve= 0 ,0
Exp/Cntr=0.3,0.1

Type RM Length L Ch R = 1 ,46609.7 ,276.1,275,273.8
XS GIS Cut Line= 3
     1753201.311      327148.606     1753444.494      327478.079
     1753687.676      327807.552
#Sta/Elev= 30
       0 1225.31    11.9 1221.32    63.6 1192.63    79.5 1187.22    95.4 1186.49
   123.2 1180.32   139.2 1172.51     155 1170.13   206.7 1151.17   242.5 1129.62
   282.3 1101.09   302.2  1084.4     322 1074.26     334 1071.98   369.7 1072.22
   393.6 1064.11     402 1063.83     417 1063.38   421.4 1063.27   457.2 1072.44
   520.8 1071.17   536.7 1077.26   560.6 1078.23   600.3 1114.46   691.8 1181.38
   703.7 1188.46   719.6 1193.14   735.5 1201.99   771.3  1231.6     819 1261.62
#Mann= 3 , 0 , 0
       0      .1       0     402    .045       0     417      .1       0
Bank Sta=402,417
XS Rating Curve= 0 ,0
Exp/Cntr=0.3,0.1

Type RM Length L Ch R = 1 ,46334.6 ,335.2,325,314
XS GIS Cut Line= 3
     1752959.142      327314.417     1753218.882      327634.025
     1753482.906      327953.637
#Sta/Elev= 30
       0 1262.26      12 1253.56      24 1250.52      28 1248.34      40 1239.73
     104 1201.01     112 1195.06     124 1190.07   159.9  1181.9   215.9  1158.8
   291.9 1119.62   323.9 1096.83   347.9 1084.74   359.9 1076.57   375.9 1068.07
   391.8 1062.96   402.8  1062.2   411.8 1061.71   419.8 1062.08   447.7 1066.19
   463.7 1070.41   519.5 1069.99   543.4 1072.38   603.2 1071.72   627.1 1076.04
     647 1076.63   718.8 1130.24   794.5 1175.04   810.5 1183.36   826.4 1189.71
#Mann= 3 , 0 , 0
       0      .1       0   402.8    .045       0   419.8     .08       0
Bank Sta=402.8,419.8
XS Rating Curve= 0 ,0
Exp/Cntr=0.3,0.1

Type RM Length L Ch R = 1 ,46009.7 ,314.2,300,287.2
XS GIS Cut Line= 3
     1752648.651      327698.496     1753013.903      327871.861
     1753378.604      328029.859
#Sta/Elev= 30
       0 1333.13    99.1 1263.36     111 1254.33   122.9 1243.19   134.8  1240.7
   166.5  1219.3   194.2 1197.84   202.2 1196.48     222 1184.25   241.8 1175.62
   297.3 1142.48   313.1 1127.75   340.9 1105.07   348.8 1097.23   360.7 1081.94
   376.6 1076.26   384.5 1070.88   392.4 1062.83   396.8 1060.55   400.3 1059.93
   411.8 1061.28     456 1068.98   634.8  1071.3   666.6 1070.41   686.5 1074.91
   702.4 1074.38   710.4 1077.42     766 1119.41   785.9 1130.43   801.8 1142.46
#Mann= 3 , 0 , 0
       0      .1       0   396.8    .045       0   411.8      .1       0
Bank Sta=396.8,411.8
XS Rating Curve= 0 ,0
Exp/Cntr=0.3,0.1

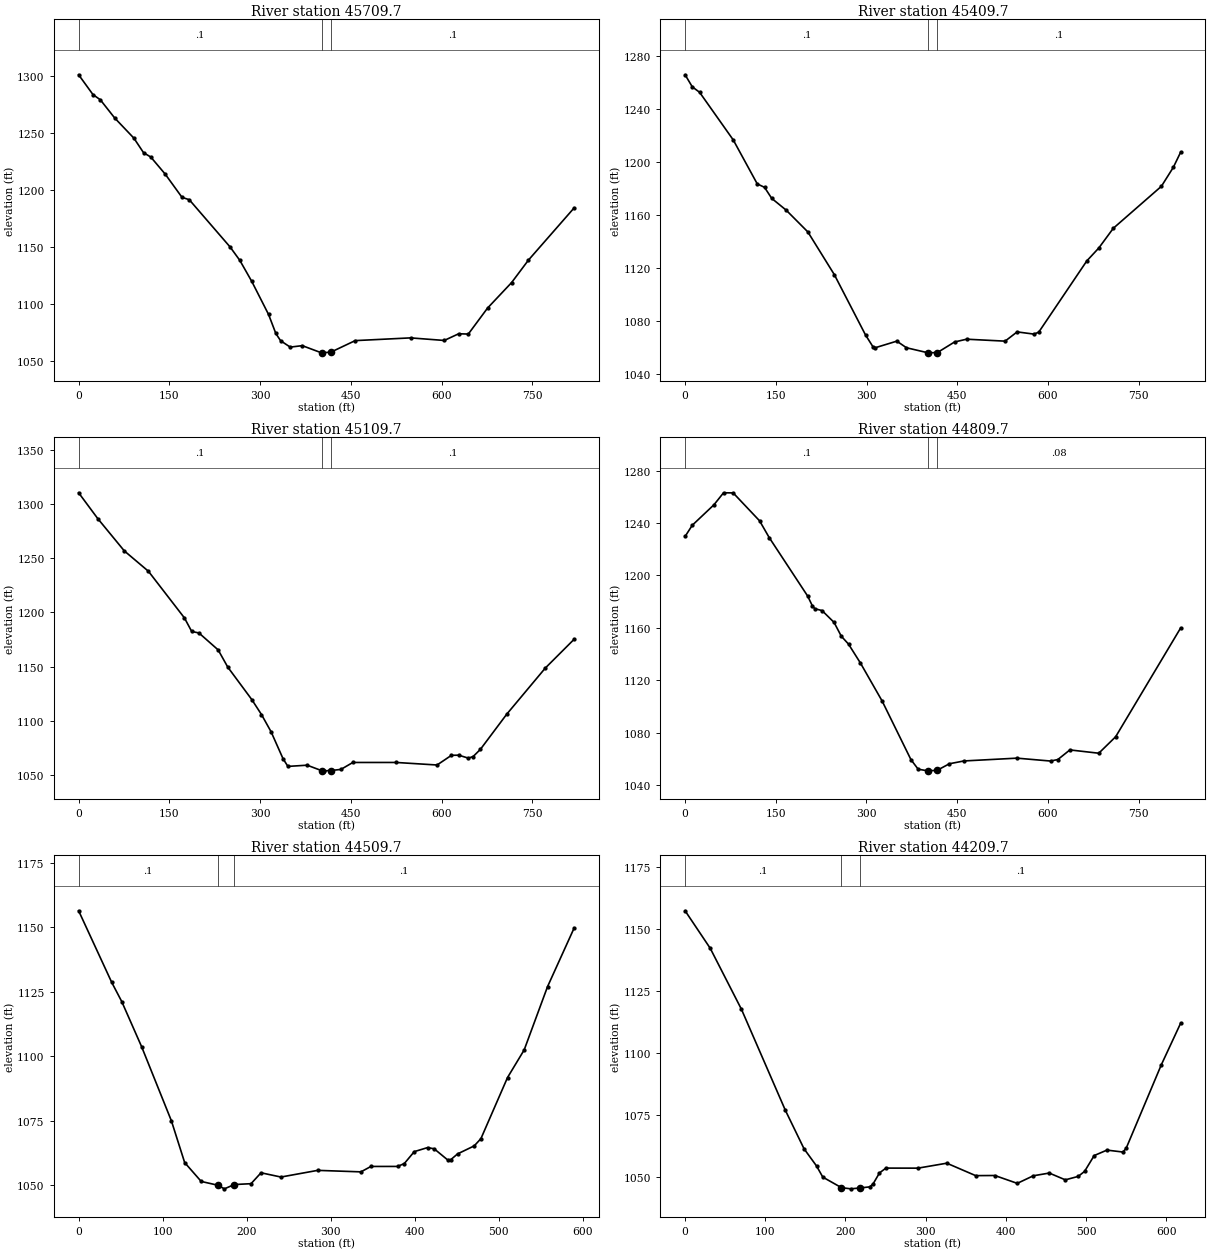
Type RM Length L Ch R = 1 ,45709.7 ,301.5,300,297.9
XS GIS Cut Line= 3
     1752621.248       328238.39     1753024.582      328167.806
     1753430.024      328108.848
#Sta/Elev= 30
       0 1300.88    23.8 1283.46    35.8 1279.01    59.6 1263.01    91.4  1245.3
   107.3 1232.59   119.3 1228.77   143.1 1213.83   170.9 1193.46   182.9 1191.38
   250.4 1149.95   266.4 1138.28   286.2 1119.79     314 1090.79     326 1074.13
   333.9 1067.78   349.8 1062.19   369.7 1063.47   401.5 1057.17     402 1057.18
     417 1057.78   457.2 1067.88   548.7 1070.28   604.4 1068.02   628.2 1073.87
   644.2 1073.64     676  1096.4   715.8 1118.78   743.6 1138.45   819.2 1184.24
#Mann= 3 , 0 , 0
       0      .1       0     402    .045       0     417      .1       0
Bank Sta=402,417
XS Rating Curve= 0 ,0
Exp/Cntr=0.3,0.1

Type RM Length L Ch R = 1 ,45409.7 ,296.8,300,303.4
XS GIS Cut Line= 3
     1752705.654      328553.487     1753103.638      328456.115
     1753501.737      328360.384
#Sta/Elev= 30
       0 1265.89    11.9 1256.75    23.9 1252.68    79.6 1216.63   119.3 1183.38
   131.3 1180.81   143.2 1172.45   167.1 1163.54   202.9  1147.1   246.6 1114.87
   298.3 1069.16   310.3 1060.43   314.2 1059.51     350 1064.51     366 1059.51
   401.8 1055.67   402.2 1055.68   417.2 1055.91   445.5 1063.89   465.4 1065.98
     529 1064.51   548.9  1071.5   576.7 1069.83   584.6 1071.29   664.1 1125.18
     684 1134.98   707.9 1149.84   787.4 1181.58   807.2 1195.99   819.2 1207.35
#Mann= 3 , 0 , 0
       0      .1       0   402.2    .045       0   417.2      .1       0
Bank Sta=402.2,417.2
XS Rating Curve= 0 ,0
Exp/Cntr=0.3,0.1

Type RM Length L Ch R = 1 ,45109.7 ,307.1,300,291.3
XS GIS Cut Line= 3
     1752727.271      328792.907     1753134.861      328753.462
     1753542.904       328718.58
#Sta/Elev= 30
       0 1310.26    31.8 1286.32    75.5 1256.66   115.3 1237.92   174.9 1194.83
   186.9 1182.37   198.8 1181.01   230.6 1165.37   246.5  1149.5   286.2 1119.57
   302.2 1105.78     318 1089.96   337.9 1064.96   345.9 1057.95   377.7 1059.07
     402 1053.96   405.5 1053.86     417 1054.17   433.4 1055.16   453.2 1061.58
   524.8 1061.59   592.4 1059.24   616.2 1068.19   628.2 1068.29   644.1 1065.58
     652 1067.04     664 1073.66   707.7  1106.2   771.3 1148.64     819 1175.22
#Mann= 3 , 0 , 0
       0      .1       0     402    .045       0     417      .1       0
Bank Sta=402,417
XS Rating Curve= 0 ,0
Exp/Cntr=0.3,0.1

Type RM Length L Ch R = 1 ,44809.7 ,297.7,300,303.9
XS GIS Cut Line= 3
     1752836.559      329203.202     1753211.879      329039.757
     1753578.357       328855.33
#Sta/Elev= 30
       0 1229.77    11.9 1238.31    47.7  1253.9    63.6 1263.07    79.5 1262.98
   123.2 1241.67   139.1  1228.9   202.7 1184.28   210.6 1176.72   214.6 1174.61
   226.5 1173.21   246.4 1164.18   258.3 1153.68   270.3 1147.61   290.1  1133.1
   325.9 1104.19   373.6 1059.43   385.5 1052.19   401.4 1050.94   401.9 1050.94
   416.9 1051.35   437.2 1056.35   461.2 1058.48   548.8 1060.62   604.5 1058.41
   616.5 1059.56   636.4  1066.9   684.2 1064.38   712.1 1076.94   819.6 1159.93
#Mann= 3 , 0 , 0
       0      .1       0   401.9    .045       0   416.9     .08       0
Bank Sta=401.9,416.9
XS Rating Curve= 0 ,0
Exp/Cntr=0.3,0.1

Type RM Length L Ch R = 1 ,44509.7 ,286.3,300,313.2
XS GIS Cut Line= 3
     1753166.799      329363.192     1753339.496      329307.785
     1753730.562      329189.966
#Sta/Elev= 30
       0 1156.49    39.4 1128.68    51.3 1121.26    74.9 1103.78   110.4 1074.96
   126.2 1058.75   145.9 1051.42   165.6 1049.96   173.5 1048.55   185.3 1050.22
   205.2 1050.55   217.1 1054.78   240.8 1053.13   284.5 1055.72     336 1055.14
   347.9 1057.24   379.6 1057.25   387.6 1058.36   399.5    1063   415.3 1064.56
   423.2 1064.09   439.1 1059.81   443.1 1059.92     451 1062.11   470.8 1065.22
   478.8 1068.03   510.5 1091.77   530.3 1102.48   558.1 1127.04   589.8 1149.83
#Mann= 3 , 0 , 0
       0      .1       0   165.6    .045       0   185.3      .1       0
Bank Sta=165.6,185.3
XS Rating Curve= 0 ,0
Exp/Cntr=0.3,0.1

Type RM Length L Ch R = 1 ,44209.7 ,288.6,300,311.8
XS GIS Cut Line= 4
     1753159.854      329510.761     1753245.846      329571.897
     1753350.277      329602.958     1753736.384      329719.962
#Sta/Elev= 30
       0  1157.4    31.3 1142.28    70.3 1117.62     125  1076.9   148.3 1061.36
   163.9 1054.42   171.7 1049.92     195 1045.66   206.7 1045.19   218.5 1045.56
   230.4 1045.99   234.4 1047.17   242.4 1051.62   250.4 1053.56   290.4 1053.54
   326.3 1055.54   362.3 1050.52   386.2 1050.57   414.2  1047.4   434.2 1050.46
   454.1 1051.56   474.1 1048.82   490.1  1050.2   498.1 1052.22   510.1 1058.62
     526 1060.82     546 1060.04     550 1061.58   593.9 1095.32   617.9 1112.02
#Mann= 3 , 0 , 0
       0      .1       0     195    .045       0   218.5      .1       0
Bank Sta=195,218.5
XS Rating Curve= 0 ,0
Exp/Cntr=0.3,0.1

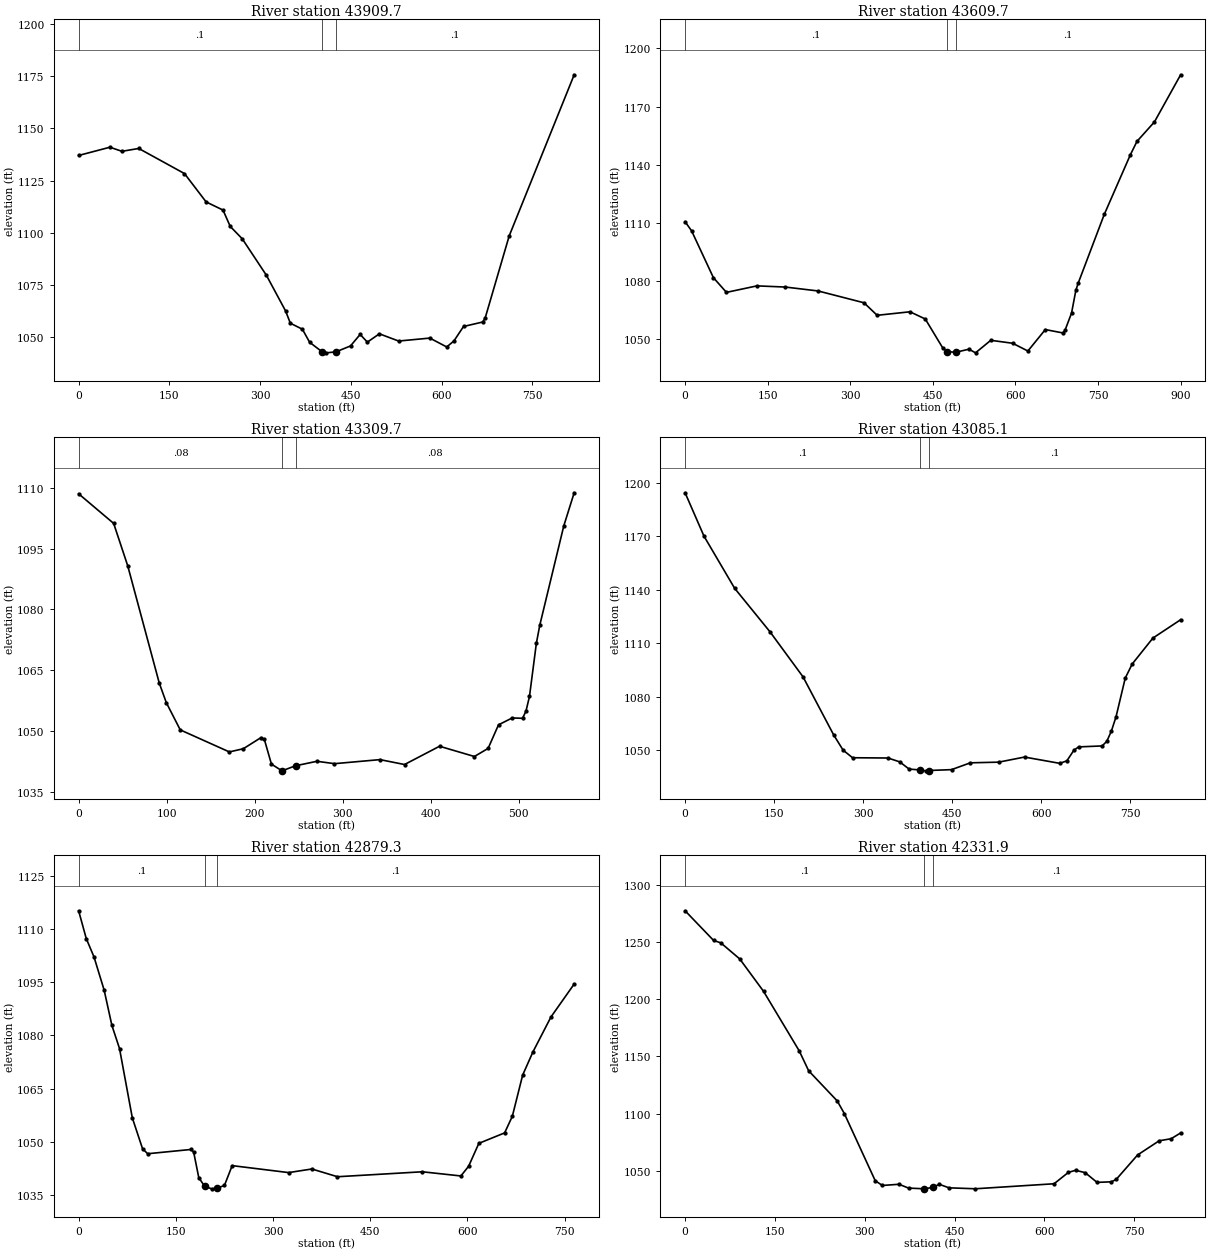
Type RM Length L Ch R = 1 ,43909.7 ,292.6,300,304.9
XS GIS Cut Line= 3
     1752878.004      329538.785     1753167.527      329828.682
     1753448.295      330126.725
#Sta/Elev= 30
       0 1136.98    51.7 1140.92    71.6 1138.97    99.4 1140.33     175 1128.32
   210.8 1114.76   238.7 1110.88   250.6 1103.08   270.5 1097.14   310.3 1079.77
   342.1 1062.68     350  1056.8   369.9 1053.93   381.9 1047.68   402.2  1043.2
   409.7 1042.64   425.6 1043.13   449.5 1045.95   465.4 1051.44   477.3 1047.76
   497.2 1051.73     529 1048.28   580.6 1049.69   608.5 1045.45   620.4 1048.31
   636.3 1055.24   668.1 1057.38   672.1 1059.31   711.8 1098.55   819.2 1175.55
#Mann= 3 , 0 , 0
       0      .1       0   402.2    .045       0   425.6      .1       0
Bank Sta=402.2,425.6
XS Rating Curve= 0 ,0
Exp/Cntr=0.3,0.1

Type RM Length L Ch R = 1 ,43609.7 ,302.9,300,300.6
XS GIS Cut Line= 4
     1752843.882      329571.525     1752789.051      329732.489
     1752936.418      330009.695     1753159.548      330361.007
#Sta/Elev= 30
       0 1110.67    11.9  1105.9    51.4 1081.84    75.1 1074.25   130.5  1077.6
     182    1077   241.6 1074.98     325 1068.89   348.9 1062.44   408.5 1064.25
   436.3 1060.54   468.1  1045.6   476.5 1043.73   491.5 1043.38   515.7 1044.98
   527.6  1043.1   555.3 1049.56     595 1048.04   622.7 1044.04   654.4 1055.09
   686.1 1053.36   690.1 1054.67     702 1063.55   709.9 1075.37   713.9 1078.84
   761.4 1114.38     809 1145.22   820.9 1152.05   852.6 1162.07   900.2 1186.36
#Mann= 3 , 0 , 0
       0      .1       0   476.5    .045       0   491.5      .1       0
Bank Sta=476.5,491.5
XS Rating Curve= 0 ,0
Exp/Cntr=0.3,0.1

Type RM Length L Ch R = 1 ,43309.7 ,235.9,224.6,210.5
XS GIS Cut Line= 4
     1752550.479      329969.095     1752685.385      330166.411
     1752788.474      330341.248     1752901.174      330385.761
#Sta/Elev= 30
       0 1108.52    39.8 1101.21    55.8 1090.74    91.6 1061.82    99.6 1056.98
   115.5 1050.23   171.3 1044.79   187.2 1045.58   207.2 1048.32   211.1 1047.87
   219.1 1041.79   231.1 1040.12   231.5 1040.15   246.5 1041.37   270.9 1042.48
   290.8 1041.89   342.5 1042.89   370.4 1041.68   410.2 1046.19   449.8 1043.66
   465.4 1045.66   477.2 1051.48   492.8 1053.18   504.5 1053.09   508.4 1054.84
   512.4 1058.48   520.2 1071.56   524.1 1076.07   551.4  1100.6   563.2 1108.77
#Mann= 3 , 0 , 0
       0     .08       0   231.5    .045       0   246.5     .08       0
Bank Sta=231.5,246.5
XS Rating Curve= 0 ,0
Exp/Cntr=0.3,0.1

Type RM Length L Ch R = 1 ,43085.1 ,206.1,205.8,205.8
XS GIS Cut Line= 4
      1752194.29      330122.081     1752545.271      330316.317
     1752819.577      330449.997     1752946.313        330430.9
#Sta/Elev= 30
       0 1194.32    31.8    1170    83.4 1140.75     143 1116.32   198.6 1091.07
   250.2  1058.5   266.1 1049.95     282  1045.7   341.6 1045.55   361.4 1043.39
   377.3 1039.33   395.2 1038.87   405.1 1038.35   410.2 1038.54   448.7 1039.02
   480.4 1042.85     528 1043.22   571.6 1046.08     631 1042.55   642.9 1043.96
   654.8 1049.95   662.7 1051.78   702.3 1052.32   710.2 1054.93   717.9 1060.68
   725.7 1068.65   741.2 1090.35   752.9 1098.26   787.8 1112.82   834.5 1123.12
#Mann= 3 , 0 , 0
       0      .1       0   395.2    .045       0   410.2      .1       0
Bank Sta=395.2,410.2
XS Rating Curve= 0 ,0
Exp/Cntr=0.3,0.1

Type RM Length L Ch R = 1 ,42879.3 ,575.4,547.3,520.6
XS GIS Cut Line= 4
     1752229.299      330371.872     1752406.382      330467.359
     1752772.702      330647.914     1752875.132      330531.595
#Sta/Elev= 30
       0 1115.24    11.8 1107.37    23.7 1102.21    39.4  1092.8    51.3 1082.86
    63.1  1076.3    82.8 1056.75    98.6 1048.01   106.5 1046.59   173.6  1047.8
   177.5 1047.04   185.4 1039.82   194.4 1037.41   205.2 1036.67   213.1  1036.8
     225 1037.64   236.9 1043.23   324.1 1041.26   359.8 1042.28   399.4 1040.09
   530.3 1041.49   589.8 1040.31   601.7 1043.04   617.5 1049.52   657.3 1052.48
   669.2 1057.18   685.1  1068.8     701 1075.37   728.8 1085.24   764.6 1094.54
#Mann= 3 , 0 , 0
       0      .1       0   194.4    .045       0   213.1      .1       0
Bank Sta=194.4,213.1
XS Rating Curve= 0 ,0
Exp/Cntr=0.3,0.1

Type RM Length L Ch R = 1 ,42331.9 ,227.6,222.3,217.7
XS GIS Cut Line= 3
     1752338.484      331175.382     1752644.229      330897.914
     1752958.466      330627.081
#Sta/Elev= 30
       0 1277.56    47.6 1251.58    59.6 1249.49    91.3 1235.37     131 1207.05
   190.6 1154.93   206.4 1137.44   254.1 1111.06     266 1099.95   317.6 1041.16
   329.5 1037.03   357.3 1038.08   373.2 1034.74   398.6 1034.14     401 1034.08
   413.6 1035.48   424.8    1038   440.8 1034.97   484.7 1034.14   616.3 1038.52
   640.2 1048.49   652.2 1050.32   668.2 1048.25   688.1 1039.73     712 1040.24
     720 1042.29   755.9 1063.78   791.8 1076.15   811.8 1077.96   827.7 1083.01
#Mann= 3 , 0 , 0
       0      .1       0   398.6    .045       0   413.6      .1       0
Bank Sta=398.6,413.6
XS Rating Curve= 0 ,0
Exp/Cntr=0.3,0.1

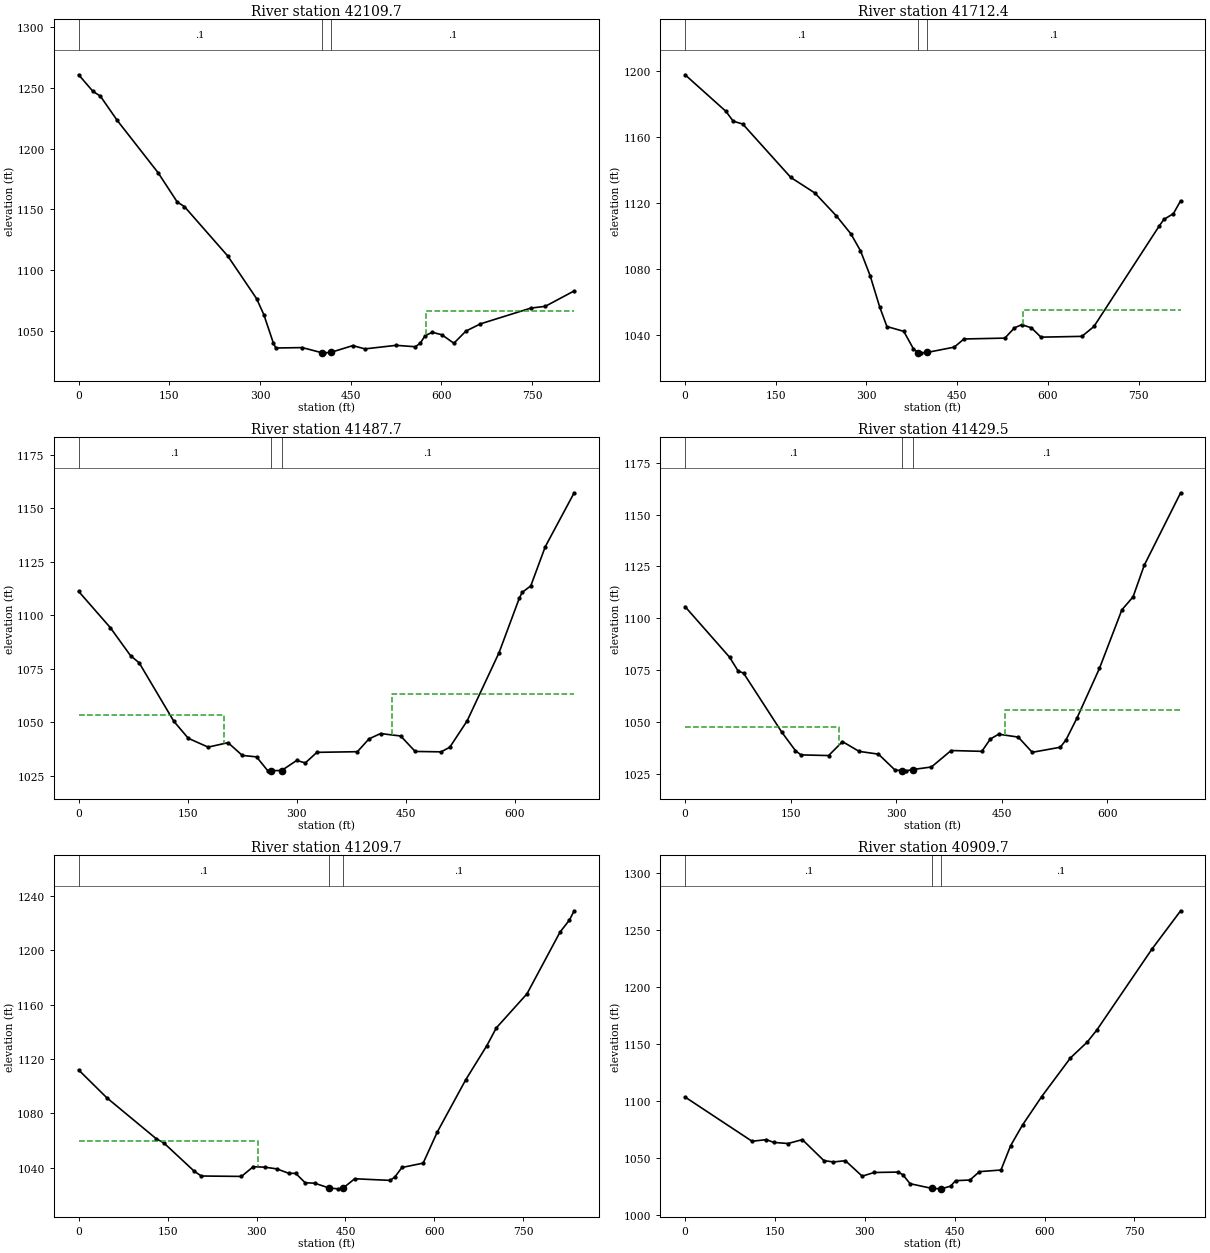
Type RM Length L Ch R = 1 ,42109.7 ,403,397.3,390.8
XS GIS Cut Line= 3
      1752582.44       331374.04      1752814.69      331036.352
     1753063.001       330710.19
#Sta/Elev= 30
       0 1260.72    23.9 1246.99    35.8 1243.27    63.7  1223.3   131.3 1180.32
   163.1 1156.16   175.1 1152.31   246.7 1111.74   294.4 1076.69   306.4 1063.51
   322.3 1039.96   326.3  1036.1     370 1036.43   402.3 1032.22   405.9 1032.12
   417.3 1032.51   453.6 1038.07   473.5 1035.36   525.3 1038.29   557.1 1037.13
   565.1    1040     573  1046.1     585 1049.04   600.9 1046.98   620.8 1040.01
   640.7    1050   664.6 1055.92   748.1  1068.9     772 1070.35   819.8 1083.04
#Mann= 3 , 0 , 0
       0      .1       0   402.3    .045       0   417.3      .1       0
#XS Ineff= 2 , 0
                          574.34         1066.43
Permanent Ineff=
       F       F
Bank Sta=402.3,417.3
XS Rating Curve= 0 ,0
Exp/Cntr=0.3,0.1

Type RM Length L Ch R = 1 ,41712.4 ,223.8,224.6,224.9
XS GIS Cut Line= 3
     1753015.804      331607.099     1753155.701      331222.381
     1753317.113      330845.198
#Sta/Elev= 30
       0 1197.56    67.6 1175.43    79.5 1169.54    95.4 1167.76   174.9 1135.48
   214.6 1126.13   250.4 1112.19   274.2 1101.41   290.1 1091.19     306 1076.18
   321.9 1057.18   333.8  1045.4   361.7 1042.48   377.6 1031.94     385 1029.65
   389.5  1029.5     400 1029.72   445.2 1032.95   461.2 1037.88   528.9  1038.4
   544.8 1044.62   556.7 1046.51   572.7 1044.64   588.6 1038.98   656.3 1039.46
   676.2 1045.42   783.8 1105.97   791.8 1110.11   807.7 1113.67   819.6 1121.42
#Mann= 3 , 0 , 0
       0      .1       0     385    .045       0     400      .1       0
#XS Ineff= 2 , 0
                          559.07         1055.57
Permanent Ineff=
       F       F
Bank Sta=385,400
XS Rating Curve= 0 ,0
Exp/Cntr=0.3,0.1

Type RM Length L Ch R = 1 ,41487.7 ,58.5,58.2,58.2
XS GIS Cut Line= 4
     1753187.632      331531.595     1753309.139      331442.343
     1753354.639      331329.778     1753503.977       330948.25
#Sta/Elev= 30
       0 1111.14    43.6 1094.18    71.4  1081.1    83.3 1077.73   130.9 1050.45
   150.8 1042.45   178.2  1038.3   205.6 1040.39   225.2 1034.43   244.8 1033.74
   260.4 1027.21   264.3  1027.3   279.3 1027.35     300 1032.05     312 1030.92
   327.9 1035.86   383.6 1036.16   399.5 1042.14   415.4 1044.65   443.2  1043.5
   463.1 1036.28   498.9 1036.09   510.8 1038.27   534.7 1050.64   578.5 1082.45
   606.3 1107.86   610.3 1110.65   622.2 1113.72   642.1 1132.02   681.9 1157.26
#Mann= 3 , 0 , 0
       0      .1       0   264.3    .045       0   279.3      .1       0
#XS Ineff= 2 , 0
          199.43 1053.33  430.92            1063
Permanent Ineff=
       F       F
Bank Sta=264.3,279.3
XS Rating Curve= 0 ,0
Exp/Cntr=0.3,0.1

Type RM Length L Ch R = 1 ,41429.5 ,208.5,219.8,232.2
XS GIS Cut Line= 5
     1753231.035      331599.303     1753298.743      331538.539
      1753349.97      331497.228     1753401.514      331369.709
     1753550.852       330988.18
#Sta/Elev= 30
       0 1105.64    63.3 1081.23    75.2 1074.69    83.1 1073.58   137.4 1045.14
   156.8 1036.23   164.6 1034.21   203.9 1033.88   223.6  1040.6   247.2  1035.9
   274.7 1034.56   298.3 1026.88   308.6 1026.64   314.2 1026.52   323.6 1027.15
     350 1028.38   377.9 1036.31   421.6 1035.91   433.6 1041.84   445.5 1044.17
   473.3 1042.78   493.2 1035.45     533 1037.89     541 1041.35   556.9 1052.07
   588.7 1075.91   620.5 1104.08   636.4 1110.35   652.3 1125.58     704  1160.5
#Mann= 3 , 0 , 0
       0      .1       0   308.6    .045       0   323.6      .1       0
#XS Ineff= 2 , 0
          217.98 1047.62  454.49         1055.81
Permanent Ineff=
       F       F
Bank Sta=308.6,323.6
XS Rating Curve= 0 ,0
Exp/Cntr=0.3,0.1

Type RM Length L Ch R = 1 ,41209.7 ,288.8,300,312
XS GIS Cut Line= 3
     1753251.796      331750.992     1753581.688      331475.492
     1753904.442      331229.324
#Sta/Elev= 30
       0 1111.98    47.8 1091.41   131.3 1061.23   143.3 1058.44     195 1037.45
   206.9 1033.94   274.6 1033.64   294.5 1040.79   314.4 1040.44   334.3 1039.18
   354.2 1035.96   366.1 1035.88     382 1028.99     398 1028.66   422.3 1025.13
   437.3  1024.5   445.7 1024.94   465.6 1031.92   525.3 1030.72   533.3 1033.21
   545.2 1040.21     581 1043.41   604.9 1066.35   652.7 1104.68   688.5 1129.94
   704.4 1142.93   756.1 1168.01   811.8  1213.4   827.8 1222.35   835.7 1229.12
#Mann= 3 , 0 , 0
       0      .1       0   422.3    .045       0   445.7      .1       0
#XS Ineff= 2 , 0
          301.87 1059.52
Permanent Ineff=
       F       F
Bank Sta=422.3,445.7
XS Rating Curve= 0 ,0
Exp/Cntr=0.3,0.1

Type RM Length L Ch R = 1 ,40909.7 ,293.7,300,304.5
XS GIS Cut Line= 3
     1753287.951       331830.06     1753698.741      331745.534
      1754103.41      331695.471
#Sta/Elev= 30
       0 1103.46   111.8 1064.63   135.8 1066.09   147.8 1063.64   171.8 1062.66
   195.7 1066.07   231.7 1047.66   247.6 1046.46   267.6 1047.58   295.6    1034
   315.6 1037.22   355.5 1037.59   363.5 1035.27   375.5  1027.4   411.9 1023.25
   426.9 1022.89   427.4 1022.87   443.4 1025.25   451.4 1030.06   475.4  1030.6
   491.4 1037.97   527.3  1039.4   543.3 1060.68   563.3 1078.97   595.3 1103.89
   643.3 1137.84   671.2 1151.69   687.2 1162.24   779.2 1233.29   827.2 1267.01
#Mann= 3 , 0 , 0
       0      .1       0   411.9    .045       0   426.9      .1       0
Bank Sta=411.9,426.9
XS Rating Curve= 0 ,0
Exp/Cntr=0.3,0.1

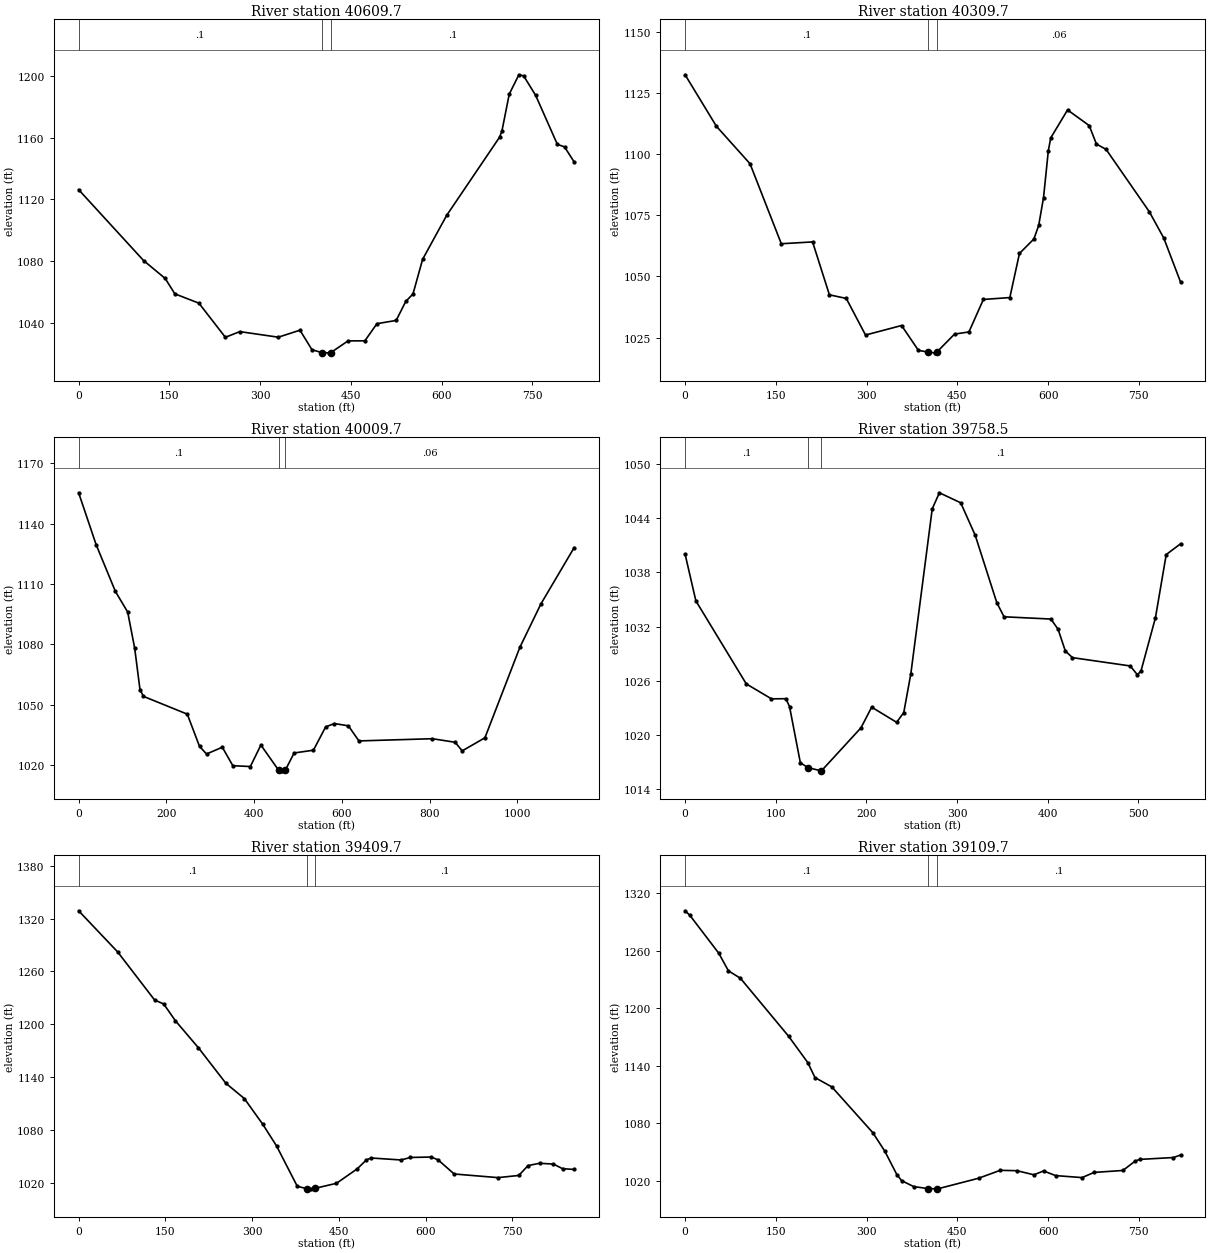
Type RM Length L Ch R = 1 ,40609.7 ,301.4,300,298.6
XS GIS Cut Line= 3
     1753281.042      332014.118     1753689.385      332044.874
     1754097.729       332075.63
#Sta/Elev= 30
       0 1126.24   107.3 1080.31   143.1 1068.68     159 1058.72   198.8 1052.67
   242.5 1030.56   266.4 1034.23     330 1030.62   365.8 1035.15   385.6 1022.52
     402  1020.6   413.5 1020.48     417 1020.69   445.3 1028.23   473.1 1028.27
     493 1039.38   524.8 1041.48   540.7 1053.82   552.6 1058.63   568.5 1081.08
   608.3 1109.59   695.8  1160.3   699.7 1164.44   711.7 1188.17   727.6  1200.7
   735.5    1200   755.4 1187.31   791.2  1155.6   803.1 1153.96     819 1144.17
#Mann= 3 , 0 , 0
       0      .1       0     402    .045       0     417      .1       0
Bank Sta=402,417
XS Rating Curve= 0 ,0
Exp/Cntr=0.3,0.1

Type RM Length L Ch R = 1 ,40309.7 ,299.2,300,302.1
XS GIS Cut Line= 3
     1753267.914      332339.139     1753677.379      332344.491
     1754086.844      332349.843
#Sta/Elev= 30
       0 1132.36    51.7 1111.35   107.3 1096.04     159 1063.37   210.7 1064.11
   238.5 1042.51   266.4 1041.03   298.2 1026.09   357.8 1029.98   385.6 1019.84
     402 1019.09   413.5 1018.82     417 1019.36   445.3 1026.47   469.1 1027.35
     493 1040.62   536.7 1041.39   552.6  1059.4   576.5 1065.32   584.4 1070.84
   592.4 1082.21   600.3  1101.3   604.3 1106.57   632.1 1118.01   667.9 1111.61
   679.8 1104.07   695.8  1101.9   767.3 1076.41   791.2 1065.65     819 1047.63
#Mann= 3 , 0 , 0
       0      .1       0     402    .045       0     417     .06       0
Bank Sta=402,417
XS Rating Curve= 0 ,0
Exp/Cntr=0.3,0.1

Type RM Length L Ch R = 1 ,40009.7 ,241.8,251.1,260
XS GIS Cut Line= 3
     1753227.563      332621.872     1753690.216      332643.845
     1754352.563      332713.886
#Sta/Elev= 30
       0 1155.38    39.9 1129.56    83.8  1106.3   111.8 1096.04   127.8 1077.97
   139.8 1057.53   147.7 1054.12   247.6 1045.27   275.5 1029.23   291.5 1025.46
   327.4 1028.83   351.4 1019.63   391.3 1019.22   415.3 1029.91   455.7  1017.4
   463.2 1017.08   470.7 1017.29   491.1 1025.97     535 1027.34   562.9 1038.94
   582.8  1040.6   614.7 1039.47   638.7 1031.96   806.2 1033.06     858 1031.29
     874 1027.01   925.8 1033.51  1005.6 1078.59  1053.4 1100.09  1129.2 1128.12
#Mann= 3 , 0 , 0
       0      .1       0   455.7    .045       0   470.7     .06       0
Bank Sta=455.7,470.7
XS Rating Curve= 0 ,0
Exp/Cntr=0.3,0.1

Type RM Length L Ch R = 1 ,39758.5 ,377,348.9,322.4
XS GIS Cut Line= 4
     1753464.079      332807.187     1753593.919      332866.964
     1753737.517      332939.999     1753975.798      332894.426
#Sta/Elev= 30
       0 1040.02    11.9 1034.84    67.5 1025.64    95.3 1023.98   111.2    1024
   115.2 1023.12   127.1 1016.91   135.4 1016.35   150.4    1016     194 1020.77
   205.8 1023.06   233.3 1021.38   241.2 1022.46     249 1026.76   272.6 1045.05
   280.5 1046.83     304 1045.72     320 1042.12   343.8 1034.65   351.8 1033.08
   403.5 1032.83   411.4  1031.7   419.4 1029.29   427.3 1028.55     491 1027.63
   498.9 1026.65   502.9 1027.08   518.8 1032.97   530.7 1039.98   546.6 1041.18
#Mann= 3 , 0 , 0
       0      .1       0   135.4    .045       0   150.4      .1       0
Bank Sta=135.4,150.4
XS Rating Curve= 0 ,0
Exp/Cntr=0.3,0.1

Type RM Length L Ch R = 1 ,39409.7 ,304,300,293.4
XS GIS Cut Line= 3
     1753430.696      333451.815     1753712.395      333165.086
     1754066.104      332878.817
#Sta/Elev= 30
       0  1328.9    67.7 1282.02   131.3 1227.64   147.2 1223.01   167.2 1204.16
     207 1173.47   254.7 1132.99   286.5 1115.74   318.4 1086.51   342.3 1061.86
   378.1 1016.09   394.5  1013.3     402 1013.16   409.5 1013.84   445.9 1019.42
   481.8 1035.88   497.8 1046.07   505.7 1048.19   557.6 1045.94   573.6 1048.78
   609.5 1049.28   621.5 1046.15   649.4 1030.02   725.3  1025.9   761.2 1028.36
   777.2 1039.54   797.1 1042.19   821.1 1041.28     837 1036.03     857  1035.2
#Mann= 3 , 0 , 0
       0      .1       0   394.5    .045       0   409.5      .1       0
Bank Sta=394.5,409.5
XS Rating Curve= 0 ,0
Exp/Cntr=0.3,0.1

Type RM Length L Ch R = 1 ,39109.7 ,297.6,300,302.6
XS GIS Cut Line= 3
     1753726.153      333675.544     1753957.189      333337.442
     1754188.225      332999.341
#Sta/Elev= 30
       0 1301.53       8 1296.68    55.7 1257.22    71.6 1238.89    91.4 1231.16
     171 1170.71   202.8 1143.14   214.7 1127.51   242.5 1117.83   310.1 1070.17
     330 1050.86   349.9 1026.39   357.8 1020.04   377.7 1013.86     402 1011.69
     417 1011.49   417.4 1011.48     485 1022.52   520.8  1030.8   548.6 1030.38
   576.5 1026.12   592.4 1030.15   612.3  1025.3     656  1023.2   675.9 1028.61
   723.6 1030.64   743.5  1040.3   751.4  1042.2   807.1 1044.13     819 1046.78
#Mann= 3 , 0 , 0
       0      .1       0     402    .045       0     417      .1       0
Bank Sta=402,417
XS Rating Curve= 0 ,0
Exp/Cntr=0.3,0.1