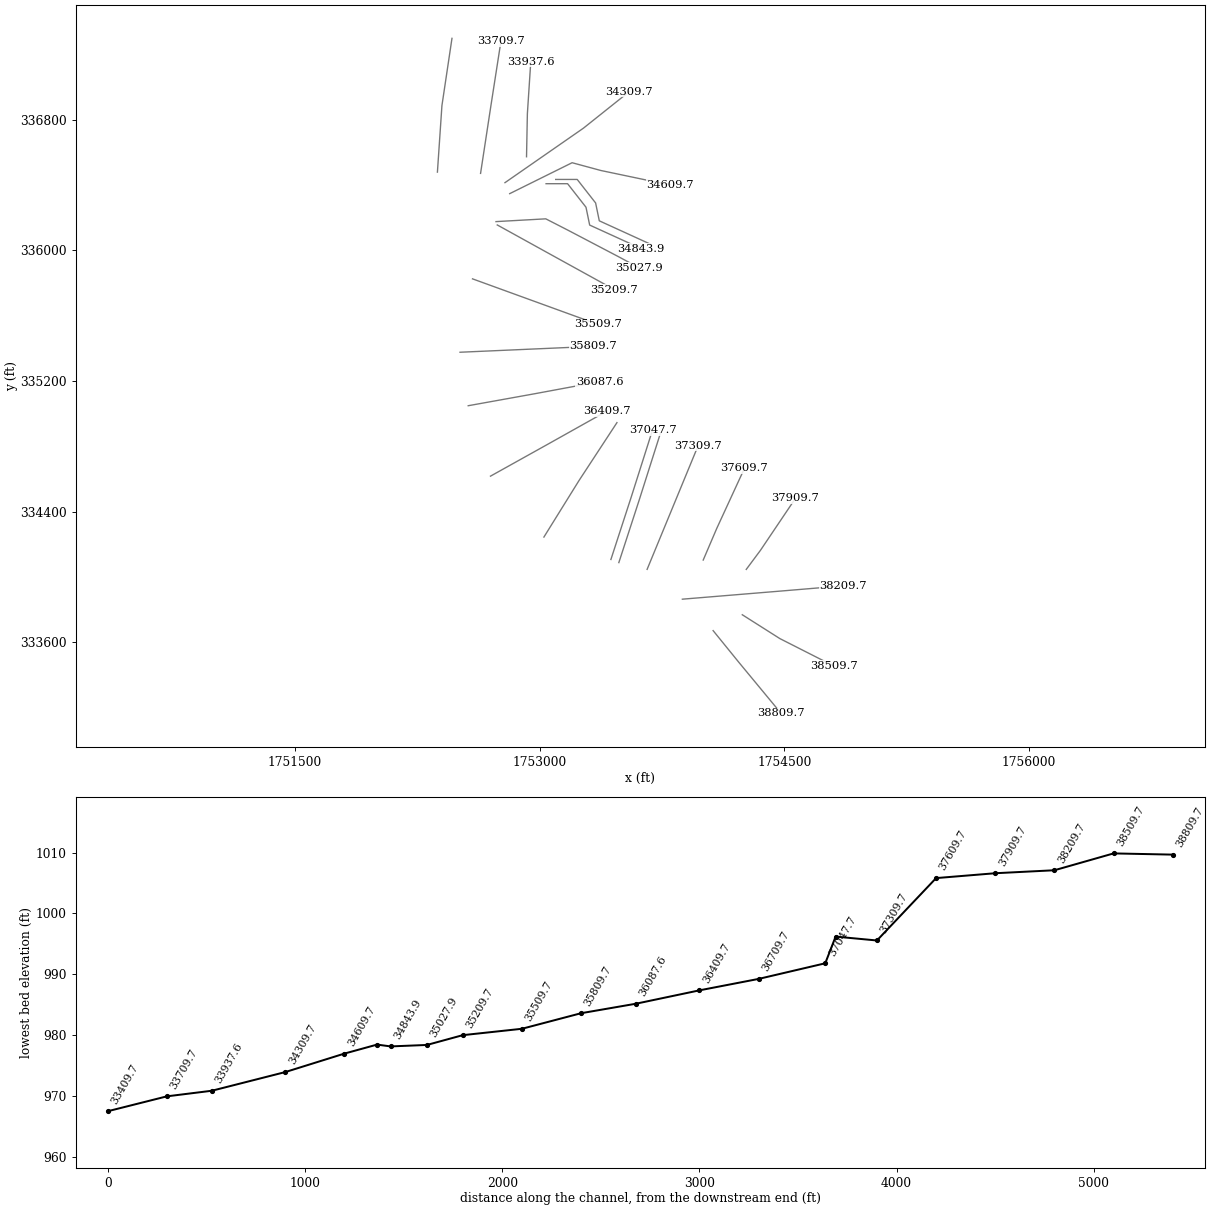
HEC-RAS study SPLAURFK.prj: SPLAURFK

--- SPLAURFK.g01 (geometry) --- (continued)

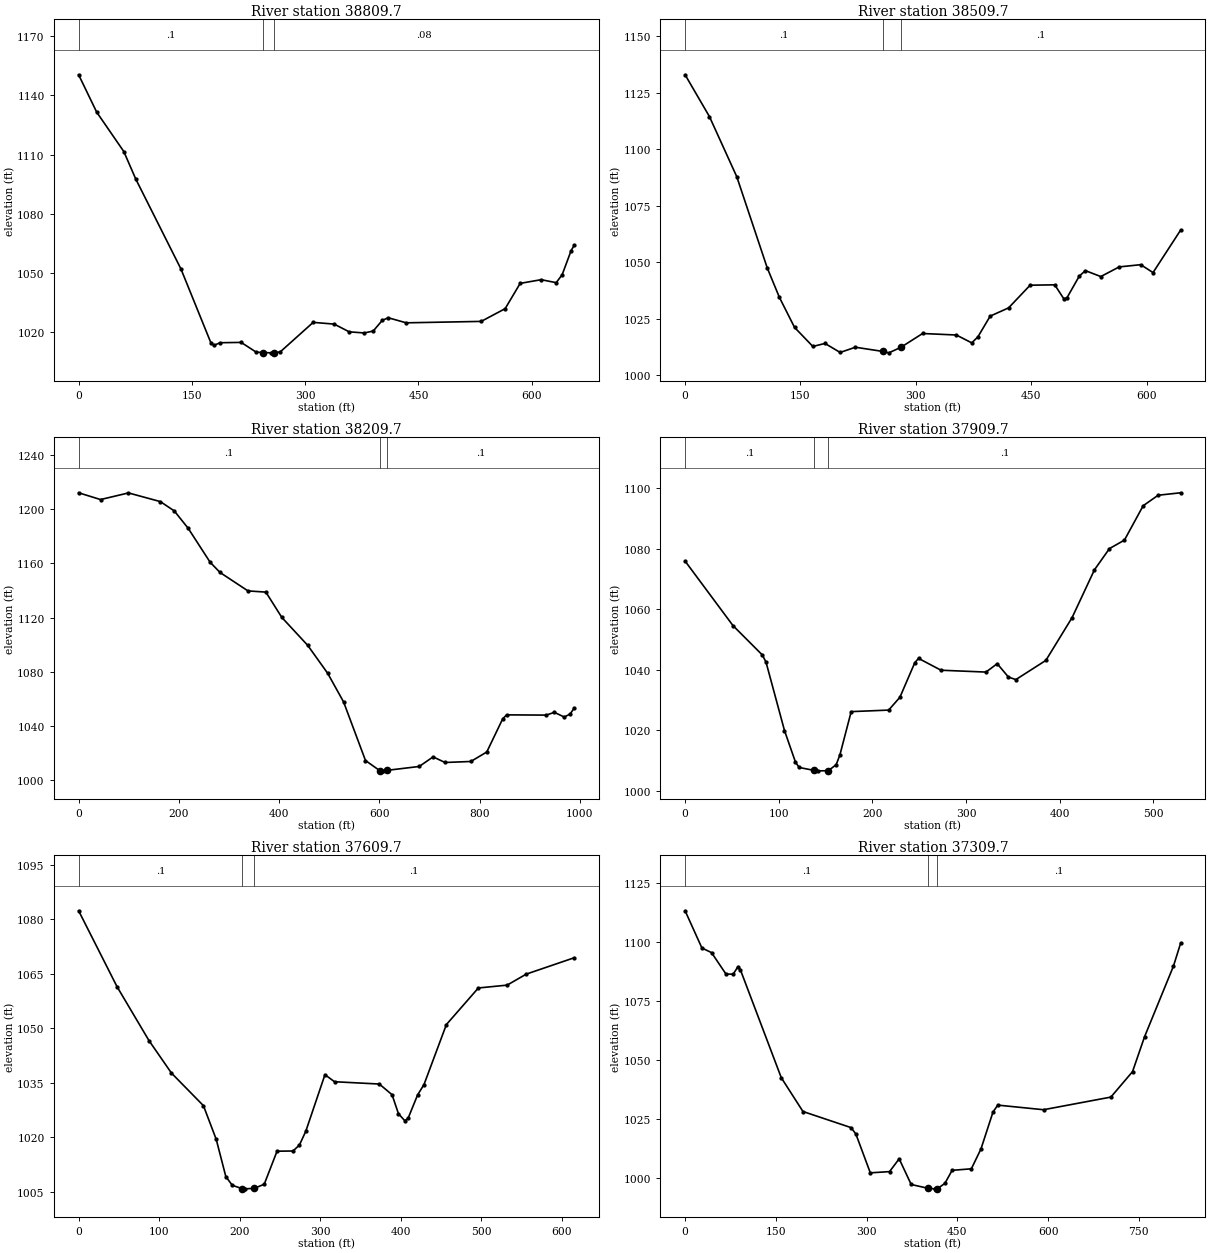
Type RM Length L Ch R = 1 ,38809.7 ,293,300,308.9
XS GIS Cut Line= 3
     1754062.632      333670.484      1754220.91      333475.626
     1754479.299      333163.539
#Sta/Elev= 30
       0 1150.39    23.9 1131.49    59.8 1111.56    75.7 1097.59   135.5 1052.11
   175.3  1014.6   179.3 1013.48   187.3  1014.8   215.2 1014.96   235.1 1010.04
   243.5 1009.85     255 1009.68   258.5 1009.75   266.9 1010.13   310.6  1025.1
   338.4 1024.22   358.3 1020.31   378.2 1019.74   390.1 1020.71     402 1026.08
   409.9 1027.44   433.8 1024.87   533.1 1025.59   564.8 1032.04   584.7 1044.83
   612.5  1046.7   632.4 1045.19   640.3 1049.22   652.2 1061.45   656.2 1064.07
#Mann= 3 , 0 , 0
       0      .1       0   243.5    .045       0   258.5     .08       0
Bank Sta=243.5,258.5
XS Rating Curve= 0 ,0
Exp/Cntr=0.3,0.1

Type RM Length L Ch R = 1 ,38509.7 ,285.3,300,312.7
XS GIS Cut Line= 3
     1754241.452      333767.706     1754471.862      333621.616
     1754803.224      333453.602
#Sta/Elev= 30
       0 1132.95    31.6 1114.48    67.2 1087.83   106.8 1047.47   122.6 1034.44
   142.3 1021.14   166.1 1012.71   181.9 1014.04   201.6 1010.05   221.4 1012.36
     257 1010.51   264.9 1009.88   280.3 1012.27   308.8 1018.44   352.7 1017.77
   372.7 1014.29   380.7 1016.95   396.7 1026.14   420.6 1029.78   448.6 1039.82
   480.6 1039.98   492.5 1033.75   496.5 1034.24   512.5 1043.84   520.5 1046.26
   540.5 1043.64   564.4 1047.91   592.4  1048.9   608.4  1045.4   644.3 1064.21
#Mann= 3 , 0 , 0
       0      .1       0     257    .045       0   280.3      .1       0
Bank Sta=257,280.3
XS Rating Curve= 0 ,0
Exp/Cntr=0.3,0.1

Type RM Length L Ch R = 1 ,38209.7 ,280.5,300,320.3
XS GIS Cut Line= 3
     1753874.059      333863.089     1754480.175      333913.086
     1754859.507      333944.789
#Sta/Elev= 30
       0 1212.09    43.7 1207.09    99.4 1211.98     163  1205.6   190.8 1198.74
   218.6 1185.91   262.4 1160.88   282.2 1153.33   337.9 1139.75   373.6 1138.87
   405.4 1120.23   457.1 1099.62   496.9 1079.04   528.7  1057.9   572.4 1014.72
   600.7 1007.29   608.2 1007.11   615.7 1007.49   679.6 1010.33   707.3  1017.4
   731.1 1013.27   782.6 1014.01   814.4    1021   846.1 1045.38     854 1048.38
   933.3 1048.19   949.2 1050.24     969 1046.78   980.9 1049.03   988.8 1053.41
#Mann= 3 , 0 , 0
       0      .1       0   600.7    .045       0   615.7      .1       0
Bank Sta=600.7,615.7
XS Rating Curve= 0 ,0
Exp/Cntr=0.3,0.1

Type RM Length L Ch R = 1 ,37909.7 ,294.7,300,303.6
XS GIS Cut Line= 3
     1754265.757      334045.484      1754352.57      334162.053
     1754566.956      334480.176
#Sta/Elev= 30
       0 1075.87    51.1 1054.58    82.5 1044.86    86.4 1042.49   106.1 1019.93
   117.8 1009.52   121.8 1007.73   137.8 1006.76   141.4 1006.62   152.8 1006.65
   161.3 1008.65   165.3 1011.93   177.3 1026.17   217.3 1026.68   229.3  1030.9
   245.2 1042.32   249.2 1043.75   273.2 1039.84   321.2 1039.23   333.2    1042
   345.2 1037.57   353.1 1036.75   385.1 1043.08   413.1  1057.2     437    1073
     453    1080     469  1082.8     489 1094.15     505 1097.62     529 1098.43
#Mann= 3 , 0 , 0
       0      .1       0   137.8    .045       0   152.8      .1       0
Bank Sta=137.8,152.8
XS Rating Curve= 0 ,0
Exp/Cntr=0.3,0.1

Type RM Length L Ch R = 1 ,37609.7 ,299.7,300,300.9
XS GIS Cut Line= 3
     1754001.868      334102.775     1754084.805      334296.419
     1754254.434      334663.949
#Sta/Elev= 30
       0 1082.33    47.7 1061.44    87.4  1046.6   115.3 1037.67     155  1028.7
   170.9 1019.42   182.8 1009.19   190.8  1006.8   203.2 1005.86   206.7 1005.82
   218.2 1005.96   230.5 1007.09   246.4 1016.18   266.2 1016.23   274.2 1017.87
   282.1 1021.66   305.9 1037.23   317.8 1035.29   373.4 1034.66   389.2 1031.73
   397.2 1026.48   405.1 1024.55   409.1  1025.2     421 1031.68   428.9 1034.51
   456.7 1051.02   496.4 1061.09   532.1 1061.87   555.9  1064.9   615.4  1069.4
#Mann= 3 , 0 , 0
       0      .1       0   203.2    .045       0   218.2      .1       0
Bank Sta=203.2,218.2
XS Rating Curve= 0 ,0
Exp/Cntr=0.3,0.1

Type RM Length L Ch R = 1 ,37309.7 ,207.6,209.5,211.3
XS GIS Cut Line= 3
     1753657.879      334045.725     1753814.146      334424.236
     1753970.413      334802.748
#Sta/Elev= 30
       0 1113.06    27.8 1097.33    43.7 1095.38    67.6  1086.3    79.5 1086.28
    87.5 1089.49    91.4 1088.12     159  1042.5   194.8 1028.24   274.3 1021.43
   282.3  1018.7   306.1 1002.32   337.9 1002.84   353.8 1008.24   373.7   997.4
     402  995.76   413.5  995.56     417  995.62   429.4  997.87   441.3 1003.38
   473.1 1004.03     489 1012.42   508.9 1028.03   516.8 1030.94   592.4 1028.99
   703.7 1034.33   739.5 1045.09   759.4 1059.85   807.1 1089.66     819 1099.37
#Mann= 3 , 0 , 0
       0      .1       0     402    .045       0     417      .1       0
Bank Sta=402,417
XS Rating Curve= 0 ,0
Exp/Cntr=0.3,0.1

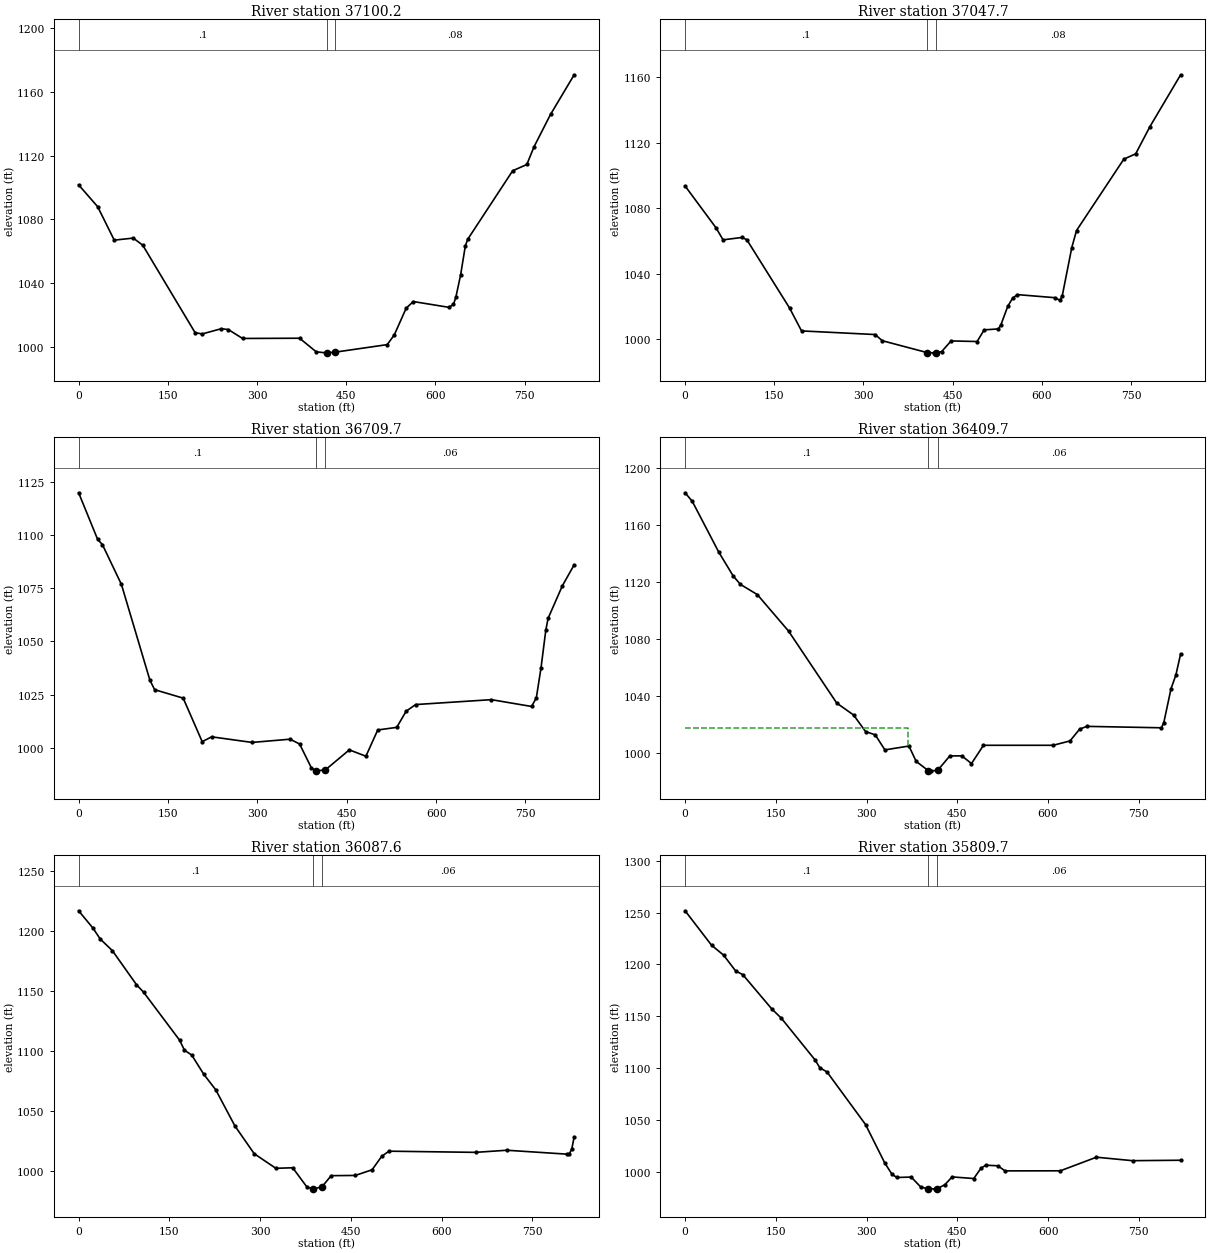
Type RM Length L Ch R = 1 ,37100.2 ,52.6,52.5,52.5
XS GIS Cut Line= 3
     1753484.507       334087.15     1753609.507      334470.831
     1753739.716      334880.553
#Sta/Elev= 30
       0 1101.65      32 1087.95    59.9 1066.95    91.9 1068.24   107.9 1063.74
   195.8  1008.9   207.8 1008.06   239.7 1011.33   251.7 1010.83   275.7 1005.23
   371.6 1005.37   399.5  996.86   415.5   996.2   416.9  996.21   431.9  996.65
     519 1001.36   530.9 1007.48   550.8 1024.18   562.8  1028.4   622.5 1024.78
   630.4 1026.55   634.4 1031.08   642.4 1045.08   650.3 1063.21   654.3 1067.46
     730 1110.51   753.8 1114.44   765.8 1125.49   793.6 1145.84   833.4 1170.76
#Mann= 3 , 0 , 0
       0      .1       0   416.9    .045       0   431.9     .08       0
Bank Sta=416.9,431.9
XS Rating Curve= 0 ,0
Exp/Cntr=0.3,0.1

Type RM Length L Ch R = 1 ,37047.7 ,343.5,338,331.8
XS GIS Cut Line= 3
     1753435.896      334106.247     1753560.896      334489.928
     1753691.104       334899.65
#Sta/Elev= 30
       0 1093.67    51.9 1068.19    63.9 1060.79    95.9 1062.27   103.9 1060.81
   175.8 1019.11   195.8  1005.2   319.6 1002.98   331.6  999.22   406.9  991.98
   419.4  991.81   421.9  991.87   431.4  992.51   447.3  999.08   491.1  998.72
     503 1005.83   526.9 1006.42   530.9 1008.68   542.8 1020.34   550.8 1025.14
   558.8 1027.36   622.5 1025.46   630.4 1023.82   634.4 1026.78   650.3 1056.03
   658.3  1066.5   737.9 1110.08   757.8 1113.31   781.7 1129.89   833.4 1161.57
#Mann= 3 , 0 , 0
       0      .1       0   406.9    .045       0   421.9     .08       0
Bank Sta=406.9,421.9
XS Rating Curve= 0 ,0
Exp/Cntr=0.3,0.1

Type RM Length L Ch R = 1 ,36709.7 ,311.5,300,289.1
XS GIS Cut Line= 3
     1753025.193      334243.686     1753239.928      334589.131
     1753472.964      334944.659
#Sta/Elev= 30
       0 1119.79    31.9  1097.9    39.9 1095.46    71.8 1076.79   119.6 1031.82
   127.6 1027.34   175.5 1023.37   207.4 1002.94   223.3 1005.21   291.1 1002.58
   354.9  1004.1   370.9 1001.84   390.8  990.57   398.8  989.24   399.2  989.24
   414.2  989.69   454.4  999.09   482.2  996.09   502.1 1008.43   533.9 1009.65
   549.8 1017.24   565.7 1020.36   692.8 1022.66   760.3 1019.46   768.3 1023.51
   776.2 1037.71   784.2 1055.31   788.1 1060.89     812 1076.14   831.8 1085.96
#Mann= 3 , 0 , 0
       0      .1       0   399.2    .045       0   414.2     .06       0
Bank Sta=399.2,414.2
XS Rating Curve= 0 ,0
Exp/Cntr=0.3,0.1

Type RM Length L Ch R = 1 ,36409.7 ,329.5,322.1,314.6
XS GIS Cut Line= 3
     1752697.555      334616.736     1753055.709      334816.024
     1753412.946      335016.087
#Sta/Elev= 30
       0 1182.63    11.9  1176.6    55.7 1140.92    79.6 1124.16    91.5 1118.28
   119.4 1111.14   171.1 1085.47   250.7 1034.96   278.6 1026.55   298.4 1014.94
   314.4 1012.64   330.3 1002.08   370.1 1004.77     382  994.01   402.4   987.4
   405.9  987.36   417.4  987.62   437.7  997.85   457.6  997.86   473.5  992.47
   493.3  1005.3   608.6  1005.3   636.4 1008.38   652.4 1016.69   664.3 1018.59
   787.5 1017.59   791.5 1021.28   803.4 1045.04   811.4  1054.6   819.3 1069.49
#Mann= 3 , 0 , 0
       0      .1       0   402.4    .045       0   417.4     .06       0
#XS Ineff= 2 , 0
          369.14 1017.26
Permanent Ineff=
       F       F
Bank Sta=402.4,417.4
XS Rating Curve= 0 ,0
Exp/Cntr=0.3,0.1

Type RM Length L Ch R = 1 ,36087.6 ,280.9,277.9,274.9
XS GIS Cut Line= 3
     1752561.004      335048.183     1752964.025      335120.727
     1753366.649      335195.496
#Sta/Elev= 30
       0 1216.58    23.8 1202.08    35.8    1193    55.7 1183.45    95.4 1155.21
   107.3 1148.85     167 1108.79   174.9 1100.52   186.9 1096.52   206.7  1080.6
   226.6 1067.58   258.4 1037.41   290.2 1014.39     326 1002.24   353.8 1002.71
   377.7  986.42   387.4  985.18   389.6  985.16   402.4  986.98   417.4  996.13
   457.2   996.3     485 1001.03   500.9  1012.2   512.9  1016.5     656 1015.52
   707.7 1017.28   807.1 1014.03     811  1014.4     815 1018.21     819 1028.41
#Mann= 3 , 0 , 0
       0      .1       0   387.4    .045       0   402.4     .06       0
Bank Sta=387.4,402.4
XS Rating Curve= 0 ,0
Exp/Cntr=0.3,0.1

Type RM Length L Ch R = 1 ,35809.7 ,308.9,300,291.1
XS GIS Cut Line= 3
     1752510.732      335375.826     1752919.836      335393.837
      1753328.94      335411.847
#Sta/Elev= 30
       0 1251.79    43.7 1218.57    63.6 1209.02    83.5  1193.8    95.4 1190.17
   143.1 1157.23     159 1148.22   214.7 1108.01   222.6 1100.49   234.6 1096.28
   298.2 1045.64     330 1008.55   341.9   997.7   349.9  994.55   373.7  994.97
   389.6  985.27     402  983.68   413.5   983.6     417  983.83   429.4  987.63
   441.3  995.11   477.1  993.54     489  1003.5     497 1006.42   516.8 1005.83
   528.8 1000.92   620.2 1000.99   679.8 1014.11   739.5 1010.76     819 1011.18
#Mann= 3 , 0 , 0
       0      .1       0     402    .045       0     417     .06       0
Bank Sta=402,417
XS Rating Curve= 0 ,0
Exp/Cntr=0.3,0.1

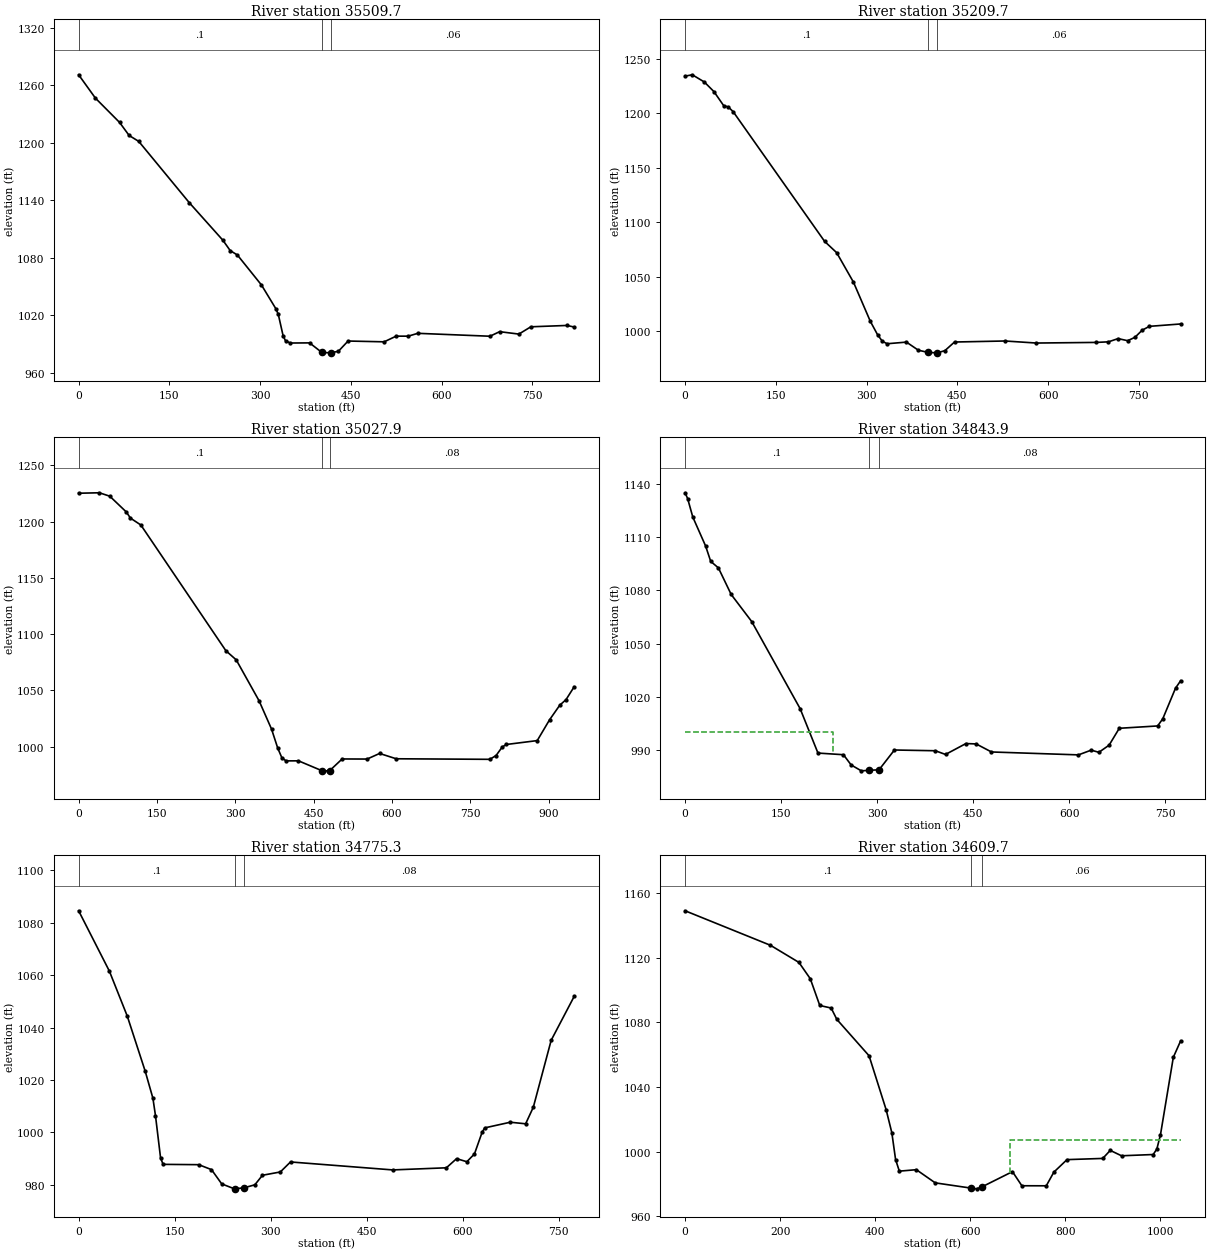
Type RM Length L Ch R = 1 ,35509.7 ,303.5,300,296.5
XS GIS Cut Line= 3
     1752587.288      335825.449     1752972.224      335685.755
     1753357.159       335546.06
#Sta/Elev= 30
       0 1270.86    27.8 1246.47    67.6 1221.25    83.5 1207.58    99.4 1201.41
   182.9 1137.53   238.5 1098.34   250.5 1087.61   262.4    1083   302.2 1051.73
     326 1026.98     330  1021.1   337.9  998.99   341.9   993.6   349.9  991.27
   381.7  991.42     402  981.42     417  981.04   429.4  982.72   445.3  993.35
   504.9  992.52   524.8  998.44   544.7  998.42   560.6 1001.38   679.8  998.35
   695.8  1003.1   727.6 1000.59   747.4 1008.18   807.1 1009.59     819 1007.93
#Mann= 3 , 0 , 0
       0      .1       0     402    .045       0     417     .06       0
Bank Sta=402,417
XS Rating Curve= 0 ,0
Exp/Cntr=0.3,0.1

Type RM Length L Ch R = 1 ,35209.7 ,181.1,181.7,182.2
XS GIS Cut Line= 3
     1752739.115      336155.595     1753097.586      335957.634
     1753456.286      335760.086
#Sta/Elev= 30
       0 1233.88    11.9 1235.12    31.8  1228.5    47.7 1219.65    63.6 1206.93
    71.6 1205.49    79.5 1201.23   230.6 1082.24   250.5  1071.9   278.3 1044.79
   306.1 1008.95   318.1   996.6     326  990.59     334  988.34   365.8  989.84
   385.6  982.36     402  980.37     417  979.99   429.4  982.01   445.3  989.92
   528.8  990.86   580.5  988.98   679.8  989.56   699.7  990.09   715.6  993.05
   731.5  991.13   743.5  994.25   755.4 1000.76   767.3  1004.3     819 1006.48
#Mann= 3 , 0 , 0
       0      .1       0     402    .045       0     417     .06       0
Bank Sta=402,417
XS Rating Curve= 0 ,0
Exp/Cntr=0.3,0.1

Type RM Length L Ch R = 1 ,35027.9 ,194.5,184.1,170.7
XS GIS Cut Line= 5
     1752731.383      336176.056     1753036.591      336193.053
     1753174.561       336122.41     1753485.009      335959.794
     1753606.035      335894.442
#Sta/Elev= 30
       0 1225.29    39.7 1225.69    59.6 1222.66    91.3 1208.61    99.2 1203.15
   119.1 1197.04   281.9 1085.21   301.7 1077.09   345.4 1040.74   369.3 1015.54
   381.2  998.56   389.1  989.98   397.1  987.23   420.9  987.28   465.5  978.55
   476.6  978.38   480.5  978.48   504.5  988.95   552.3  988.86   576.2  993.84
     608  989.11   787.2  988.62   799.2     992   811.1  999.67     819 1001.83
     878 1005.28   901.5 1023.72   921.2 1036.81     933 1041.65   948.7 1053.14
#Mann= 3 , 0 , 0
       0      .1       0   465.5    .045       0   480.5     .08       0
Bank Sta=465.5,480.5
XS Rating Curve= 0 ,0
Exp/Cntr=0.3,0.1

Type RM Length L Ch R = 1 ,34843.9 ,68.7,68.6,72
XS GIS Cut Line= 5
     1753038.327      336408.331     1753170.271      336408.331
     1753283.118      336264.234     1753305.688      336154.859
      1753621.66      336010.761
#Sta/Elev= 30
       0 1135.08       4 1131.77      12 1121.41      32 1105.07      40 1096.37
      52 1092.69      72 1077.67     104 1062.42   179.7  1013.2   207.5  988.17
   247.3  987.24   259.3  981.47   275.2  978.14   287.9  978.43   302.9  978.74
   326.9   989.9   390.8  989.48   406.7  987.39   438.6  993.54   454.6  993.32
   478.5  988.79   614.3  987.15   634.2  989.82   646.2   988.6   662.2  992.63
   678.1 1002.16     738 1003.48     746 1007.52   765.9 1024.79   773.9 1028.99
#Mann= 3 , 0 , 0
       0      .1       0   287.9    .045       0   302.9     .08       0
#XS Ineff= 2 , 0
          230.64 1000.07
Permanent Ineff=
       F       F
Bank Sta=287.9,302.9
XS Rating Curve= 0 ,0
Exp/Cntr=0.3,0.1

Type RM Length L Ch R = 1 ,34775.3 ,150.2,165.6,181.8
XS GIS Cut Line= 5
     1753097.354      336434.372     1753229.299      336434.372
     1753342.146      336290.275     1753364.716        336180.9
     1753680.688      336036.803
#Sta/Elev= 30
       0 1084.55      48 1061.53      76 1044.33     104  1023.3     116 1013.02
     120 1006.41     128  990.17     132  987.78   187.6  987.66   207.5  985.77
   223.5  980.32   243.4  978.44   243.8  978.45   258.8  978.86   275.2  979.98
   287.1  983.62     315  984.88   330.9   988.7   490.5  985.66   574.3  986.47
   590.3  989.96   606.3  988.78   618.2  991.77   630.2 1000.08   634.2  1001.7
   674.1 1003.86   698.1 1003.26   710.1 1009.59     738 1035.14   773.9 1051.87
#Mann= 3 , 0 , 0
       0      .1       0   243.8    .045       0   258.8     .08       0
Bank Sta=243.8,258.8
XS Rating Curve= 0 ,0
Exp/Cntr=0.3,0.1

Type RM Length L Ch R = 1 ,34609.7 ,280.2,300,320.1
XS GIS Cut Line= 5
     1752815.367       336347.31     1753198.049      336536.803
     1753374.343      336489.152     1753715.187      336417.685
     1753798.743      336403.122
#Sta/Elev= 30
       0 1149.05   179.6 1127.69   239.5  1117.1   263.4    1107   283.4 1090.44
   307.3 1088.86   319.3 1081.83   387.1 1059.31     423 1025.95     435 1011.69
   442.9  995.09   450.8  987.91   486.6  988.81   526.3  980.66   602.1  977.39
   613.6  976.96   625.5  978.31   688.8   987.6   708.6  978.87     760  978.84
   775.9  987.29   803.6  995.04   878.8  995.78   894.6 1000.75   918.3  997.42
   984.9   998.2   992.6 1001.56  1000.3 1010.49  1027.3 1058.37  1042.7 1068.54
#Mann= 3 , 0 , 0
       0      .1       0   602.1    .045       0   625.5     .06       0
#XS Ineff= 2 , 0
                           683.1         1007.14
Permanent Ineff=
       F       F
Bank Sta=602.1,625.5
XS Rating Curve= 0 ,0
Exp/Cntr=0.3,0.1

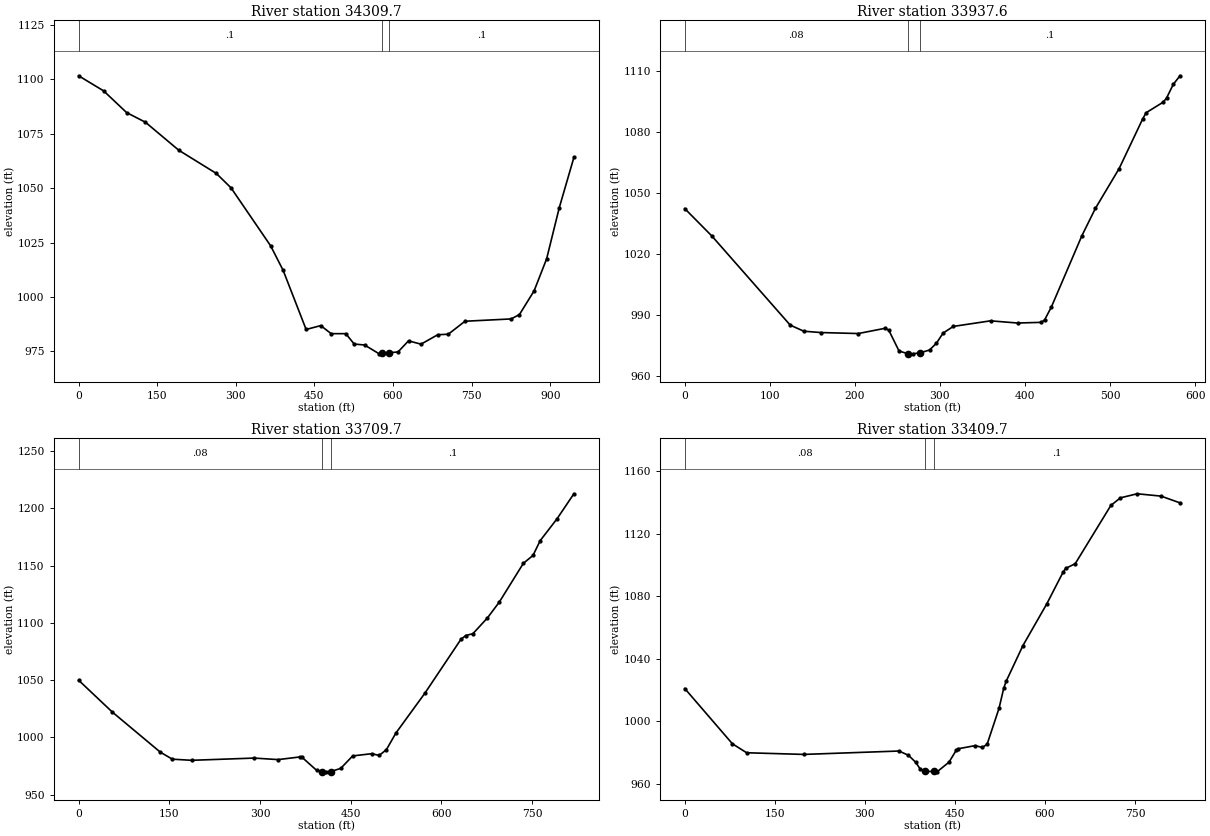
Type RM Length L Ch R = 1 ,34309.7 ,350.8,372.1,391
XS GIS Cut Line= 3
     1752786.384      336414.654     1753267.526      336748.505
     1753548.743      336972.567
#Sta/Elev= 30
       0 1101.54    47.8  1094.6    91.6 1084.65   127.5 1080.22   191.2 1067.36
   262.9  1056.7   290.8 1050.13   366.5 1023.48   390.4  1012.2   434.2   985.1
   462.1  986.88     482  983.18   509.9  983.18   525.9  978.42   545.8  977.97
   573.7  973.92   578.1  974.23   593.1  974.43   609.6  974.79   629.6  979.88
   653.5  978.36   685.5   982.7   705.5  982.92   737.4  988.88   825.3  989.94
   841.3  991.94   869.3 1002.83   893.2 1017.52   917.2 1040.88   945.2 1064.04
#Mann= 3 , 0 , 0
       0      .1       0   578.1    .045       0   593.1      .1       0
Bank Sta=578.1,593.1
XS Rating Curve= 0 ,0
Exp/Cntr=0.3,0.1

Type RM Length L Ch R = 1 ,33937.6 ,230.6,227.9,225.9
XS GIS Cut Line= 3
     1752918.535      336573.261     1752923.743       336837.15
     1752944.577      337154.859
#Sta/Elev= 30
       0 1042.25      32 1028.72     124  984.96     140  981.97     160  981.32
     204  980.83     236  983.45     240  982.36   251.9  972.26     262  970.93
   267.9  970.85     277  971.39   287.8  972.73   295.8  976.03   303.7  981.04
   315.7  984.33   359.5  987.08   391.3     986   419.2  986.33   423.1  987.54
   431.1  993.94   466.9 1028.92   482.8 1042.37   510.7 1061.94   538.6 1086.54
   542.5 1089.42   562.4 1094.57   566.4 1096.55   574.4  1103.4   582.3 1107.57
#Mann= 3 , 0 , 0
       0     .08       0     262    .045       0     277      .1       0
Bank Sta=262,277
XS Rating Curve= 0 ,0
Exp/Cntr=0.3,0.1

Type RM Length L Ch R = 1 ,33709.7 ,298.1,300,300.1
XS GIS Cut Line= 3
     1752636.733      336471.376     1752698.644      336876.171
     1752761.659      337280.793
#Sta/Elev= 30
       0 1049.95    55.7 1022.16   135.2  987.07     155  980.99   186.9     980
   290.2  981.95     330  980.62   365.8  982.93   369.7   982.5   393.6  971.24
     402     970   409.5  969.93     417  970.21   433.4  972.92   453.2  983.83
     485   985.8     497  984.23   508.9  989.25   524.8  1003.9   572.5 1038.54
   632.1 1085.58   640.1    1089     652 1090.58   675.9 1104.28   695.8  1118.3
   735.5 1152.08   751.4 1158.96   763.3 1171.87   791.2 1190.99     819  1212.8
#Mann= 3 , 0 , 0
       0     .08       0     402    .045       0     417      .1       0
Bank Sta=402,417
XS Rating Curve= 0 ,0
Exp/Cntr=0.3,0.1

Type RM Length L Ch R = 1 ,33409.7 ,228.7,230,233.7
XS GIS Cut Line= 3
     1752372.169      336479.194     1752399.861      336886.674
     1752461.473      337298.784
#Sta/Elev= 30
       0 1020.84    79.3  985.46   103.1   979.7   198.3  978.64   356.9  980.81
   372.7  978.07   384.6  973.64   392.6  969.08   400.9  967.77   415.9   967.7
   420.3  967.48   440.2  973.68   452.1  981.19     456  982.29   483.8  984.27
   495.7  983.11   503.7  985.15   523.5 1008.09   531.4 1021.04   535.4 1025.45
   563.2 1048.24   602.9 1074.92   630.6 1095.62   634.6 1097.78   650.5 1100.81
     710 1138.19   725.9 1142.99   753.7 1145.58   793.4 1144.09   825.1 1139.74
#Mann= 3 , 0 , 0
       0     .08       0   400.9    .045       0   415.9      .1       0
Bank Sta=400.9,415.9
XS Rating Curve= 0 ,0
Exp/Cntr=0.3,0.1