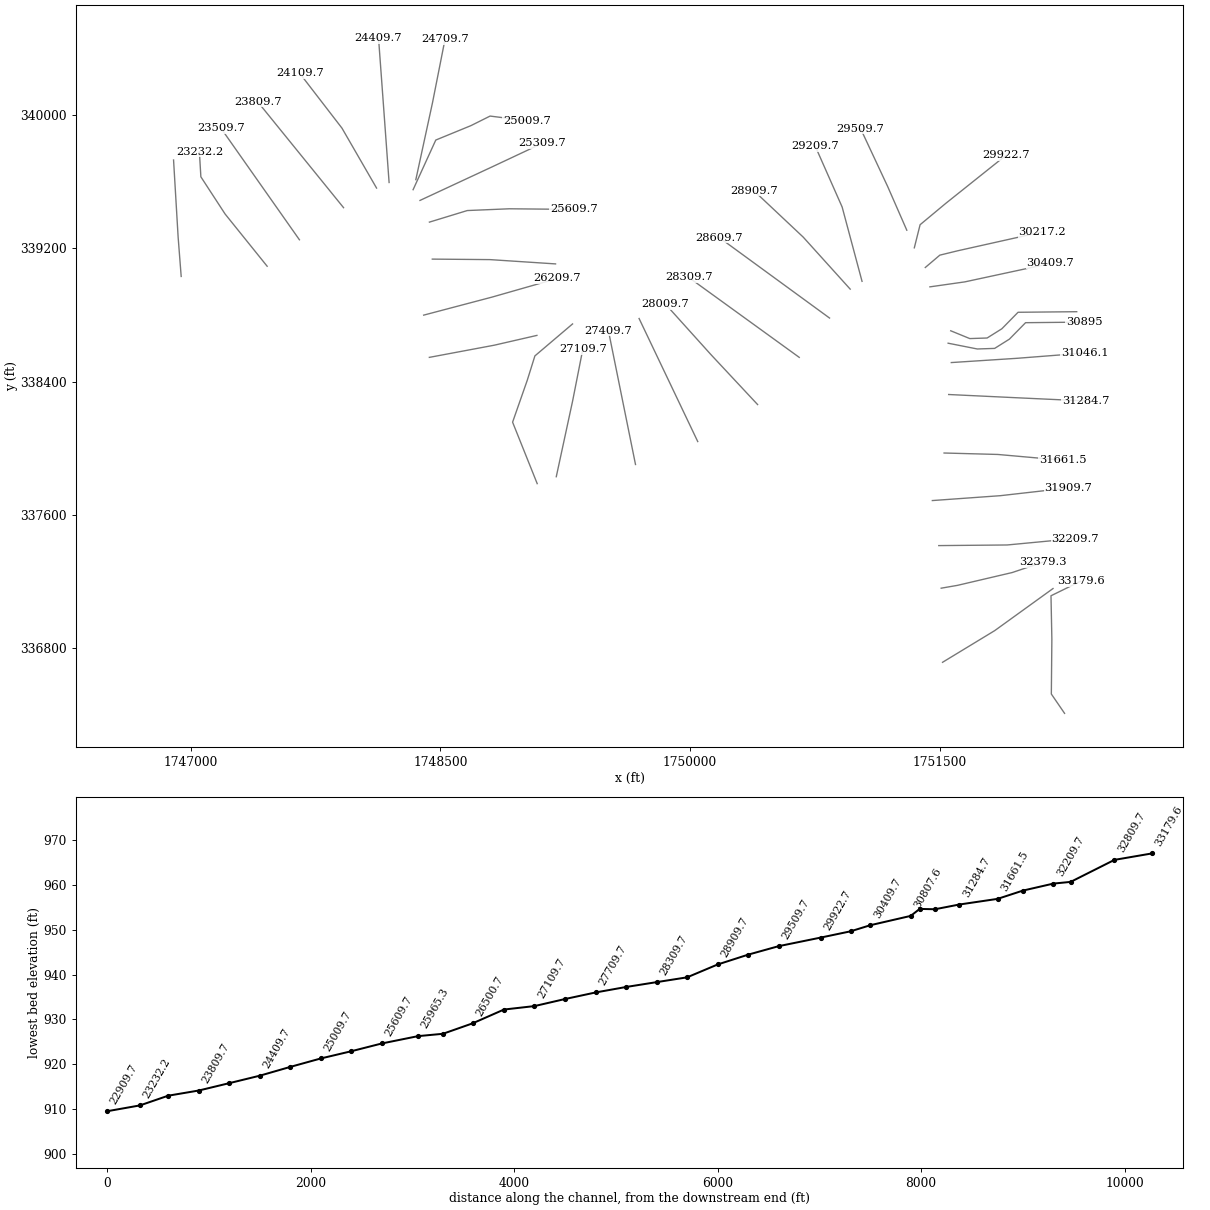
HEC-RAS study SPLAURFK.prj: SPLAURFK

--- SPLAURFK.g01 (geometry) --- (continued)

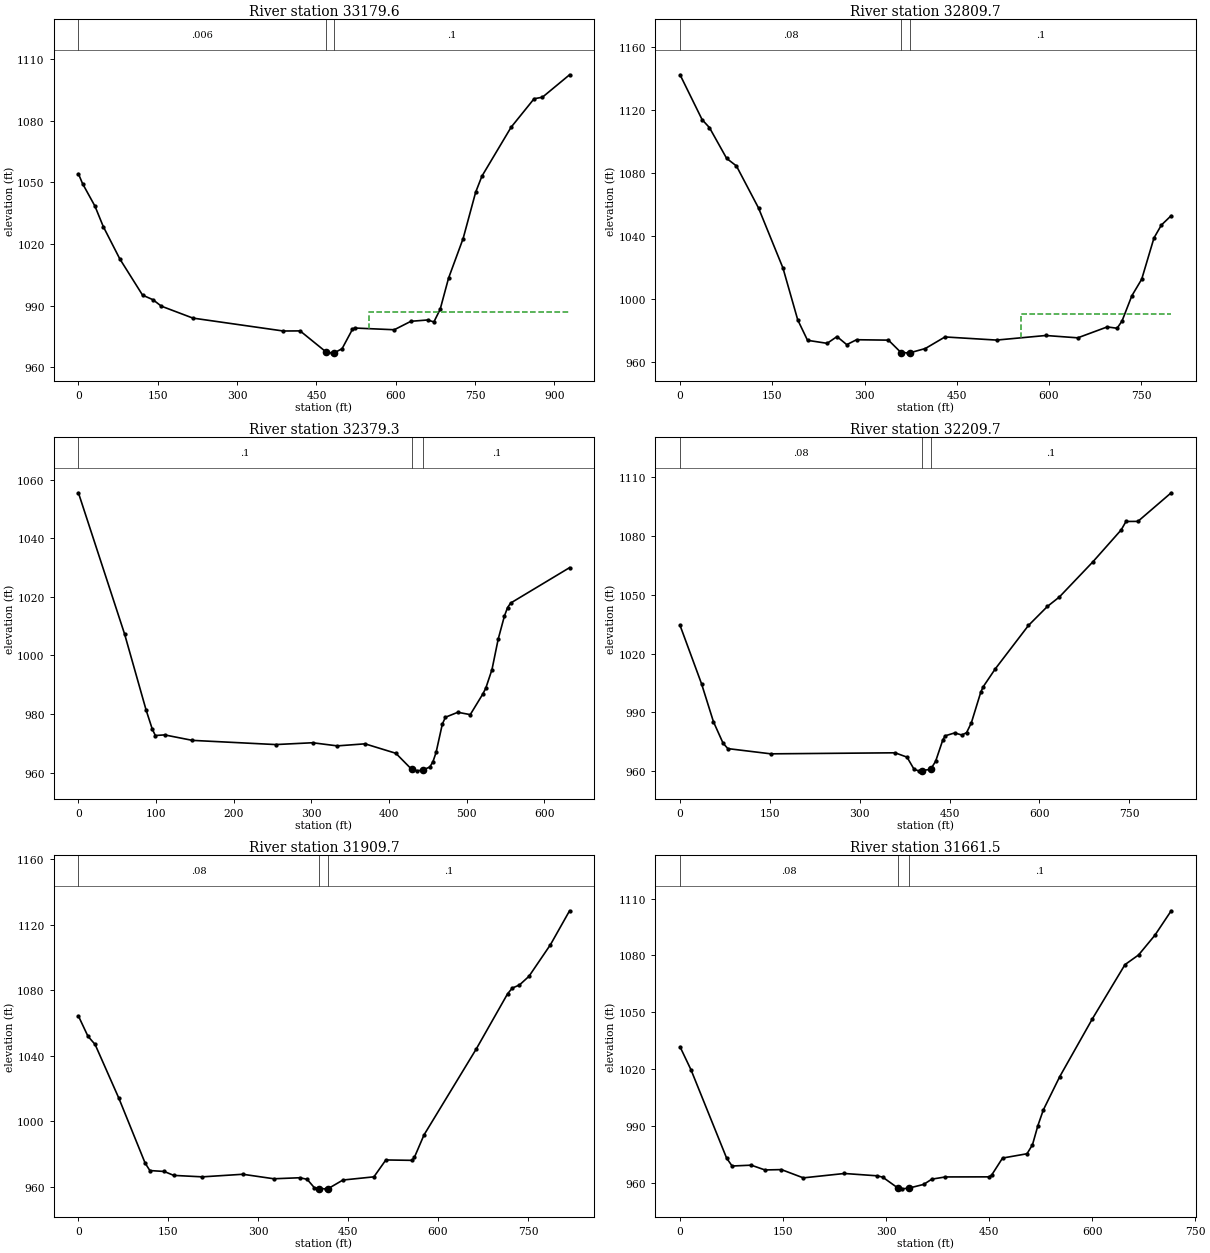
Type RM Length L Ch R = 1 ,33179.6 ,393.1,370,348.1
XS GIS Cut Line= 5
     1752250.132      336406.595     1752170.617      336522.878
     1752173.743      336852.775     1752168.535      337113.192
     1752345.618      337199.997
#Sta/Elev= 30
       0 1054.21     7.8 1049.43    31.3 1038.42      47 1028.49    78.3 1012.71
   121.3  995.07   140.9  992.85   156.8   989.7   216.4  983.89   387.3   977.6
   419.1  977.65   468.9  967.24   478.7  966.96   483.9     967   498.4  968.96
   518.1  978.45   522.1  979.05   597.1  978.21   628.6  982.33   660.2  982.97
     672  982.01   683.9  988.19   699.7 1003.33   727.3 1022.67     751 1045.25
   762.8 1053.04     818  1076.9   861.4 1090.76   877.2 1091.52   928.5 1102.45
#Mann= 3 , 0 , 0
       0    .006       0   468.9    .045       0   483.9      .1       0
#XS Ineff= 2 , 0
                          549.46          986.86
Permanent Ineff=
       F       F
Bank Sta=468.9,483.9
XS Rating Curve= 0 ,0
Exp/Cntr=0.3,0.1

Type RM Length L Ch R = 1 ,32809.7 ,437.1,430.3,423.8
XS GIS Cut Line= 3
     1751516.979      336713.489     1751830.503      336903.843
     1752180.688      337156.595
#Sta/Elev= 30
       0 1142.24    35.9 1113.71    47.8 1108.66    75.8 1089.09    91.7 1084.29
   127.6 1057.58   167.4 1019.36   191.4  986.44   207.3  973.48   239.2  971.56
   255.2  975.85   271.1  970.72     287  973.85   338.9  973.59   359.3   965.7
   370.8  965.52   374.3  965.61   398.8  968.25   430.8  975.62   514.7  973.63
   594.7  976.54   646.7  975.06   694.7     982   710.7  981.14   718.7  985.74
   734.7 1001.78   750.7  1012.3   770.7 1038.55   782.7 1046.73   798.7 1052.71
#Mann= 3 , 0 , 0
       0     .08       0   359.3    .045       0   374.3      .1       0
#XS Ineff= 2 , 0
                          554.89          990.48
Permanent Ineff=
       F       F
Bank Sta=359.3,374.3
XS Rating Curve= 0 ,0
Exp/Cntr=0.3,0.1

Type RM Length L Ch R = 1 ,32379.3 ,174.7,169.7,164.5
XS GIS Cut Line= 4
     1751508.784      337158.749     1751606.441      337175.676
     1751935.075      337252.614     1752120.764      337314.999
#Sta/Elev= 30
       0 1055.54    59.5 1007.29    87.2  981.35    95.2   974.8    99.1  972.68
     111  972.89   146.8  971.02     254  969.59   301.6  970.21   333.4  969.14
   369.1  969.84   408.8  966.61   429.1  961.15   436.6  960.62   444.1  960.95
   452.6  961.95   456.6  963.76   460.6   966.9   468.6  976.52   472.6  978.91
   488.6  980.61   504.6  979.81   520.6  986.76   524.6  988.83   532.6  995.21
   540.6 1005.59   548.6 1013.45   552.6 1016.32   556.6 1017.89   632.5 1029.98
#Mann= 3 , 0 , 0
       0      .1       0   429.1    .045       0   444.1      .1       0
Bank Sta=429.1,444.1
XS Rating Curve= 0 ,0
Exp/Cntr=0.3,0.1

Type RM Length L Ch R = 1 ,32209.7 ,298.6,300,300.4
XS GIS Cut Line= 3
      1751494.32      337414.603     1751905.227       337418.31
     1752312.651      337457.024
#Sta/Elev= 30
       0  1034.4    35.9 1004.63    55.8  985.26    71.8  974.36    79.8  971.58
   151.6  968.91   359.1  969.44     379  967.23     391  960.93     399  960.24
   403.4  960.36   418.4     961   426.8  965.12   438.7  975.91   442.7   978.1
   458.6  979.58   470.5  978.51   478.5  979.72   486.4  984.68   502.3 1000.46
   506.3 1003.15   526.2 1012.16   581.8 1034.38   613.6 1044.12   633.4 1048.89
   689.1 1066.73   736.7 1083.13   744.7 1087.42   764.6 1087.46   820.2 1102.05
#Mann= 3 , 0 , 0
       0     .08       0   403.4    .045       0   418.4      .1       0
Bank Sta=403.4,418.4
XS Rating Curve= 0 ,0
Exp/Cntr=0.3,0.1

Type RM Length L Ch R = 1 ,31909.7 ,250.5,248.2,243.5
XS GIS Cut Line= 3
     1751455.713      337685.183     1751864.091      337714.435
     1752271.403      337760.688
#Sta/Elev= 30
       0 1064.23    15.9 1051.86    27.8 1046.88    67.6  1013.9   111.3   974.4
   119.2  969.85   143.1  969.29     159  966.89   206.7     966   274.3  967.58
     326  964.83   369.7  965.46   381.6  964.47   393.5  959.44   401.9  958.81
   413.4  958.68   416.9  958.86   441.3  964.06     493  966.01   512.9  976.32
   556.7  976.08   560.7  978.06   576.6  991.62   664.1 1044.32   715.9 1077.73
   723.8 1081.28   735.8 1083.16   751.7 1088.48   787.5 1107.77   819.4 1128.48
#Mann= 3 , 0 , 0
       0     .08       0   401.9    .045       0   416.9      .1       0
Bank Sta=401.9,416.9
XS Rating Curve= 0 ,0
Exp/Cntr=0.3,0.1

Type RM Length L Ch R = 1 ,31661.5 ,377.5,376.8,377.4
XS GIS Cut Line= 3
     1751526.174      337970.831     1751849.091       337962.15
     1752239.716      337927.428
#Sta/Elev= 30
       0 1031.77      16  1019.6    67.8  973.06    75.8  968.88   103.7  969.33
   123.6  966.81   147.6  966.99   179.5  962.63   239.3  964.94   287.1  963.71
   295.1     963     318  957.07     323  956.84     333   957.2   354.7  959.17
   366.6  961.95   386.4  963.12   449.8  963.16   453.8  964.13   469.6  973.08
   505.2  975.35   513.2   980.1   521.1  990.24     529  998.49   552.8 1015.99
   600.3 1046.48   647.9 1075.15   667.7 1080.26   691.4 1090.63   715.2 1103.56
#Mann= 3 , 0 , 0
       0     .08       0     318    .045       0     333      .1       0
Bank Sta=318,333
XS Rating Curve= 0 ,0
Exp/Cntr=0.3,0.1

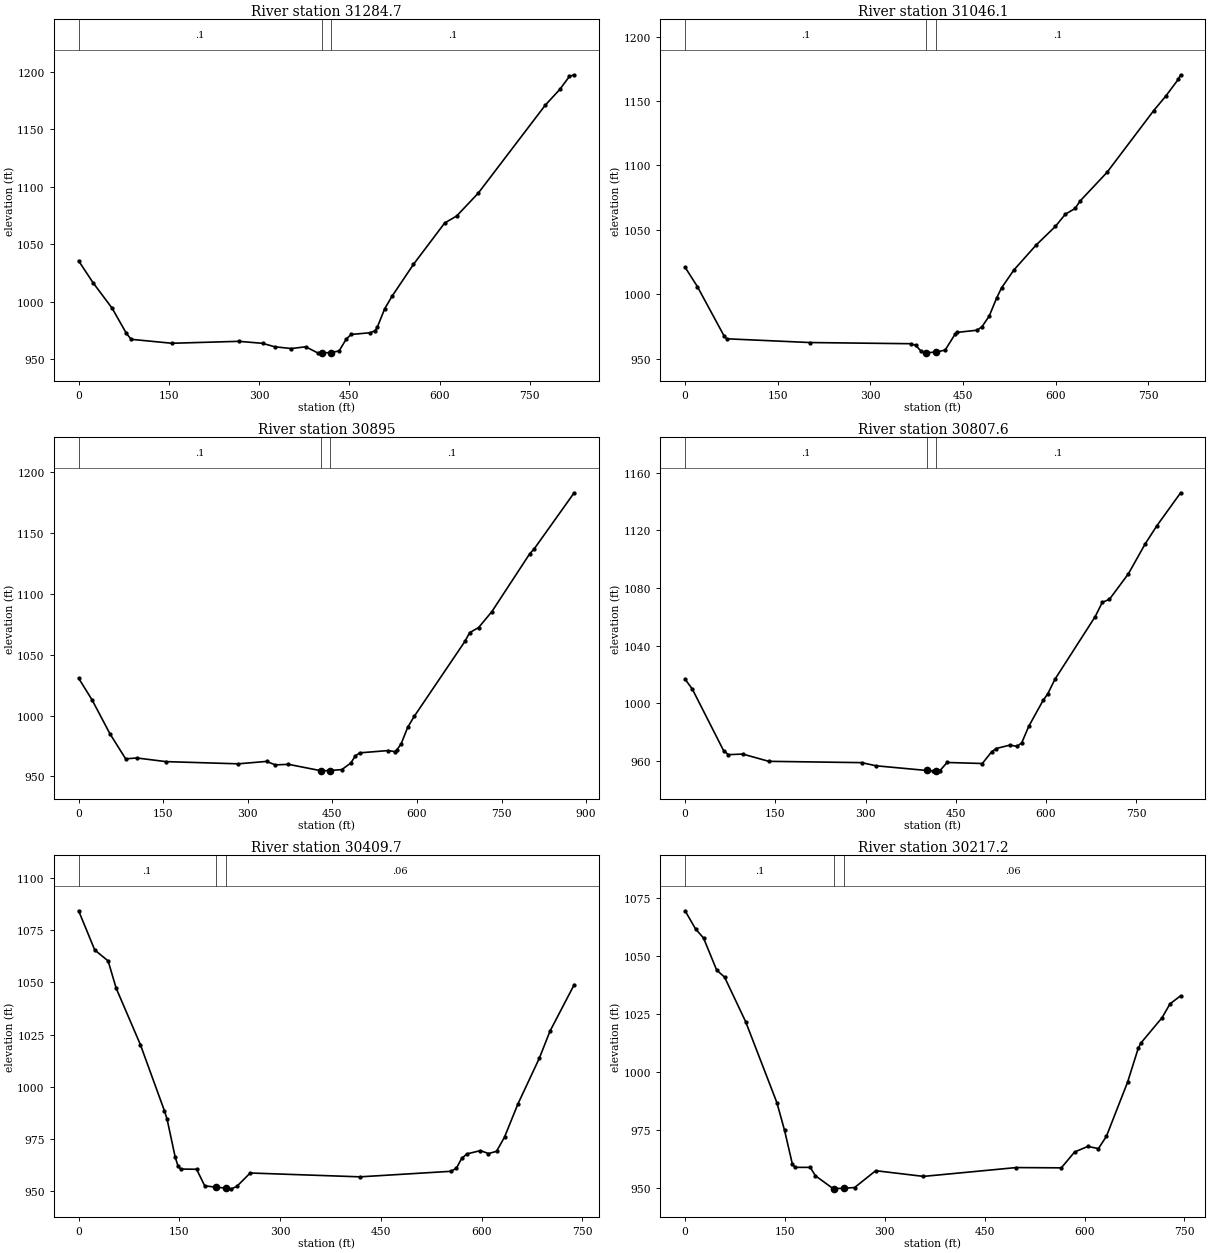
Type RM Length L Ch R = 1 ,31284.7 ,236.1,238.5,241.3
XS GIS Cut Line= 3
     1751553.897      338322.274     1751970.618      338302.428
     1752376.867      338283.553
#Sta/Elev= 30
       0 1035.64    23.8 1016.73    55.6  994.48    79.5  972.44    87.4  967.34
     155  963.91   266.2  965.59   305.9  963.86   325.8  960.87   353.6  959.31
   377.5  960.85   397.3  955.58   404.2  955.71   419.2  955.66   433.1  957.31
   445.1  967.65   453.1  971.57     485  973.09     493  974.87   496.9  978.29
   508.9  993.97   520.9 1004.67   556.7 1032.56   608.6 1068.57   628.5 1074.65
   664.4 1094.54     776 1171.19     800  1184.8   815.9 1196.06   823.9 1197.54
#Mann= 3 , 0 , 0
       0      .1       0   404.2    .045       0   419.2      .1       0
Bank Sta=404.2,419.2
XS Rating Curve= 0 ,0
Exp/Cntr=0.3,0.1

Type RM Length L Ch R = 1 ,31046.1 ,131.2,151.1,170.4
XS GIS Cut Line= 3
     1751569.577      338514.234     1751965.988      338539.935
     1752370.061      338571.503
#Sta/Elev= 30
       0 1020.93    19.9 1005.94    63.6  967.25    67.5  965.43   202.6  962.52
   365.5  961.61   373.4  960.42   381.4  956.24   389.3  954.53   390.9  954.57
   405.9  955.15   421.1  956.62     437  968.78     441  970.42   472.7  972.07
   480.7  974.72   492.6   983.1   504.5  996.99   512.5  1004.9   532.4 1018.74
   568.1 1037.95   599.9 1052.72   615.8  1062.1   631.7 1066.56   639.6 1072.27
   683.3 1094.55   758.8  1142.4   778.7 1153.86   798.6 1166.65   802.6  1170.3
#Mann= 3 , 0 , 0
       0      .1       0   390.9    .045       0   405.9      .1       0
Bank Sta=390.9,405.9
XS Rating Curve= 0 ,0
Exp/Cntr=0.3,0.1

Type RM Length L Ch R = 1 ,30895   ,90.6,87.4,84.5
XS GIS Cut Line= 6
     1751550.479      338630.553     1751725.827      338595.831
     1751829.993      338599.303     1751918.535      338654.859
     1752015.757      338753.817     1752368.188      338757.289
#Sta/Elev= 30
       0 1030.72    23.8 1012.94    55.6  984.99    83.4  964.47   103.3  965.17
   154.9  962.18     283  960.37   333.3  962.35   348.8  959.49     372  959.95
     430  954.67   431.1   954.6     445  954.87   466.8  955.63   482.6  960.99
   490.6  966.79   498.5  969.39   549.2  971.27   560.6  970.42   564.5  971.79
   572.1  976.97   583.6  990.39     595  999.27   685.5 1061.32   693.4 1068.22
   709.2 1072.28   732.9 1085.51   799.9 1132.97   807.8 1136.97   878.8 1183.14
#Mann= 3 , 0 , 0
       0      .1       0     430    .045       0     445      .1       0
Bank Sta=430,445
XS Rating Curve= 0 ,0
Exp/Cntr=0.3,0.1

Type RM Length L Ch R = 1 ,30807.6 ,413,398,384.6
XS GIS Cut Line= 6
     1751566.104      338705.206     1751680.688      338658.331
     1751784.854      338661.803     1751873.396      338717.359
     1751970.618      338816.317     1752323.049      338819.789
#Sta/Elev= 30
       0 1016.66      12 1009.79    63.9  967.16    71.9  964.28    95.8  964.69
   139.2  959.65   293.8  958.74   317.1  956.57   401.7   953.3   411.8  953.05
   416.7  953.07   423.7   953.2   435.6  958.86   494.2  958.14   509.5  966.19
   517.2  968.54   540.1  970.92   551.7  970.06   559.6  972.42   571.4  983.96
   595.1 1001.87     603 1006.51   614.8  1016.5   681.9 1060.13   693.7    1070
   705.5 1072.08   737.1 1089.84   764.7 1110.37   784.4 1123.16   823.9 1146.02
#Mann= 3 , 0 , 0
       0      .1       0   401.7    .045       0   416.7      .1       0
Bank Sta=401.7,416.7
XS Rating Curve= 0 ,0
Exp/Cntr=0.3,0.1

Type RM Length L Ch R = 1 ,30409.7 ,190.4,192.5,192.6
XS GIS Cut Line= 3
     1751441.104      338969.095     1751650.668      338998.931
     1752165.063       339109.72
#Sta/Elev= 30
       0 1084.42      24 1065.59    43.9 1060.36    55.9 1047.25    91.9 1020.21
   127.8  988.39   131.8  984.27   143.8  966.17   147.8   962.1   151.8  960.46
   175.7  960.37   187.7  952.44   204.2  951.75   219.2  951.34   227.6  950.97
   235.6  952.16   255.5  958.57     419  956.73   554.5  959.39   562.5  960.86
   570.4  965.59   578.4  967.76   598.4  969.32   610.3   967.9   622.3  968.97
   634.2  975.82   654.2  991.75     686 1013.65     702 1026.72   737.9 1048.92
#Mann= 3 , 0 , 0
       0      .1       0   204.2    .045       0   219.2     .06       0
Bank Sta=204.2,219.2
XS Rating Curve= 0 ,0
Exp/Cntr=0.3,0.1

Type RM Length L Ch R = 1 ,30217.2 ,283.9,294.5,304.8
XS GIS Cut Line= 4
     1751413.327      339085.414      1751500.67      339159.597
     1751609.507      339186.109     1752114.716      339298.956
#Sta/Elev= 30
       0 1069.62    15.8 1061.74    27.7 1057.87    47.4 1044.03    59.3 1040.97
    90.9 1021.79   137.8  986.87   149.4  974.84     161  960.46   164.8  958.89
     188  958.88   195.7  955.27   222.8  949.62   223.9  949.67   238.9  949.93
   254.5  950.16   286.3  957.45     358  954.99   497.4   958.8   565.1  958.68
     585  965.52   604.9  967.92   620.8  966.99   632.8  972.28   664.6  995.65
   680.6 1010.26   684.5 1012.51   716.4 1023.48   728.3 1029.44   744.3 1032.95
#Mann= 3 , 0 , 0
       0      .1       0   223.9    .045       0   238.9     .06       0
Bank Sta=223.9,238.9
XS Rating Curve= 0 ,0
Exp/Cntr=0.3,0.1

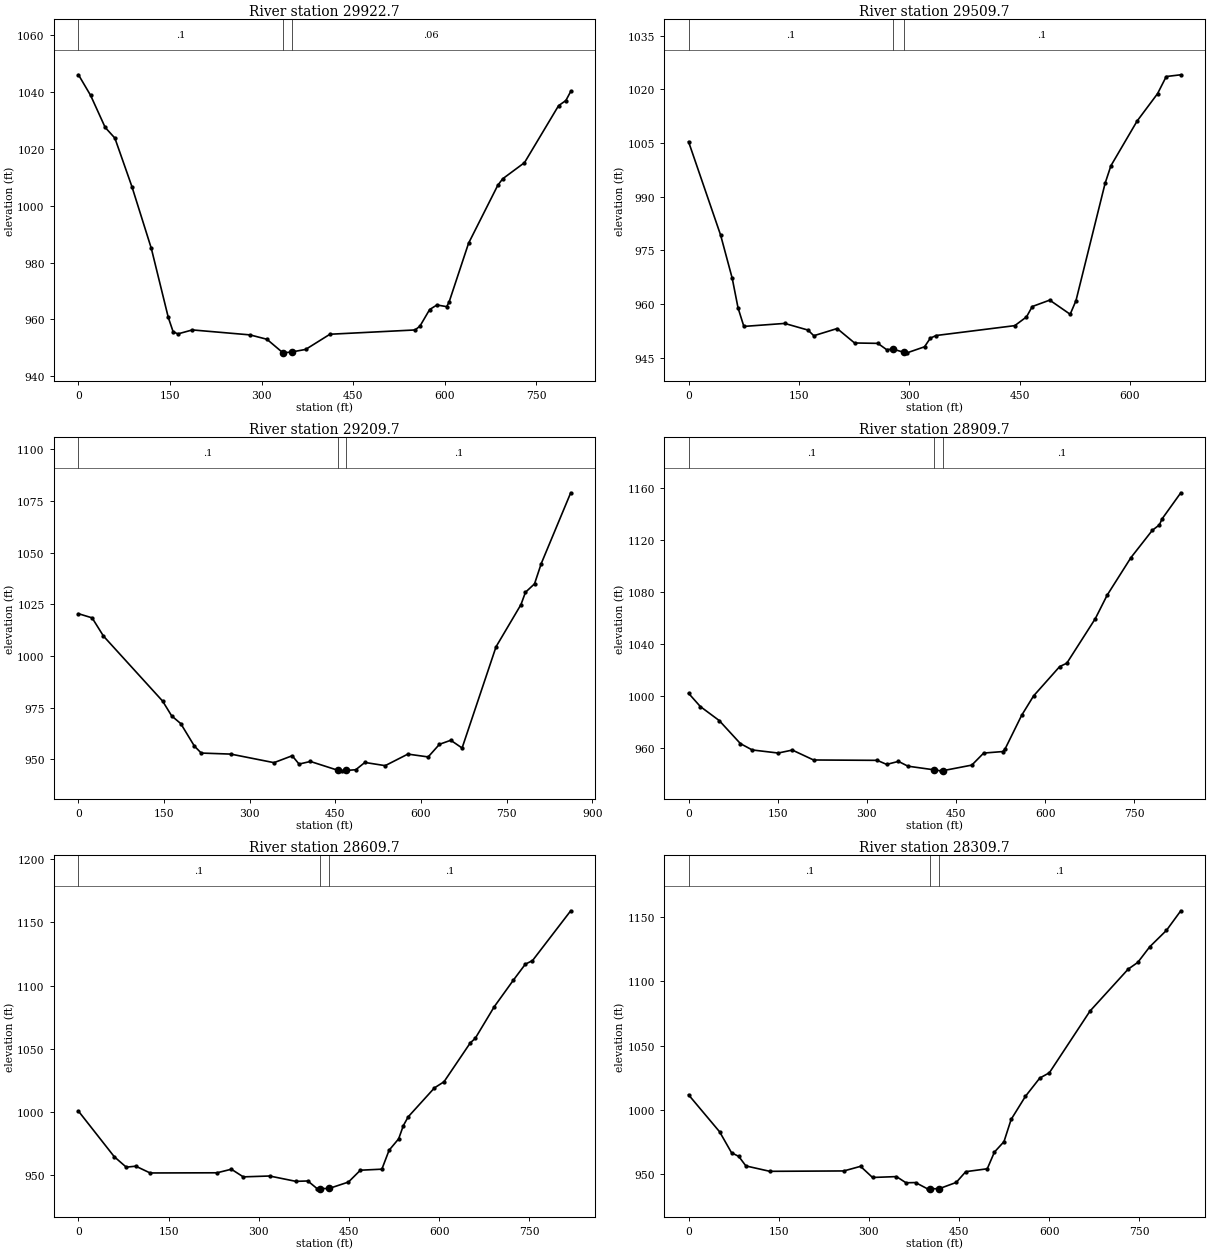
Type RM Length L Ch R = 1 ,29922.7 ,383.8,413,443.4
XS GIS Cut Line= 4
     1751347.354       339203.47     1751382.094      339342.338
     1751536.591      339470.831     1751897.702      339759.025
#Sta/Elev= 30
       0 1046.16    19.9 1038.89    43.7 1027.63    59.6 1023.86    87.5 1006.78
   119.3  985.01   147.1  960.67     155  955.66   162.8  954.89   186.5  956.29
     281  954.54   308.6     953   334.6  948.27   336.2  948.22   349.6  948.54
     372  949.42   411.8  954.77   551.2  956.28   559.2  957.63   575.1  963.48
     587  965.08     603  964.49     607  966.16   638.8  986.82   686.6 1007.21
   694.6 1009.51   730.4 1015.21   786.2 1035.28   798.1 1037.08   806.1 1040.29
#Mann= 3 , 0 , 0
       0      .1       0   334.6    .045       0   349.6     .06       0
Bank Sta=334.6,349.6
XS Rating Curve= 0 ,0
Exp/Cntr=0.3,0.1

Type RM Length L Ch R = 1 ,29509.7 ,303.4,300,299.5
XS GIS Cut Line= 3
     1751302.216      339309.372     1751187.882      339570.596
     1751025.152      339918.507
#Sta/Elev= 30
       0 1005.39    43.6  979.25    59.4  967.15    67.3  958.88    75.2   953.7
   130.7  954.54   162.4  952.68   170.3   951.1     202  953.11   225.7  949.07
   257.4  948.96   269.3   947.2   277.6  947.38   292.6  946.46     297  946.31
   320.8     948   328.7  950.42   336.6  951.16   443.5  953.92   459.4  956.36
   467.3  959.27     491  961.06   518.8   957.1   526.7  960.92   566.3  993.75
   574.2  998.66   609.8 1011.17   637.6 1018.83   649.4 1023.62   669.2 1024.11
#Mann= 3 , 0 , 0
       0      .1       0   277.6    .045       0   292.6      .1       0
Bank Sta=277.6,292.6
XS Rating Curve= 0 ,0
Exp/Cntr=0.3,0.1

Type RM Length L Ch R = 1 ,29209.7 ,289.3,300,309.1
XS GIS Cut Line= 3
     1751033.273      339002.267      1750913.82      339448.588
     1750751.987       339814.64
#Sta/Elev= 30
       0 1020.45    23.9 1018.44    43.8 1009.62   147.4  978.17   163.3     971
   179.2  967.27   203.1  956.38   215.1  953.02   266.9  952.52   342.5  948.38
   374.4  951.72   386.4  947.69   406.3  948.96   454.5  944.68     462  944.42
   469.5  944.62   485.8  944.96   501.7  948.48   537.3  946.93     577  952.52
   612.6  951.15   632.4  957.27   652.2  959.21     672  955.46   731.5 1004.46
   775.1 1024.84     783 1030.82   798.9  1034.9   810.7 1044.74   862.3 1078.96
#Mann= 3 , 0 , 0
       0      .1       0   454.5    .045       0   469.5      .1       0
Bank Sta=454.5,469.5
XS Rating Curve= 0 ,0
Exp/Cntr=0.3,0.1

Type RM Length L Ch R = 1 ,28909.7 ,295.4,300,302.8
XS GIS Cut Line= 3
     1750962.099      338955.468     1750680.195      339267.573
     1750383.347      339546.813
#Sta/Elev= 30
       0 1001.88    19.8  991.68    51.6   980.9    87.3  963.15   107.1  958.29
   150.8  955.92   174.6   958.2   210.3  950.58   317.4   950.3   333.3  947.17
   353.1   949.5     369  945.82   413.1     943   424.6  942.23   428.1  942.37
   476.5  946.64   496.5  955.89   528.4  957.05   532.4  958.97   560.4  984.94
   580.4  999.83   624.3 1022.39   636.3 1024.97   684.3 1059.28   704.2  1077.3
   744.2 1106.18   780.2 1127.18   792.2 1131.38   796.2 1135.71   828.1 1156.03
#Mann= 3 , 0 , 0
       0      .1       0   413.1    .045       0   428.1      .1       0
Bank Sta=413.1,428.1
XS Rating Curve= 0 ,0
Exp/Cntr=0.3,0.1

Type RM Length L Ch R = 1 ,28609.7 ,299.9,300,300.1
XS GIS Cut Line= 3
     1750838.075      338781.694      1750507.41      339023.065
     1750176.516      339264.577
#Sta/Elev= 30
       0 1000.81    59.6  964.75    79.5  956.52    95.4  957.28   119.2  951.92
   230.5  952.06   254.4  954.87   274.2  948.84     318  949.52   361.7  945.29
   381.6  945.59   397.5  939.37   401.9  939.55   416.9  939.65   449.2  944.74
     469   954.1   504.8  954.92   516.8   969.9   532.7   978.9   540.6  989.44
   548.6  996.31   592.3 1019.21   608.2 1024.04     652 1054.86     660 1058.27
   691.8  1083.4   723.6  1104.4   743.5 1117.03   755.4 1119.84     819 1159.24
#Mann= 3 , 0 , 0
       0      .1       0   401.9    .045       0   416.9      .1       0
Bank Sta=401.9,416.9
XS Rating Curve= 0 ,0
Exp/Cntr=0.3,0.1

Type RM Length L Ch R = 1 ,28309.7 ,304.3,300,295.2
XS GIS Cut Line= 3
     1750656.067      338545.379     1750324.324      338785.455
     1749992.582      339025.532
#Sta/Elev= 30
       0  1011.6    51.7  982.75    71.6  966.38    83.5   963.6    95.4  956.16
   135.2  951.95   258.4  952.25   286.2  955.84   306.1  947.16   345.9  947.84
   361.8  943.03   377.7  943.18   397.6   938.3     402  938.34     417  938.41
   445.3  943.28   461.2  951.68     497  953.93   508.9  966.94   524.8  975.07
   536.7  992.39   560.6 1010.47   584.4 1024.65   600.3 1028.75   667.9 1076.84
   731.5 1109.57   747.4 1114.77   767.3 1126.94   795.2 1139.79     819 1155.02
#Mann= 3 , 0 , 0
       0      .1       0     402    .045       0     417      .1       0
Bank Sta=402,417
XS Rating Curve= 0 ,0
Exp/Cntr=0.3,0.1

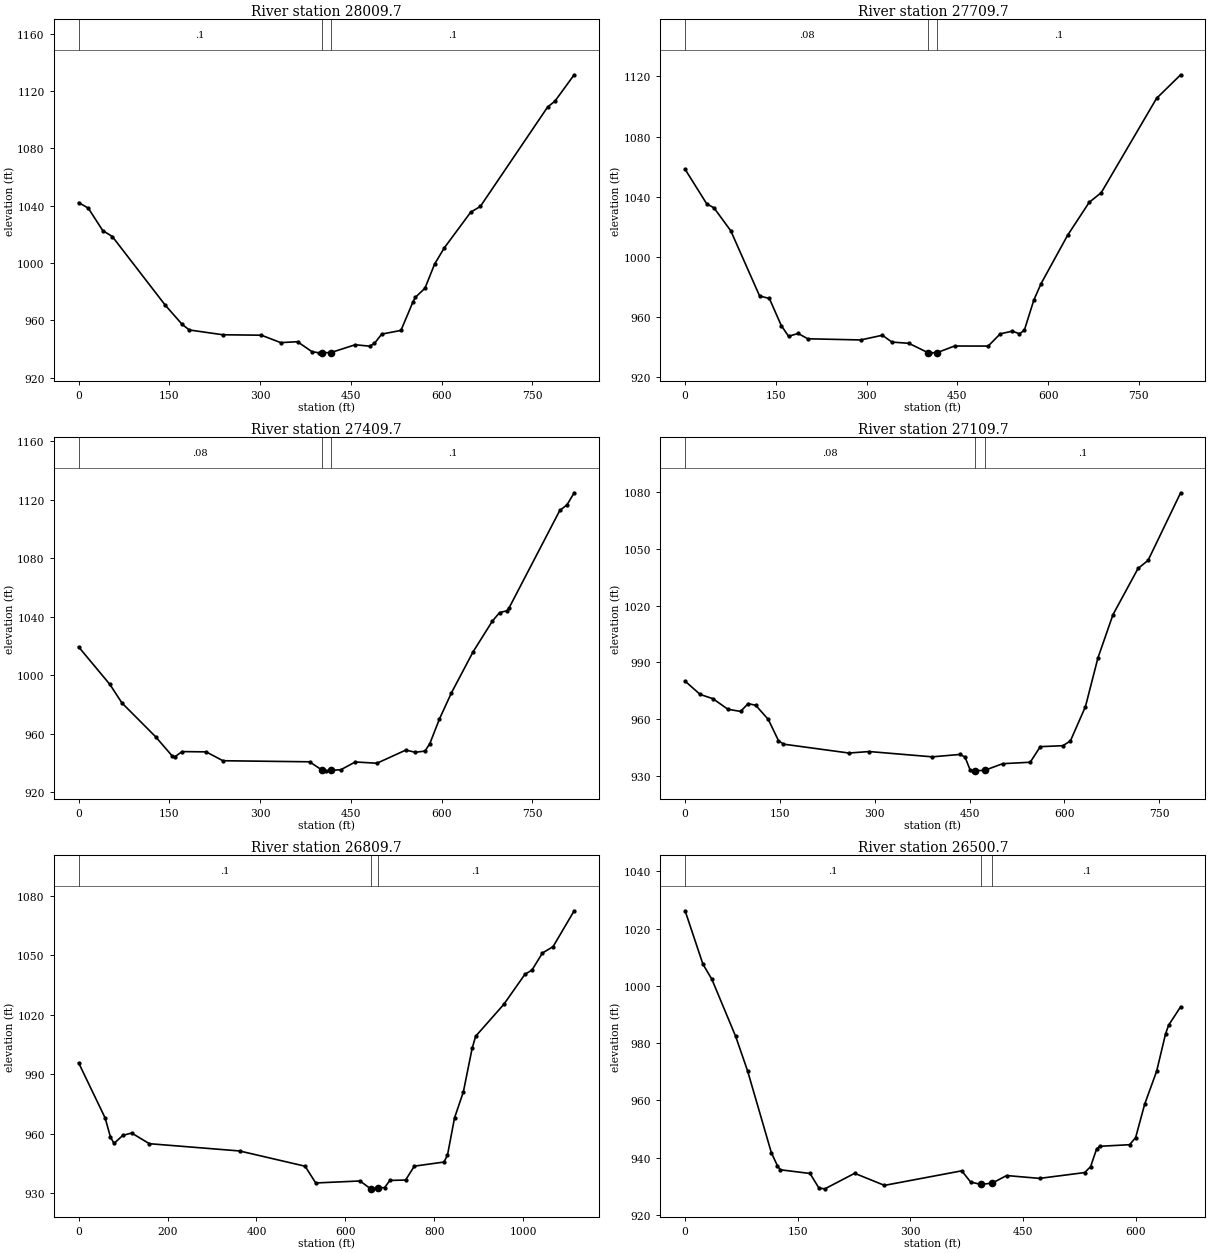
Type RM Length L Ch R = 1 ,28009.7 ,306.9,300,293.5
XS GIS Cut Line= 3
     1750405.865      338261.913     1750126.326       338561.14
     1749852.186      338865.449
#Sta/Elev= 30
       0 1042.06    15.9 1038.21    39.8 1022.55    55.7 1018.38   143.1  970.52
     171  957.14   182.9  953.18   238.5  949.83   302.1  949.53     334  944.35
   361.8  944.98   385.6  938.05   397.6  937.22     402  937.26     417  937.41
   457.2  942.86   481.1  941.87     489  943.82     501  950.29   532.8  952.87
   552.6  972.74   556.6  975.93   572.5  982.35   588.4  999.16   604.3 1010.39
   648.1 1035.37     664 1039.37   775.3 1108.78   787.2 1112.77   819.1 1131.24
#Mann= 3 , 0 , 0
       0      .1       0     402    .045       0     417      .1       0
Bank Sta=402,417
XS Rating Curve= 0 ,0
Exp/Cntr=0.3,0.1

Type RM Length L Ch R = 1 ,27709.7 ,305.5,300,294.5
XS GIS Cut Line= 3
     1750046.205      338039.611     1749870.013      338409.268
     1749693.821      338778.926
#Sta/Elev= 30
       0 1058.19    35.8 1035.15    47.7 1032.55    75.5 1017.24   123.2  973.81
   139.2  972.24     159  954.14     171  947.04   186.9  948.88   202.8  945.36
   290.2  944.58     326   947.7   341.9  943.16   369.7  942.35     402  936.01
   405.5     936     417  936.21   445.3  940.54   500.9   940.5   520.8  948.62
   540.7  950.44   552.6  948.71   560.6  950.96   576.5  971.27   588.4  982.14
   632.1  1014.2   667.9 1036.21   687.8 1042.63   779.2 1105.41     819 1121.11
#Mann= 3 , 0 , 0
       0     .08       0     402    .045       0     417      .1       0
Bank Sta=402,417
XS Rating Curve= 0 ,0
Exp/Cntr=0.3,0.1

Type RM Length L Ch R = 1 ,27409.7 ,309.3,300,291.2
XS GIS Cut Line= 3
     1749672.327       337901.85     1749591.098      338303.212
     1749509.869      338704.575
#Sta/Elev= 30
       0 1019.28    51.7   993.6    71.6  980.95   127.2  957.86     155  944.54
     159  944.16     171  947.69   210.7  947.52   238.5  941.45   381.7  940.72
     402  935.13   409.5  934.54     417  934.89   433.4   935.3   457.2   940.6
     493  939.74   540.7  948.72   556.6  947.22   572.5  948.07   580.5  953.22
   596.4  970.06   616.2  987.92     652 1015.96   683.8 1036.94   695.8 1042.75
   707.7 1043.95   711.7 1046.18   795.2 1112.55   807.1 1116.39     819 1124.66
#Mann= 3 , 0 , 0
       0     .08       0     402    .045       0     417      .1       0
Bank Sta=402,417
XS Rating Curve= 0 ,0
Exp/Cntr=0.3,0.1

Type RM Length L Ch R = 1 ,27109.7 ,302.8,300,297.3
XS GIS Cut Line= 3
     1749196.313       337828.47     1749294.748      338284.615
     1749356.035      338595.831
#Sta/Elev= 30
       0  980.17    23.9  973.17    43.9  970.96    67.8  965.37    87.8  964.25
    99.7  968.35   111.7  967.48   131.6  960.02   147.6  948.93   155.6  947.02
   259.2  942.34   291.2  943.13   390.9  940.34   434.7   941.6   442.7  940.25
   450.7  933.57   454.7  932.97   459.1     933   474.1  933.27   502.3  936.73
   545.9   937.5   561.8   945.7   597.5   946.2   609.4  948.69   633.2  966.75
     653  992.43   676.8  1015.2   716.4 1039.49   732.3 1043.76   783.8 1079.34
#Mann= 3 , 0 , 0
       0     .08       0   459.1    .045       0   474.1      .1       0
Bank Sta=459.1,474.1
XS Rating Curve= 0 ,0
Exp/Cntr=0.3,0.1

Type RM Length L Ch R = 1 ,26809.7 ,332.9,308.9,284.9
XS GIS Cut Line= 5
     1749081.729      337786.803     1748933.863      338156.091
     1749022.116      338408.132     1749067.841      338554.164
     1749294.087        338746.3
#Sta/Elev= 30
       0  995.73    59.7  967.89    71.6   958.3    79.6  955.09    99.4  959.16
   119.3  960.34   159.1  954.96     362   951.3   509.4  943.61   533.3  935.16
     633  936.17   656.9   932.2   657.3  932.21   672.3  932.52   688.4  932.87
   700.2  936.45   735.5  936.63   755.1  943.64   821.8  945.71   829.7  949.15
   845.6  968.03   865.4  981.04   885.1 1002.97   893.1 1009.14   956.4 1025.22
  1003.9 1040.37  1019.7  1042.5  1043.4 1051.13  1067.2 1054.32  1114.7 1072.41
#Mann= 3 , 0 , 0
       0      .1       0   657.3    .045       0   672.3      .1       0
Bank Sta=657.3,672.3
XS Rating Curve= 0 ,0
Exp/Cntr=0.3,0.1

Type RM Length L Ch R = 1 ,26500.7 ,289.6,291.1,292.3
XS GIS Cut Line= 3
     1748433.787      338545.428     1748823.049        338618.4
     1749079.993      338677.428
#Sta/Elev= 30
       0 1026.19    23.8 1007.51    35.6  1002.3    67.3  982.35    83.2  970.28
   114.8  941.77   122.8  937.24   126.7  935.78   166.3  934.48   178.2  929.38
   186.1  929.12   225.7  934.54   265.4  930.33   368.3  935.41   380.2  931.47
   394.1  930.66   409.1  931.14     428  933.76   471.9  932.77   531.9   934.8
   539.8  936.85   547.8  943.01   551.8  943.97   591.8  944.53   599.8  947.02
   611.8  958.66   627.7  970.14   639.7  983.29   643.7  986.25   659.7  992.69
#Mann= 3 , 0 , 0
       0      .1       0   394.1    .045       0   409.1      .1       0
Bank Sta=394.1,409.1
XS Rating Curve= 0 ,0
Exp/Cntr=0.3,0.1

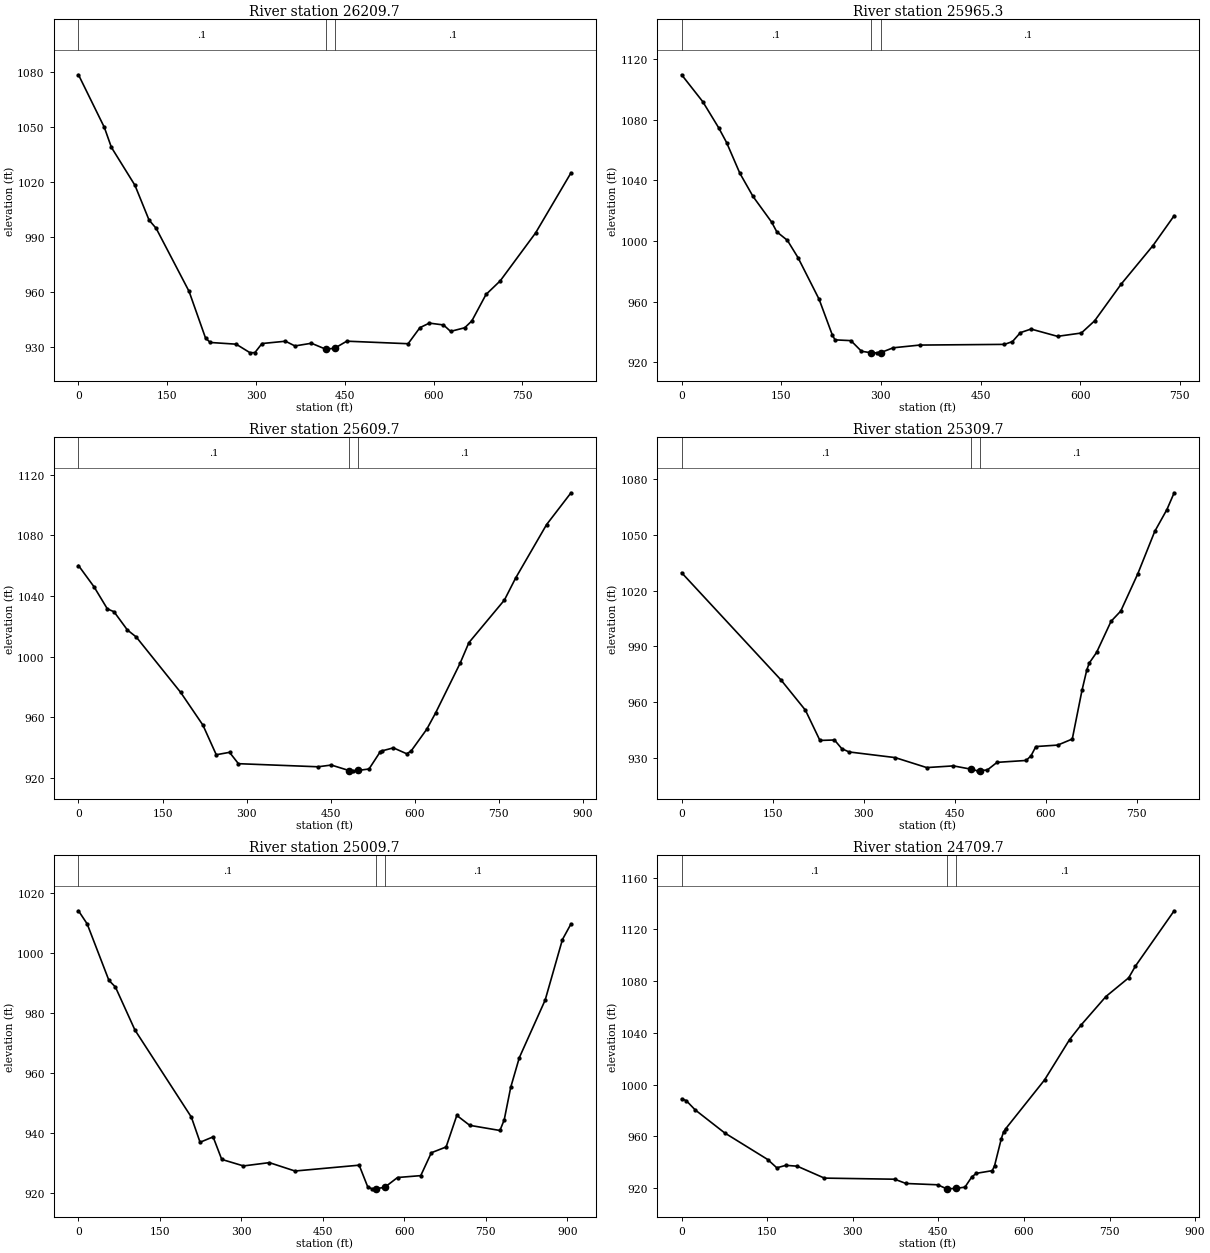
Type RM Length L Ch R = 1 ,26209.7 ,250.5,244.3,237.7
XS GIS Cut Line= 3
     1748399.682      338799.188     1748810.874      338907.654
     1749201.944      339019.389
#Sta/Elev= 30
       0  1078.3    43.7 1049.63    55.6 1038.77    95.4 1018.08   119.2  999.15
   131.2  994.64   186.8  960.29   214.6  934.88   222.6  932.45   266.3  931.52
   290.1   926.8   298.1  926.97     310  931.87   349.7  933.13   365.6  930.56
   393.5  932.02   417.8  928.77   432.8  929.32   453.2  933.15   556.8  931.77
   576.8  940.53   592.7     943   616.6  941.99   628.6  938.49   652.5  940.47
   664.5   944.2   688.4   958.6   712.4  966.01   772.2  992.15     832 1024.88
#Mann= 3 , 0 , 0
       0      .1       0   417.8    .045       0   432.8      .1       0
Bank Sta=417.8,432.8
XS Rating Curve= 0 ,0
Exp/Cntr=0.3,0.1

Type RM Length L Ch R = 1 ,25965.3 ,351.3,355.7,356.7
XS GIS Cut Line= 3
     1748451.521      339135.761     1748797.842      339132.771
     1749192.023      339106.939
#Sta/Elev= 30
       0 1109.64    31.8 1091.91    55.7 1074.73    67.7 1064.93    87.6 1044.74
   107.5 1029.38   135.4 1012.54   143.3 1006.06   159.2 1000.46   175.2  989.05
     207  961.54   226.9  937.96   230.9  934.84   254.8  934.33   270.7  927.32
     285  926.34   294.6  926.28     300   926.5   318.5  929.61   358.3   931.4
     486  931.86     498  933.71   509.9  939.59   525.9  941.97   565.8  937.16
   601.7  939.35   621.7   947.4   661.6  971.58   709.4  996.95   741.4 1016.71
#Mann= 3 , 0 , 0
       0      .1       0     285    .045       0     300      .1       0
Bank Sta=285,300
XS Rating Curve= 0 ,0
Exp/Cntr=0.3,0.1

Type RM Length L Ch R = 1 ,25609.7 ,294.6,300,308
XS GIS Cut Line= 4
      1748434.16      339357.984     1748661.661      339427.498
     1748914.117      339438.117     1749302.216      339434.372
#Sta/Elev= 30
       0  1060.1    27.8 1046.03    51.5  1031.5    63.4 1029.61    87.2  1017.6
   103.1 1012.93   182.4  976.35     222  954.81   245.8  935.27   269.5  936.86
   285.3  929.37   427.4  927.33   451.1  928.47   483.1   924.8   490.6  924.65
   498.1  924.88   518.3  925.87   538.1  937.09     542  937.87   561.8  939.81
   585.6  935.91   593.5  937.76   621.3  952.07   637.1  962.83   680.7  995.51
   696.5 1009.21   759.9 1037.33   779.7  1051.7   835.1 1087.09   878.7 1108.09
#Mann= 3 , 0 , 0
       0      .1       0   483.1    .045       0   498.1      .1       0
Bank Sta=483.1,498.1
XS Rating Curve= 0 ,0
Exp/Cntr=0.3,0.1

Type RM Length L Ch R = 1 ,25309.7 ,300.7,300,301.6
XS GIS Cut Line= 3
     1748377.616      339488.358     1748816.313      339692.511
     1749112.979      339831.942
#Sta/Elev= 30
       0 1029.74     164  971.83     204  955.62   227.9  939.32   251.9  939.55
   263.9  934.88   275.9  933.11   351.9  930.06   403.9  924.68   447.9  925.59
   476.4  923.85   487.9  922.92   491.4  923.02   503.9  923.41   519.8  927.49
   567.8  928.52   575.8  931.03   583.8  936.02   619.8   936.8   643.8  940.07
   659.8  966.31   667.8  977.42   671.8  981.05   683.8  986.73   707.7 1003.54
   723.7 1009.07   751.7 1029.11   779.7 1052.01   799.7 1063.76   811.7 1072.84
#Mann= 3 , 0 , 0
       0      .1       0   476.4    .045       0   491.4      .1       0
Bank Sta=476.4,491.4
XS Rating Curve= 0 ,0
Exp/Cntr=0.3,0.1

Type RM Length L Ch R = 1 ,25009.7 ,277.1,300,321.2
XS GIS Cut Line= 5
     1748336.159      339552.854     1748472.354      339851.039
     1748683.788      339937.761     1748798.743      339995.136
     1749019.229      339967.359
#Sta/Elev= 30
       0 1014.14      16 1009.76      56  990.92      68  988.69   103.9  974.35
   207.9  945.24   223.9  936.86   247.9  938.66   263.8  931.14   303.8  928.96
   351.5  930.06   398.7  927.26   516.9  929.21   532.7  921.95   540.6  921.31
   548.8   921.4   563.8   921.8   587.5  925.09   630.3  925.72   649.8  933.36
     677  935.29   696.7  945.82   720.5  942.51   776.1  940.79     784  944.34
   795.9  955.16   811.8   965.1   859.4  984.33   891.2 1004.53     907 1009.77
#Mann= 3 , 0 , 0
       0      .1       0   548.8    .045       0   563.8      .1       0
Bank Sta=548.8,563.8
XS Rating Curve= 0 ,0
Exp/Cntr=0.3,0.1

Type RM Length L Ch R = 1 ,24709.7 ,293.8,300,306.2
XS GIS Cut Line= 3
     1748352.563      339613.192     1748452.648       340075.15
     1748528.337      340458.328
#Sta/Elev= 30
       0     989     7.9  987.67    23.8  980.42    75.5  962.63   150.9  942.08
   166.8  935.68   182.7  937.59   202.6  936.94   250.2  927.72   373.4  926.87
   393.2  923.57   448.8  922.56   464.7  919.43   465.2  919.44   480.2  919.74
   496.6  920.74   508.6  928.65   516.5  931.41   544.4  933.47   548.4   937.1
   560.4  958.29   564.3  963.42   568.3  966.04   636.1 1003.58   679.9 1034.72
   699.8 1045.84   743.7 1068.06   783.6 1082.52   795.5 1091.62   863.3 1134.31
#Mann= 3 , 0 , 0
       0      .1       0   465.2    .045       0   480.2      .1       0
Bank Sta=465.2,480.2
XS Rating Curve= 0 ,0
Exp/Cntr=0.3,0.1

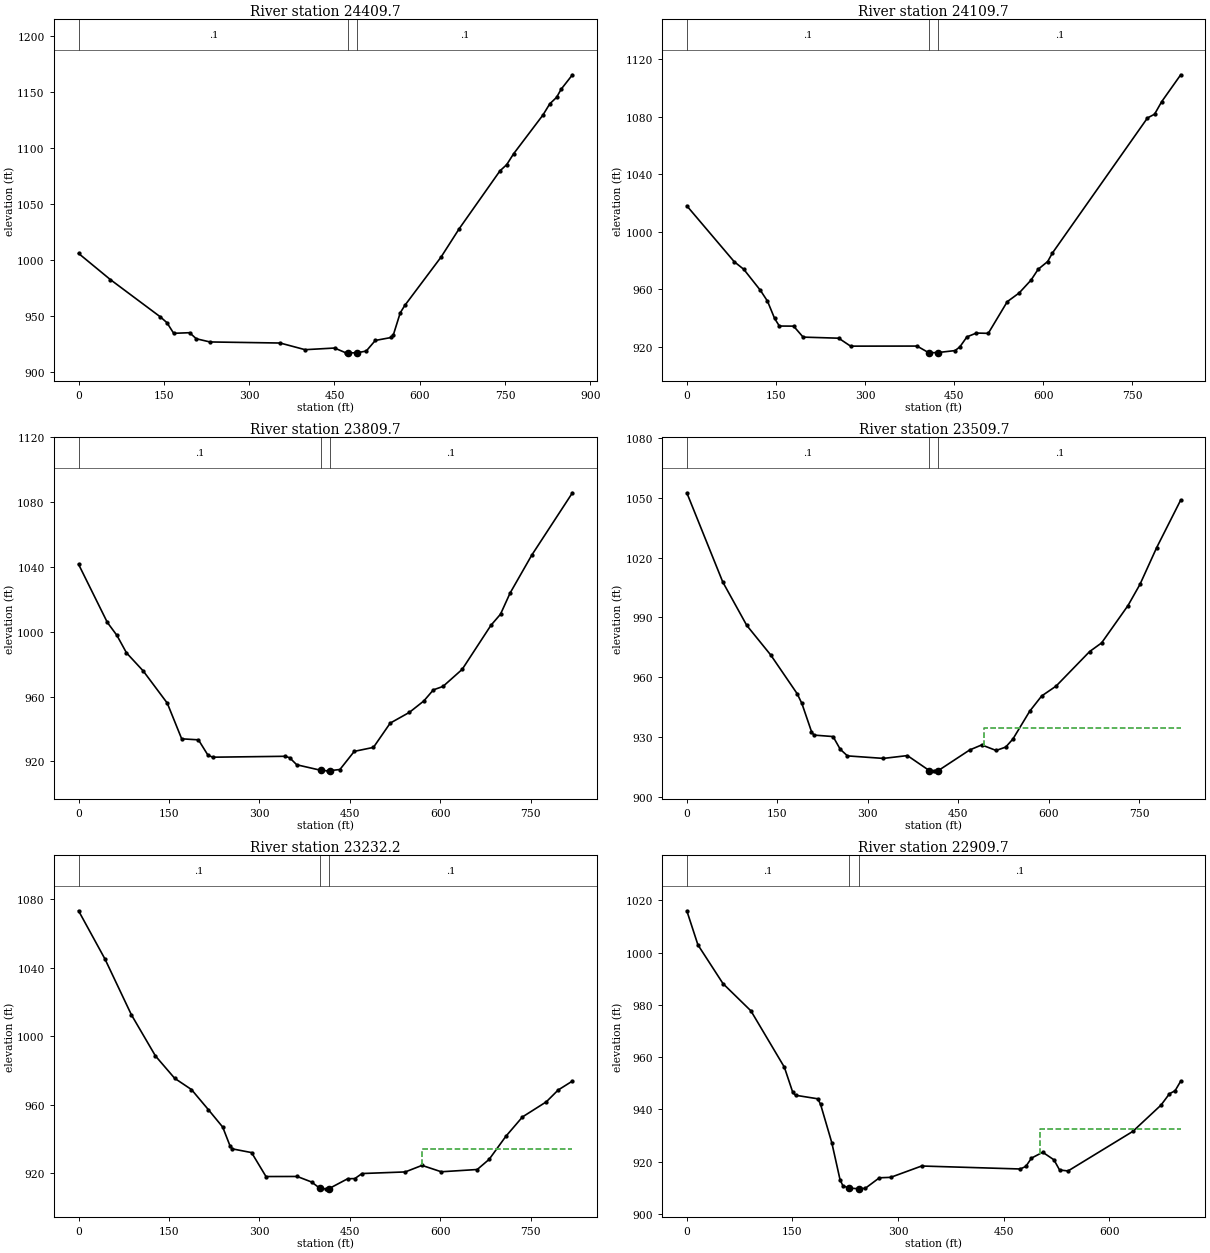
Type RM Length L Ch R = 1 ,24409.7 ,290,300,312.9
XS GIS Cut Line= 3
     1748191.931      339596.102     1748156.896      340076.772
     1748128.604       340462.15
#Sta/Elev= 30
       0 1006.22    55.8   982.9   143.4  949.73   155.3  944.45   167.3  934.89
   195.2  935.44   207.1  930.02     231  927.19   354.5  926.23   398.3  920.28
   450.1  921.76     470  917.47   474.4  917.47   489.4  917.49   505.8  919.06
   521.8  928.54   549.7  931.16   553.6  933.67   565.6  953.17   573.6  959.75
   637.3 1002.89   669.2 1028.18   740.9 1079.86   752.8 1085.42   764.8 1095.03
   816.6 1129.77   828.5 1139.69   840.5 1145.48   848.4 1152.67   868.4 1165.63
#Mann= 3 , 0 , 0
       0      .1       0   474.4    .045       0   489.4      .1       0
Bank Sta=474.4,489.4
XS Rating Curve= 0 ,0
Exp/Cntr=0.3,0.1

Type RM Length L Ch R = 1 ,24109.7 ,296.1,300,300.5
XS GIS Cut Line= 3
     1748116.556      339562.635     1747908.839      339922.551
     1747654.968      340252.013
#Sta/Elev= 30
       0  1018.1    79.9  979.18    95.9  973.93   123.9  959.28   135.8  951.78
   147.8  939.73   155.8  934.46   179.8  934.39   195.8  926.75   255.7     926
   275.7  920.47   387.6  920.52   407.6  915.81   408.1  915.82   423.1  916.03
   451.6  917.38   459.6  919.92   471.6  926.92   487.5  929.58   507.5  929.37
   539.5  951.42   559.5  957.46   579.5  966.42   591.5  973.96   607.5  979.34
   615.5  985.25   775.5 1079.23   787.5 1081.87   799.5 1090.61   831.5 1109.28
#Mann= 3 , 0 , 0
       0      .1       0   408.1    .045       0   423.1      .1       0
Bank Sta=408.1,423.1
XS Rating Curve= 0 ,0
Exp/Cntr=0.3,0.1

Type RM Length L Ch R = 1 ,23809.7 ,301.5,300,298.5
XS GIS Cut Line= 3
     1747918.349      339444.798     1747660.416      339762.856
     1747402.484      340080.914
#Sta/Elev= 30
       0  1041.7    47.7 1005.82    63.6  997.81    79.5     987   107.3  975.81
   147.1  955.98     171  933.94   198.8  933.31   214.7  923.77   222.6  922.59
   341.9  923.15   349.9  922.32   361.8  917.92     402  914.48   413.5  914.17
     417  914.31   433.4  914.99   457.2  926.19     489  928.65   516.8  943.63
   548.6  950.27   572.5   957.3   588.4  964.17   604.3  966.27   636.1   976.8
   683.8    1004   699.7 1010.88   715.6 1023.93   751.4 1047.27     819 1085.83
#Mann= 3 , 0 , 0
       0      .1       0     402    .045       0     417      .1       0
Bank Sta=402,417
XS Rating Curve= 0 ,0
Exp/Cntr=0.3,0.1

Type RM Length L Ch R = 1 ,23509.7 ,276.5,277.4,276.6
XS GIS Cut Line= 3
     1747653.115      339251.962     1747417.557      339586.929
     1747181.999      339921.896
#Sta/Elev= 30
       0 1052.53    59.6 1007.77    99.4  985.99   139.2  971.12   182.9  951.76
   190.8  946.83   206.7  932.74   210.7  930.96   242.5  930.22   254.4  923.85
   266.4  920.52     326  919.26   365.8  920.67     402  913.17   409.5  913.02
     417  913.14   469.1   923.5     489  926.02   512.9  923.24   528.8  924.94
   540.7  928.97   568.5   942.9   588.4  950.58   612.3  955.53   667.9  972.85
   687.8  977.21   731.5  995.92   751.4 1006.56   779.2 1025.07     819  1048.9
#Mann= 3 , 0 , 0
       0      .1       0     402    .045       0     417      .1       0
#XS Ineff= 2 , 0
                          492.93          934.48
Permanent Ineff=
       F       F
Bank Sta=402,417
XS Rating Curve= 0 ,0
Exp/Cntr=0.3,0.1

Type RM Length L Ch R = 1 ,23232.2 ,335.7,322.6,310.8
XS GIS Cut Line= 4
     1747459.263      339092.931     1747206.729      339406.595
      1747061.08      339630.146     1747052.216      339779.859
#Sta/Elev= 30
       0 1073.12    43.9 1044.92    87.7 1012.42   127.6  988.41   159.5  975.36
   187.4  968.79   215.3  957.11   239.2   946.9   251.2  936.04   255.2  934.18
   287.1  932.01     311  918.04   362.8  918.08   386.7  914.84   400.2  911.23
   410.6  910.86   415.2  910.92   446.5  916.74   458.4  916.85   470.4  919.79
   542.1  920.73   569.9  924.54   601.8  920.82   661.5  922.14   681.3  928.08
     709  941.51   736.6  952.83   776.1  961.63   795.8  968.53   819.5  973.76
#Mann= 3 , 0 , 0
       0      .1       0   400.2    .045       0   415.2      .1       0
#XS Ineff= 2 , 0
                          569.81          933.86
Permanent Ineff=
       F       F
Bank Sta=400.2,415.2
XS Rating Curve= 0 ,0
Exp/Cntr=0.3,0.1

Type RM Length L Ch R = 1 ,22909.7 ,309.1,300,289.3
XS GIS Cut Line= 3
     1746942.841      339031.595     1746924.446      339268.282
        1746897.      339731.226
#Sta/Elev= 30
       0 1016.01    15.8 1002.94    51.4  988.12      91   977.7   138.5  956.12
   150.4  946.51   154.3  945.39     186  944.03   189.9   941.9   205.8  927.26
   217.6  912.98   221.6  910.76   229.9  909.87   244.9  909.56   253.4  909.77
   273.4  913.79   289.4  913.96   333.4   918.3   473.3  917.16   481.3  918.14
   489.3  921.32   505.3  923.57   521.2  920.67   529.2  916.79   541.2   916.4
   633.2  931.55   673.2  941.61   685.2  945.96   693.2  947.12   701.2  950.79
#Mann= 3 , 0 , 0
       0      .1       0   229.9    .045       0   244.9      .1       0
#XS Ineff= 2 , 0
                          501.07          932.29
Permanent Ineff=
       F       F
Bank Sta=229.9,244.9
XS Rating Curve= 0 ,0
Exp/Cntr=0.3,0.1