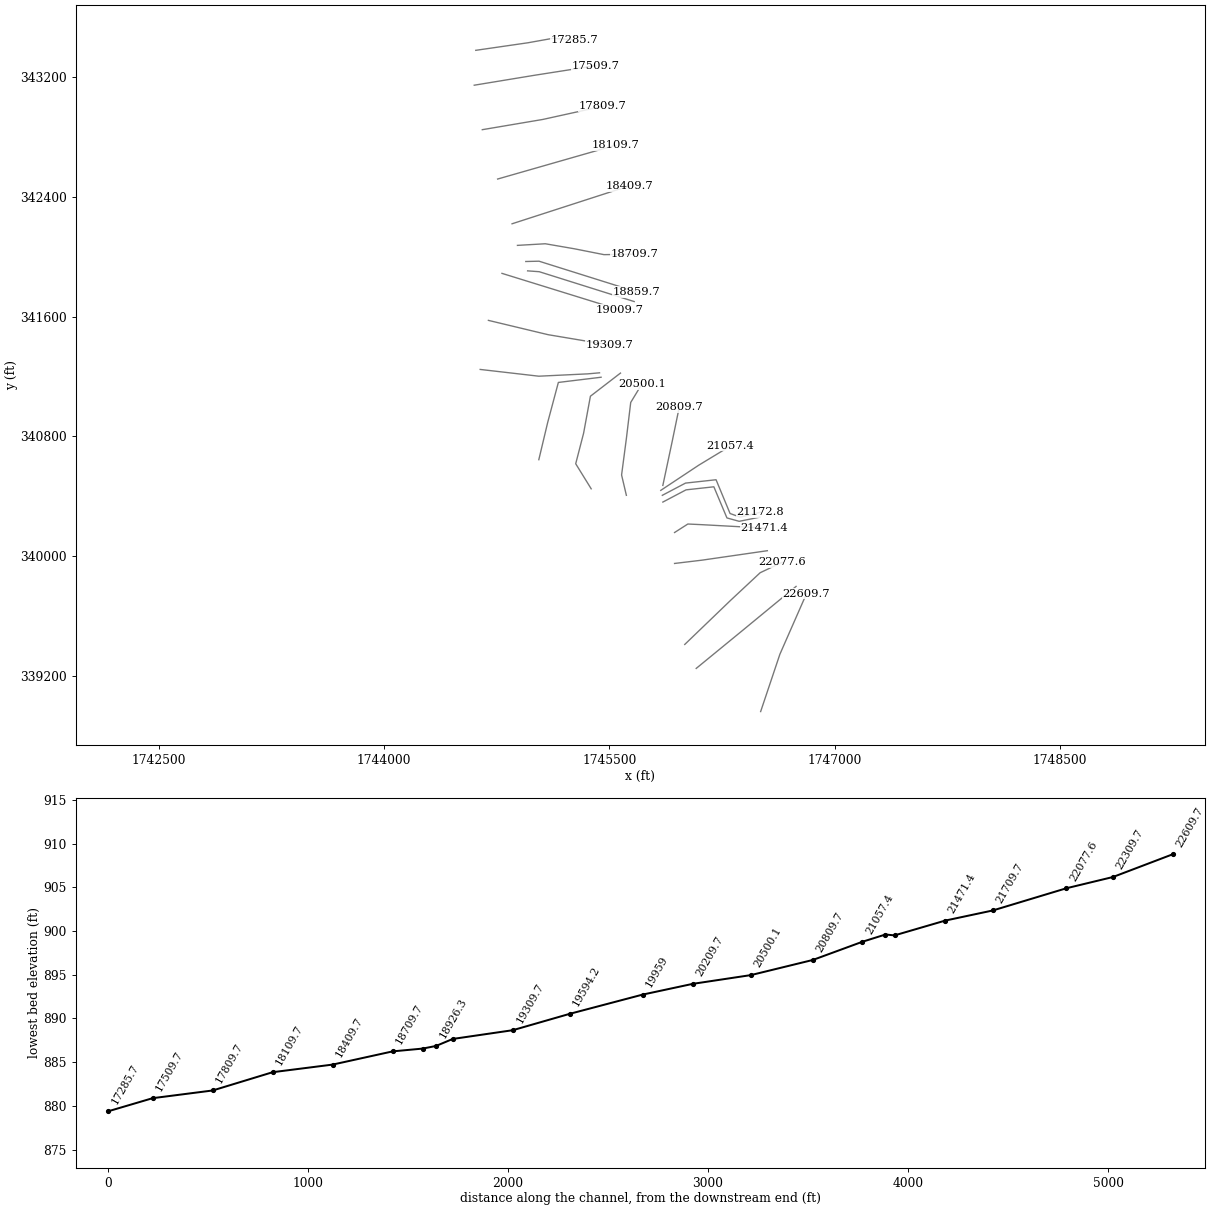
HEC-RAS study SPLAURFK.prj: SPLAURFK

--- SPLAURFK.g01 (geometry) --- (continued)

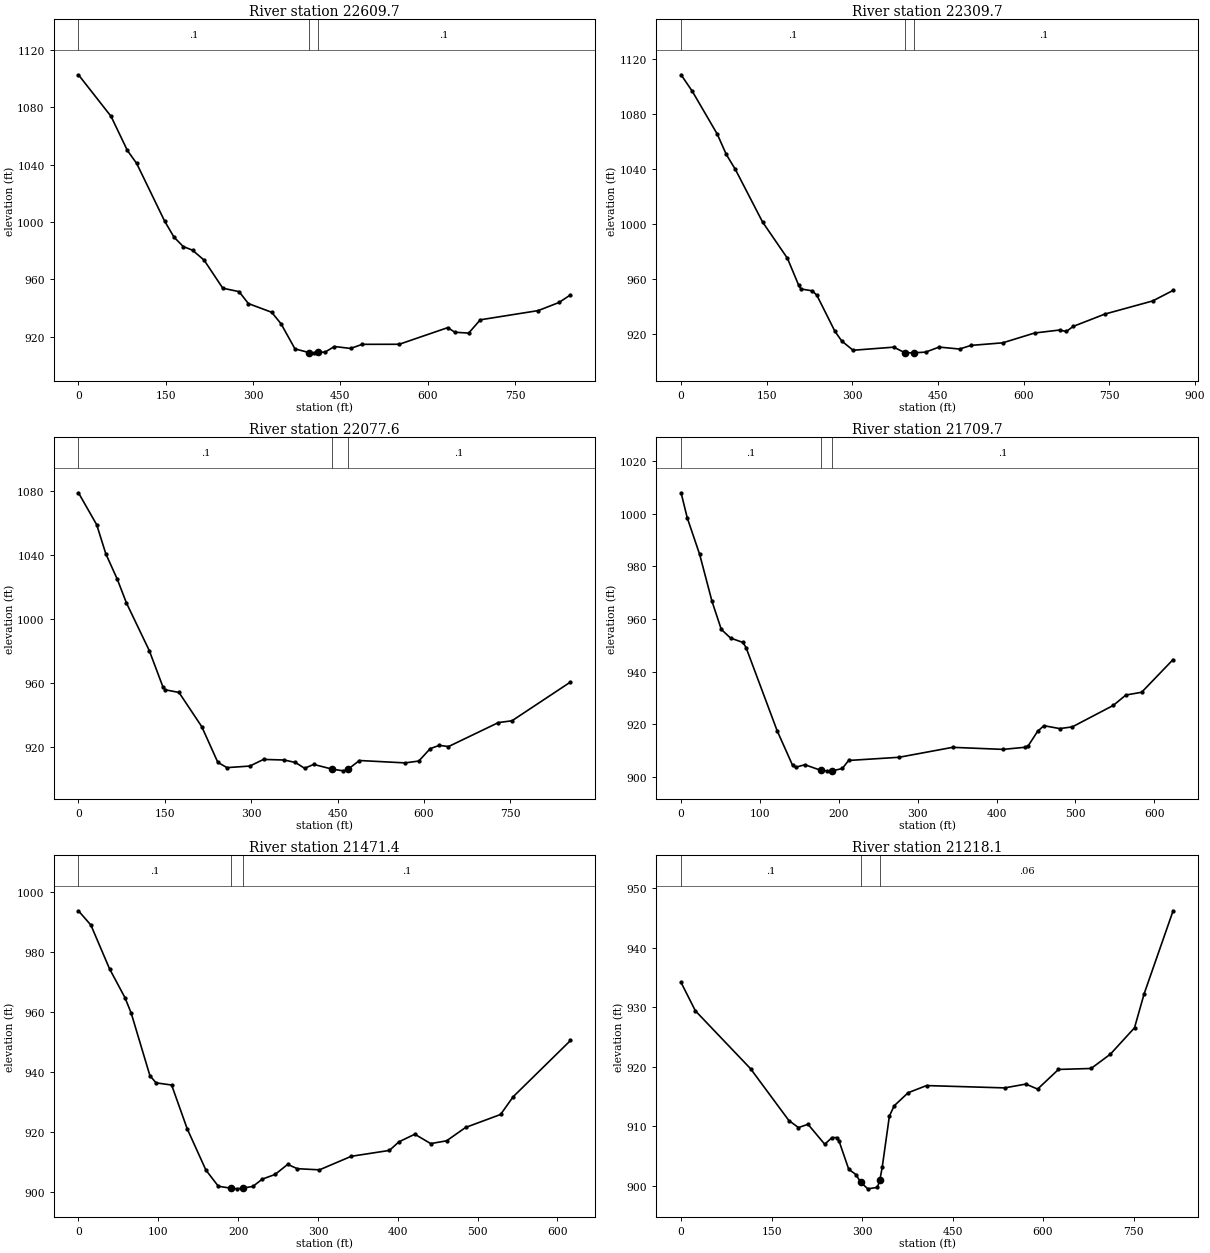
Type RM Length L Ch R = 1 ,22609.7 ,312.7,300,289.4
XS GIS Cut Line= 3
     1746507.658      338962.997     1746635.987      339345.947
     1746813.287      339750.114
#Sta/Elev= 30
       0 1102.59      56  1073.6      84 1049.86     100  1040.8     148 1000.61
     164  989.49     180  982.87   195.9  980.33   215.9  973.36   247.9  953.84
   275.9  951.43   291.9  943.12   331.9  937.05   347.9  929.08   371.9  911.55
   396.4  908.92   403.9  908.78   411.4  909.05   423.8  909.34   439.7  913.19
   467.5  911.84   487.4  914.71     551  914.75   634.5  926.37   646.4  923.15
   670.3  922.53   690.2   931.8   789.6  938.21   825.4  943.87   845.2  949.17
#Mann= 3 , 0 , 0
       0      .1       0   396.4    .045       0   411.4      .1       0
Bank Sta=396.4,411.4
XS Rating Curve= 0 ,0
Exp/Cntr=0.3,0.1

Type RM Length L Ch R = 1 ,22309.7 ,230.3,232,233.7
XS GIS Cut Line= 3
     1746078.368      339251.116     1746387.665      339504.949
     1746743.624      339798.517
#Sta/Elev= 30
       0 1108.79    19.8 1096.67    63.4 1065.52    79.2  1050.7    95.1  1039.8
   142.6 1001.56   186.2  975.08     206  955.34     210   952.7   229.8  951.34
   237.7  948.16   269.4  921.82   281.3   914.8   301.1  908.05   372.4  910.31
   392.2  906.17   392.6  906.18   407.6  906.22     428  906.68   451.8  910.37
   487.6  908.94   507.5  911.58   563.2  913.47   618.9  920.61   662.6  922.79
   674.6  921.73   686.5  925.42   742.2  934.44   825.7  943.98   861.5  951.67
#Mann= 3 , 0 , 0
       0      .1       0   392.6    .045       0   407.6      .1       0
Bank Sta=392.6,407.6
XS Rating Curve= 0 ,0
Exp/Cntr=0.3,0.1

Type RM Length L Ch R = 1 ,22077.6 ,382.1,368,354.4
XS GIS Cut Line= 4
     1746001.961      339411.048      1746307.62      339705.643
     1746504.574      339889.934     1746649.438      339958.678
#Sta/Elev= 30
       0 1079.12    31.7 1059.08    47.6 1040.79    67.4    1025    83.3 1010.12
     123  980.24   146.8  957.39   150.8  955.67   174.6  954.01   214.2  932.55
     242  910.25   257.9   906.9   297.6  907.88   321.4  912.04   357.1  911.68
   376.9  910.13   392.8  906.48   408.6  908.92   441.2   905.9   460.2  904.89
   468.2   905.9     488  911.36   567.3  909.87   591.1  911.03     611  918.83
   626.8  920.85   642.7   920.1   729.4  935.14   752.9  936.24   854.6  960.54
#Mann= 3 , 0 , 0
       0      .1       0   441.2    .045       0   468.2      .1       0
Bank Sta=441.2,468.2
XS Rating Curve= 0 ,0
Exp/Cntr=0.3,0.1

Type RM Length L Ch R = 1 ,21709.7 ,242,238.3,233.8
XS GIS Cut Line= 3
      1745934.16      339951.734     1746117.327       339973.77
     1746552.216      340036.803
#Sta/Elev= 30
       0 1007.98     7.8  998.49    23.6  984.54    39.2  966.75      51  956.08
    62.8  952.78    78.5  951.12    82.4  949.19   121.7  917.67   141.3   904.5
   145.2  903.71     157  904.67     177  902.56   184.5  902.35     192  902.35
   204.5  903.25   212.4  906.29   276.4   907.5   344.3  911.28   408.2   910.5
   436.2   911.3   440.2  911.87   452.1  917.37   460.1   919.5   480.1   918.4
   496.1  919.05     548   927.2     564  931.15     584   932.2   623.9  944.63
#Mann= 3 , 0 , 0
       0      .1       0     177    .045       0     192      .1       0
Bank Sta=177,192
XS Rating Curve= 0 ,0
Exp/Cntr=0.3,0.1

Type RM Length L Ch R = 1 ,21471.4 ,249.7,253.2,256.9
XS GIS Cut Line= 4
      1745934.16      340158.331      1746022.59      340214.977
     1746119.924      340210.414     1746533.118      340187.845
#Sta/Elev= 30
       0  993.82    15.6  989.04    38.9  974.51    58.3  964.85    66.1  959.69
    89.5   938.9    97.2   936.5   116.7  935.77   136.2   921.2   159.6  907.46
   175.2  902.05   190.8  901.41   198.6  901.19   205.8  901.46   218.4  901.98
   230.3  904.44   246.2  905.97   262.1  909.34   274.1   907.9   301.9  907.52
   341.7  912.03   389.5  913.99   401.4  916.85   421.3  919.39   441.2  916.26
   461.1  917.19     485  921.65   528.7  925.96   544.6   931.9   616.3  950.61
#Mann= 3 , 0 , 0
       0      .1       0   190.8    .045       0   205.8      .1       0
Bank Sta=190.8,205.8
XS Rating Curve= 0 ,0
Exp/Cntr=0.3,0.1

Type RM Length L Ch R = 1 ,21218.1 ,45.3,45.3,45.3
XS GIS Cut Line= 6
     1745856.035      340361.456     1746010.549      340443.053
     1746195.898      340463.421     1746283.118      340255.553
     1746364.716      340232.984     1746501.868      340260.761
#Sta/Elev= 30
       0  934.15    23.8  929.38   115.2  919.67   178.7  910.97   194.6  909.79
   210.4  910.34   238.2  906.98   250.1  908.11     258  908.11     262  907.48
   277.9  902.79   289.8   901.9   297.7   900.6   309.6   899.5   325.5  899.75
   329.5  900.99   333.4  903.11   345.3  911.72   353.3  913.45   376.4  915.64
   406.9  916.84   536.3  916.45   571.5  917.09     591  916.25   625.6  919.55
   679.7  919.71   711.7  922.12   751.6  926.54   767.6  932.26   815.6  946.19
#Mann= 3 , 0 , 0
       0      .1       0   297.7    .045       0   329.5     .06       0
Bank Sta=297.7,329.5
XS Rating Curve= 0 ,0
Exp/Cntr=0.3,0.1

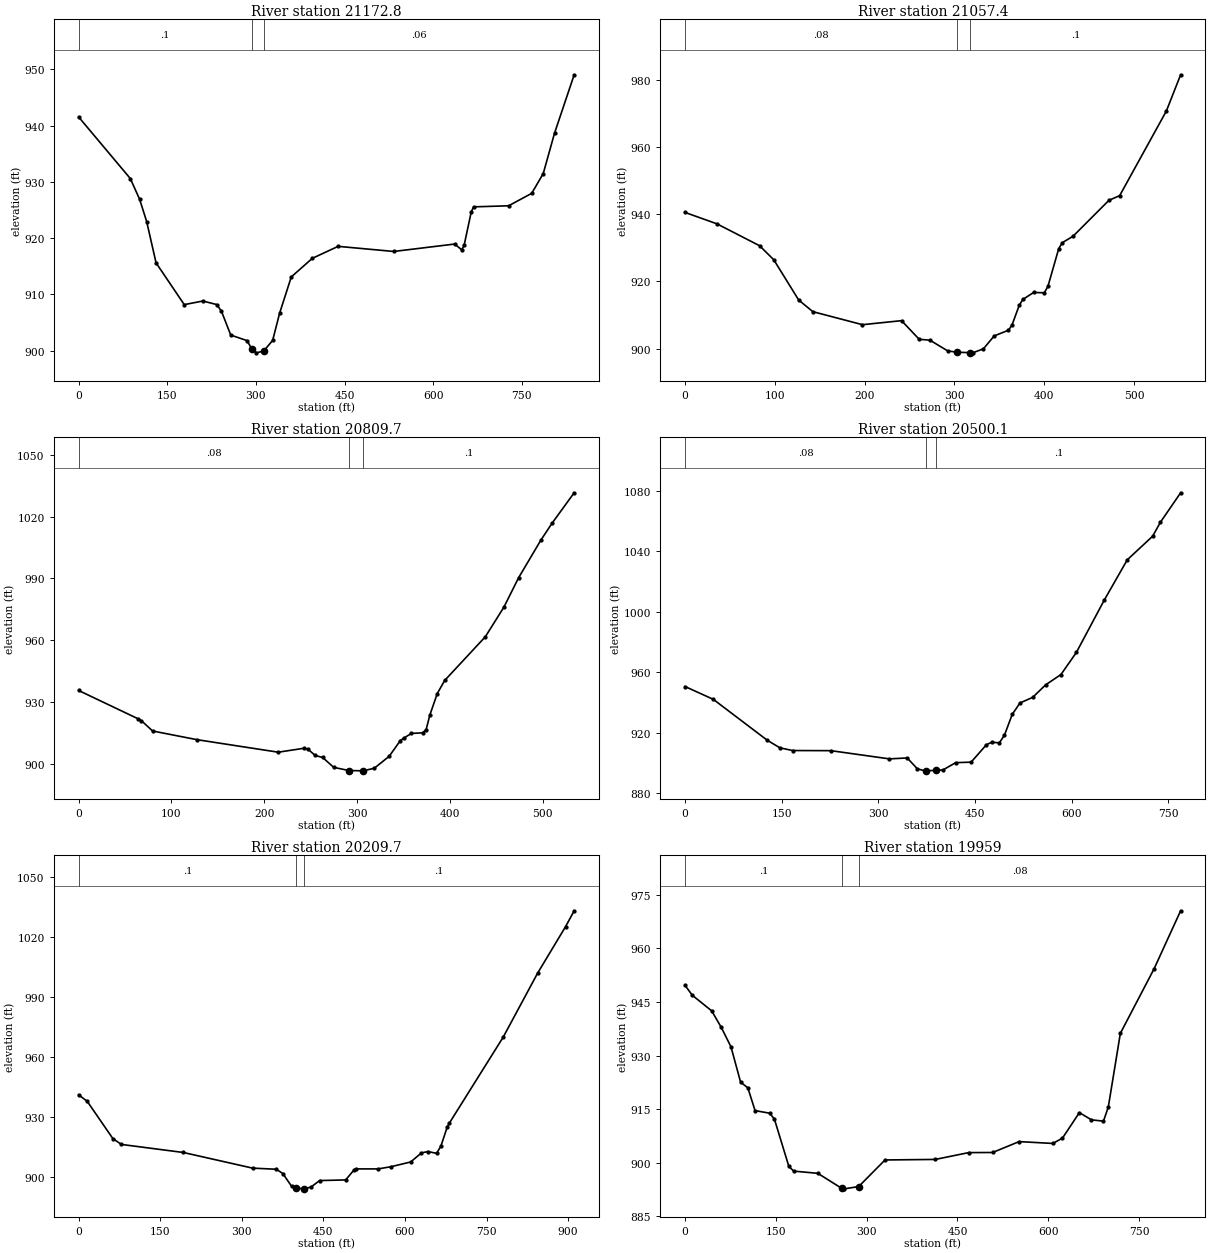
Type RM Length L Ch R = 1 ,21172.8 ,104.9,115.4,125.3
XS GIS Cut Line= 6
     1745852.563      340406.595     1746007.077      340488.192
     1746210.582      340510.555     1746303.952      340285.067
      1746371.66      340260.761     1746505.858      340293.506
#Sta/Elev= 30
       0  941.53    87.4  930.59   103.2   926.9   115.2  922.91     131   915.6
   178.7  908.17   210.2  908.81   233.8  908.18   241.7  906.98   257.4  902.76
     285  901.77   292.8  900.33   300.7   899.6   313.2  899.93   328.3  901.81
   340.1  906.65   359.8  913.09   395.4   916.4   439.1  918.53   533.2  917.62
   636.3  918.94   648.3   917.9   652.3  918.73   664.3  924.64   668.3  925.55
   727.6  925.74   766.7  927.96   786.2  931.48   805.3  938.66   838.5  949.03
#Mann= 3 , 0 , 0
       0      .1       0   292.8    .045       0   313.2     .06       0
Bank Sta=292.8,313.2
XS Rating Curve= 0 ,0
Exp/Cntr=0.3,0.1

Type RM Length L Ch R = 1 ,21057.4 ,229.8,247.7,266.5
XS GIS Cut Line= 3
     1745842.146      340439.581     1746095.618      340607.984
     1746307.424      340736.456
#Sta/Elev= 30
       0  940.51    35.6  937.11      83  930.61    98.8  926.43   126.5  914.48
   142.3  911.01   197.6  907.14   241.1  908.34   260.8  902.79   272.7  902.54
   292.5  899.35   302.6  898.96   317.6  898.82   320.3  898.77   332.3  899.96
   344.3   903.8   360.2  905.49   364.2  907.07   372.2  912.89   376.2  914.64
   388.2  916.71   400.2  916.63   404.2  918.56   416.2  929.75   420.2  931.52
   432.2  933.45   472.1  944.11   484.1  945.51   536.1  970.67     552  981.44
#Mann= 3 , 0 , 0
       0     .08       0   302.6    .045       0   317.6      .1       0
Bank Sta=302.6,317.6
XS Rating Curve= 0 ,0
Exp/Cntr=0.3,0.1

Type RM Length L Ch R = 1 ,20809.7 ,308,309.6,311.3
XS GIS Cut Line= 3
     1745856.035      340472.567     1745917.972      340764.794
      1745965.41      340995.136
#Sta/Elev= 30
       0  935.65    63.7  922.01    67.7  920.98    79.7  916.01   127.4  911.81
   215.1  905.73     243  907.65   246.9  907.25   254.9  904.14   262.9  903.18
   274.8  898.38   291.2  896.84   306.2   896.7   306.7  896.69   318.6  897.97
   334.6  903.75   346.6  911.34   350.5  912.61   358.5  914.83   370.5  915.12
   374.4  916.66   378.4  923.74   386.4  934.16   394.4  940.52   438.2  961.72
   458.2  976.08   474.1  990.38     498 1008.54     510 1016.71   533.9 1031.52
#Mann= 3 , 0 , 0
       0     .08       0   291.2    .045       0   306.2      .1       0
Bank Sta=291.2,306.2
XS Rating Curve= 0 ,0
Exp/Cntr=0.3,0.1

Type RM Length L Ch R = 1 ,20500.1 ,293,290.4,289.1
XS GIS Cut Line= 5
     1745612.979      340406.595     1745581.094      340542.414
     1745612.979      340785.067     1745641.944      341026.431
      1745715.41      341147.914
#Sta/Elev= 30
       0  950.66    43.8   942.2   127.6  915.16   147.4  910.12   167.1  908.38
   226.4  908.29   317.1  902.87   344.8  903.47   360.6   896.3   372.4  894.96
   374.6  894.96   389.6  895.33   400.2  895.53   420.1  900.36     444  900.71
   467.9  912.26   475.9  913.81   487.9   913.5   495.8  918.56   507.8  932.21
   519.8  939.79   539.7  943.54   559.6  951.75   583.5   958.6   607.4  973.19
     651    1008   686.5 1034.44   725.9 1050.04   737.8 1059.18   769.3 1078.71
#Mann= 3 , 0 , 0
       0     .08       0   374.6    .045       0   389.6      .1       0
Bank Sta=374.6,389.6
XS Rating Curve= 0 ,0
Exp/Cntr=0.3,0.1

Type RM Length L Ch R = 1 ,20209.7 ,250.2,250.7,248.9
XS GIS Cut Line= 5
     1745378.604      340449.997     1745275.418      340617.307
     1745328.066      340821.319     1745373.396      341068.053
      1745573.69      341222.525
#Sta/Elev= 30
       0  940.92    15.7  937.72    62.9  919.08    78.6  916.15   192.6  912.12
   319.8  904.31   363.5  903.75   375.5  901.58   391.4  895.29   399.8  894.38
   414.8  893.97   415.2  893.96   427.2  894.85   443.1   898.1   490.9  898.41
   506.8  903.56   510.8  903.92   550.6  903.92   574.5  905.02   610.4  907.38
   630.3   911.9   642.2   912.6   658.1  911.69     666  915.26   677.9     925
   681.8  926.88   780.6  969.75   843.9 1001.73   895.3 1024.98   911.1 1032.89
#Mann= 3 , 0 , 0
       0      .1       0   399.8    .045       0   414.8      .1       0
Bank Sta=399.8,414.8
XS Rating Curve= 0 ,0
Exp/Cntr=0.3,0.1

Type RM Length L Ch R = 1 ,19959   ,399,364.8,334.8
XS GIS Cut Line= 4
     1745029.646      340644.442     1745088.674      340892.706
     1745159.854      341160.067     1745444.577      341194.789
#Sta/Elev= 30
       0  949.64      12  946.88    43.9  942.54    59.8   937.9    75.8  932.47
    91.7  922.59   103.7  920.98   115.6  914.62   139.6   913.9   147.5  912.27
   171.4  899.02   179.4  897.69   219.3  897.07   259.1  892.83   263.1  892.73
   286.8  893.37   330.3  900.81   413.3  900.96   468.6  902.87   508.1   902.9
   551.8  905.95   607.6  905.43   623.5  906.93   651.4  914.06   671.3  912.04
   691.2  911.67   699.2  915.63   719.1  936.24   774.9  954.33   818.7  970.54
#Mann= 3 , 0 , 0
       0      .1       0   259.1    .045       0   286.8     .08       0
Bank Sta=259.1,286.8
XS Rating Curve= 0 ,0
Exp/Cntr=0.3,0.1

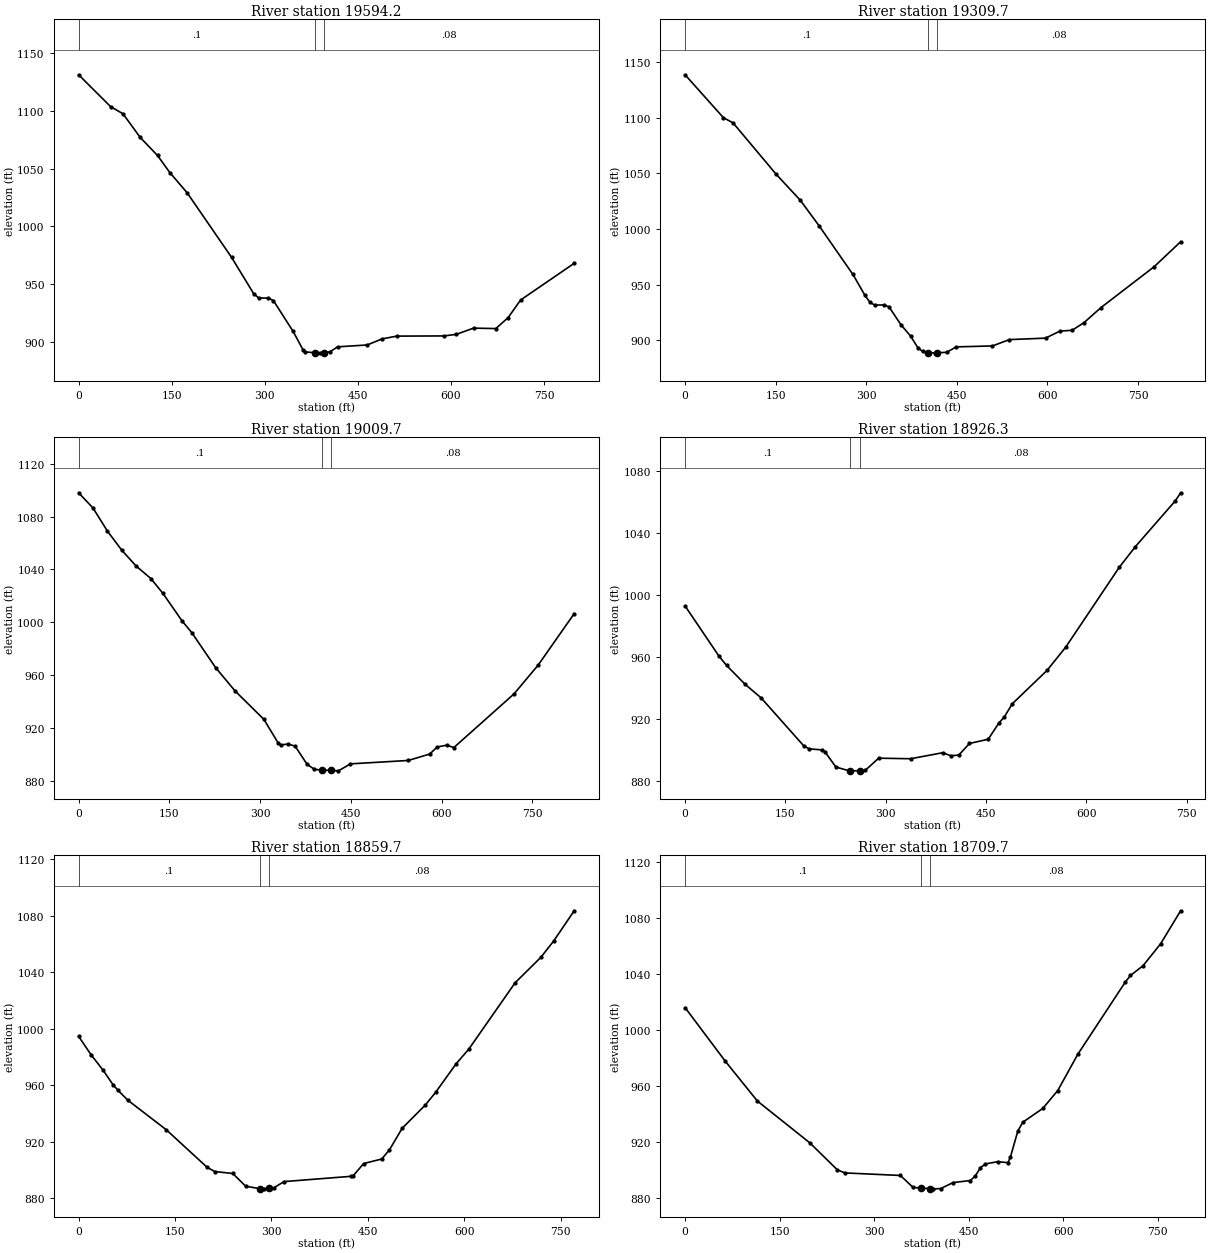
Type RM Length L Ch R = 1 ,19594.2 ,287.1,284.5,280.1
XS GIS Cut Line= 4
     1744639.021      341246.872     1745029.646      341201.734
     1745356.035      341217.359      1745434.16      341224.303
#Sta/Elev= 30
       0 1131.27    51.6 1103.66    71.5  1097.5    99.3 1076.98   127.1  1061.4
     147 1046.57   174.8 1029.14   246.3  973.28     282  941.77     290  938.09
   305.8  937.87   313.8  935.82   345.6  909.05   361.4  893.27   365.4  891.27
   380.3  890.68   389.2  890.53   395.3  890.66   405.2  891.43   417.1  895.71
     465  897.36   488.9  902.61   512.8  905.01   588.5  905.17   608.4  906.52
   636.3  911.92   672.2  911.54   692.1  921.08     712  936.23   798.4  968.03
#Mann= 3 , 0 , 0
       0      .1       0   380.3    .045       0   395.3     .08       0
Bank Sta=380.3,395.3
XS Rating Curve= 0 ,0
Exp/Cntr=0.3,0.1

Type RM Length L Ch R = 1 ,19309.7 ,301.4,300,296.8
XS GIS Cut Line= 3
     1744693.816      341574.364     1745091.631      341478.793
     1745497.507      341410.537
#Sta/Elev= 30
       0 1138.65    63.6 1099.98    79.4 1095.44   150.9 1049.15   190.7 1025.92
   222.4 1002.53     278   959.1   297.9  940.32   305.9  934.18   313.8  931.63
   329.7   931.7   337.6  930.08   357.5  913.92   373.4  903.78   385.3  893.44
   393.2  889.92   401.6   888.8   413.1  888.66   416.6  888.66   433.1  889.16
   449.1  894.02     509  894.86     537  900.55   596.9  901.88   620.9  908.22
   640.9  908.91   660.9  915.93   688.8  929.36   776.8  966.08   820.7  988.54
#Mann= 3 , 0 , 0
       0      .1       0   401.6    .045       0   416.6     .08       0
Bank Sta=401.6,416.6
XS Rating Curve= 0 ,0
Exp/Cntr=0.3,0.1

Type RM Length L Ch R = 1 ,19009.7 ,83.5,83.4,83.3
XS GIS Cut Line= 3
     1744784.204      341888.133     1745175.321      341766.819
     1745566.439      341645.506
#Sta/Elev= 30
       0 1097.97    23.8 1086.44    47.7  1068.9    71.6 1054.37    95.4 1042.41
   119.3 1033.13   139.2 1021.97     171    1001   186.9  992.27   226.6   965.6
   258.4  948.16   306.1  926.62     330  908.59     334  907.22   345.9  907.95
   357.8  906.34   377.7  892.53   389.6  888.85     402  888.17     417  888.03
   429.4  887.66   449.3  892.94   544.7   895.5   580.5   900.4   592.4  905.68
   608.3  907.06   620.2  905.28   719.6  945.86   759.4  967.59     819 1006.54
#Mann= 3 , 0 , 0
       0      .1       0     402    .045       0     417     .08       0
Bank Sta=402,417
XS Rating Curve= 0 ,0
Exp/Cntr=0.3,0.1

Type RM Length L Ch R = 1 ,18926.3 ,66.5,66.5,66.5
XS GIS Cut Line= 3
     1744954.993      341904.859     1745032.358      341899.275
     1745665.063      341699.997
#Sta/Elev= 30
       0  993.06    50.4  960.91      62  954.76    89.6  942.67   113.5  933.93
   177.5  902.92   185.5  901.04   205.4  900.32   209.4  898.95   225.4  889.32
   245.4  886.86     247  886.87     262  886.93   269.4   887.2   289.4  895.01
   337.3  894.66   385.3  898.54   397.2  896.57   409.2     897   425.2   904.5
   453.2  907.22   469.2  917.68   477.2  921.56   489.2  930.07   541.1  951.54
   569.1  966.56     649  1017.9     673 1031.19   732.9  1060.8   740.9    1066
#Mann= 3 , 0 , 0
       0      .1       0     247    .045       0     262     .08       0
Bank Sta=247,262
XS Rating Curve= 0 ,0
Exp/Cntr=0.3,0.1

Type RM Length L Ch R = 1 ,18859.7 ,147.1,150.1,152.5
XS GIS Cut Line= 3
     1744942.841      341967.359      1745030.94      341969.425
     1745682.424      341764.234
#Sta/Elev= 30
       0  994.51    19.2  981.57    38.3  970.41    53.6   960.2    61.3  956.33
    76.6  949.29   136.1  928.51     200  901.78     212   898.8   239.9  897.44
   259.9  888.42     282  886.68   287.8  886.56     297  886.99   303.8   887.3
   319.8   891.7   423.6  895.41   427.6     896   443.6  904.48   471.6  907.66
   483.6  914.06   503.5  929.44   539.5  945.88   555.5  954.83   587.4  975.07
   607.4  985.58   679.3 1032.46   719.2 1050.39   739.2 1061.96   771.2 1083.42
#Mann= 3 , 0 , 0
       0      .1       0     282    .045       0     297     .08       0
Bank Sta=282,297
XS Rating Curve= 0 ,0
Exp/Cntr=0.3,0.1

Type RM Length L Ch R = 1 ,18709.7 ,289,300,311.5
XS GIS Cut Line= 5
     1744887.285      342074.997     1745072.821      342085.834
     1745265.922      342052.399     1745463.801      342013.137
     1745666.799       342015.97
#Sta/Elev= 30
       0 1015.78    63.3  977.78   114.7  949.02   197.8  919.19   241.8  899.76
   253.8  897.62   341.8   895.8   361.8  887.25   374.3   886.8   389.3  886.35
   393.7  886.24   405.6   886.4   425.3  890.71     453  892.19   460.9  895.65
   468.8  901.36   476.8  904.04   496.5   905.7   512.4  904.92   516.3   908.8
   528.2  927.63   536.1  933.88   567.7   943.7   591.5  956.48   623.4  982.46
     699 1034.23     707 1038.78   726.9 1045.75   754.7 1061.35   786.6 1085.03
#Mann= 3 , 0 , 0
       0      .1       0   374.3    .045       0   389.3     .08       0
Bank Sta=374.3,389.3
XS Rating Curve= 0 ,0
Exp/Cntr=0.3,0.1

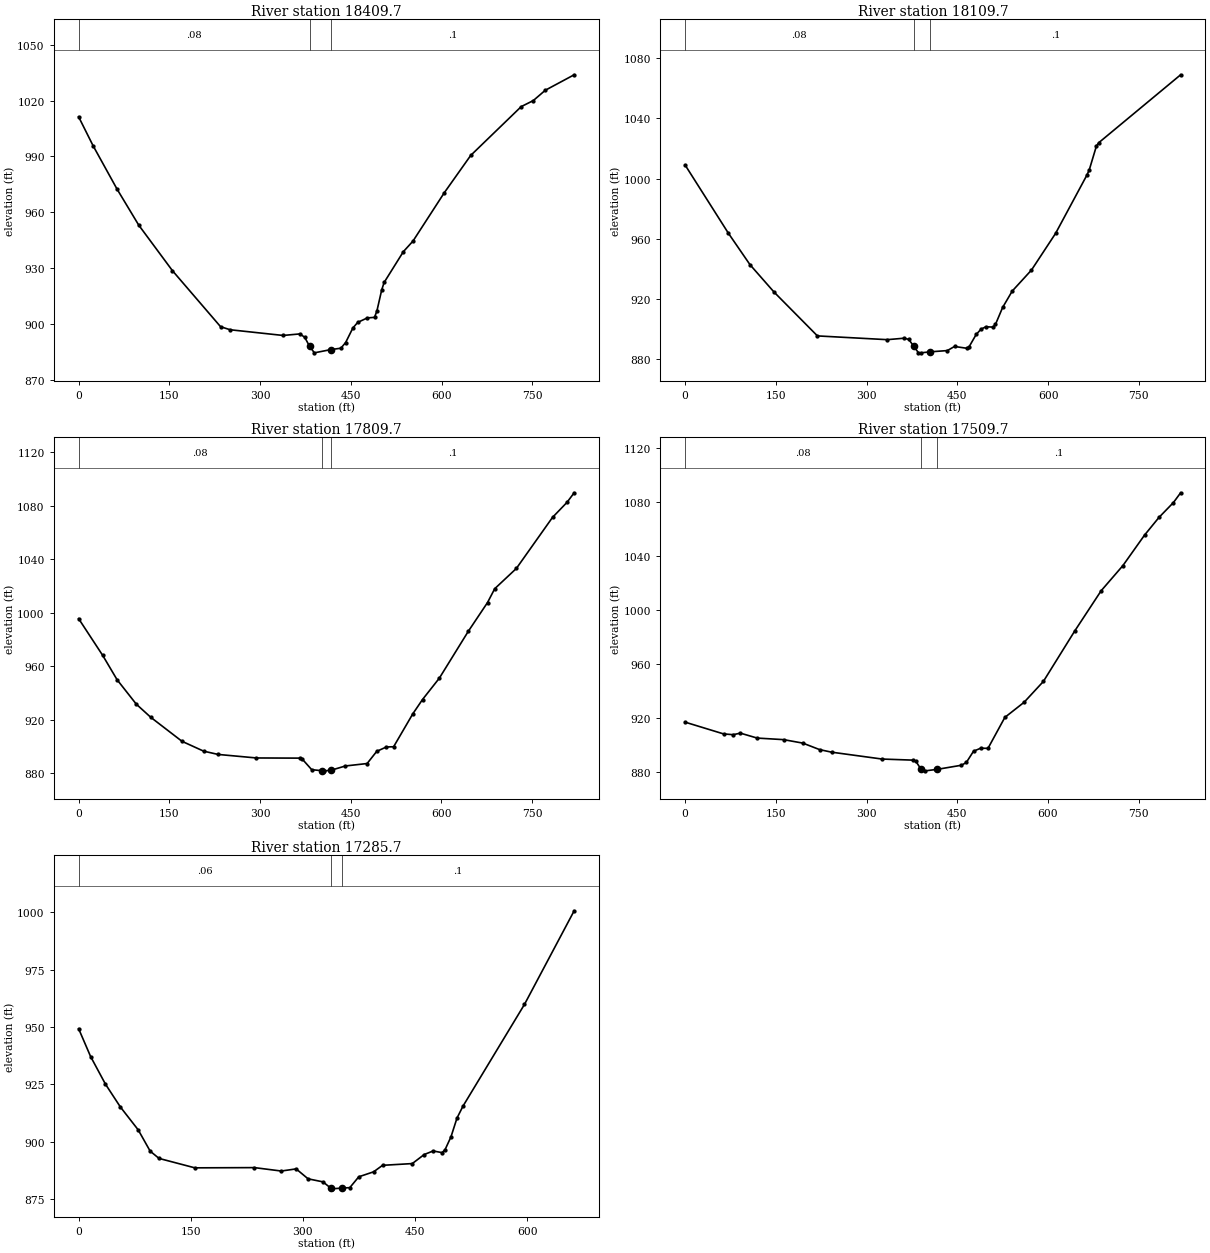
Type RM Length L Ch R = 1 ,18409.7 ,300.8,300,299.2
XS GIS Cut Line= 3
     1744851.409      342219.172      1745240.97      342345.396
     1745630.531      342471.621
#Sta/Elev= 30
       0 1011.25    23.8   995.8    63.6  972.44    99.4  953.16     155  928.79
   234.6  898.74   250.5   897.1   337.9  894.05   365.8  894.88   373.7  893.04
   381.7  888.23   389.6  884.73     417  886.48   433.4  887.21   441.3  890.25
   453.2  898.02   461.2  901.04   477.1  903.45     489  903.75     493  907.21
   500.9  918.47   504.9  922.46   536.7  938.97   552.6  944.64   604.3  970.54
     648  990.55   731.5 1016.73   751.4 1019.95   771.3  1025.5     819 1033.79
#Mann= 3 , 0 , 0
       0     .08       0   381.7    .045       0     417      .1       0
Bank Sta=381.7,417
XS Rating Curve= 0 ,0
Exp/Cntr=0.3,0.1

Type RM Length L Ch R = 1 ,18109.7 ,302.5,300,298.6
XS GIS Cut Line= 3
     1744755.246      342517.875     1745148.841      342630.894
     1745542.436      342743.912
#Sta/Elev= 30
       0 1009.01    71.6  963.52   107.3  942.57   147.1  924.31   218.7  895.14
     334  892.64   361.8   893.6   369.7  892.83   377.7  888.31   385.6  883.97
   389.6  883.86   405.5  884.55   433.4  885.36   445.3  888.11   465.2  886.92
   469.1  887.71   481.1  896.11     489  899.59     497  901.23   508.9  901.01
   512.9  902.75   524.8   914.1   540.7  925.03   572.5  939.03   612.3  963.43
     664 1002.21   667.9 1005.65   679.8 1021.65   683.8 1023.91     819 1069.12
#Mann= 3 , 0 , 0
       0     .08       0   377.7    .045       0   405.5      .1       0
Bank Sta=377.7,405.5
XS Rating Curve= 0 ,0
Exp/Cntr=0.3,0.1

Type RM Length L Ch R = 1 ,17809.7 ,300.1,300,298.6
XS GIS Cut Line= 3
      1744653.09      342847.311     1745056.719      342915.762
     1745457.172      343004.229
#Sta/Elev= 30
       0  995.61    39.8  968.13    63.6  949.92    95.4  931.64   119.2  921.85
   170.9  903.87   206.7   896.5   230.5  894.05   294.1   891.4   365.7  891.28
   369.6  890.67   385.5  882.62   401.9  881.91   405.4  881.77   416.9  882.15
   441.2  885.41   477.1  887.24     493  896.35   508.9  899.62   520.9  899.79
   552.7  924.45   568.7  935.13   596.5  951.09   644.3  986.07   676.2 1007.66
   688.1    1018   723.9 1033.18   783.7 1071.38   807.6  1082.6   819.5 1089.78
#Mann= 3 , 0 , 0
       0     .08       0   401.9    .045       0   416.9      .1       0
Bank Sta=401.9,416.9
XS Rating Curve= 0 ,0
Exp/Cntr=0.3,0.1

Type RM Length L Ch R = 1 ,17509.7 ,224.5,223.9,224.2
XS GIS Cut Line= 3
     1744599.387      343144.237     1745003.075      343210.886
     1745408.201      343274.377
#Sta/Elev= 30
       0  916.96    63.6  908.25    79.4  907.67    91.4  908.82   119.2  905.16
   162.9     904   194.6  901.43   222.4  896.61   242.3  894.71   325.7  889.62
   377.4  888.81   381.4  888.01   389.3  882.59   397.2  880.89   416.7  881.99
   456.9  885.04   464.9  887.08   476.8  895.41   488.8  897.69   500.7  897.53
   528.6  920.48   560.4  931.67   592.3  947.13     644  984.41   687.8  1014.3
   723.7 1032.91   759.5  1055.5   783.4 1068.63   807.3 1079.65   819.2 1086.88
#Mann= 3 , 0 , 0
       0     .08       0   389.3    .045       0   416.7      .1       0
Bank Sta=389.3,416.7
XS Rating Curve= 0 ,0
Exp/Cntr=0.3,0.1

Type RM Length L Ch R = 1 ,17285.7 ,379.2,376.1,371
XS GIS Cut Line= 4
     1744609.507      343377.081     1744956.729      343427.428
      1745125.31      343457.686     1745265.757      343446.525
#Sta/Elev= 30
       0  949.24      16  937.12    35.9  925.05    55.8  915.12    79.7  905.11
    95.7  895.83   107.6  892.65   155.5  888.54   235.2  888.64   271.1  887.15
     291  888.08     307  883.75   326.9  882.42   337.7   879.6   338.9  879.38
   352.7  879.72   362.8   879.9   374.8  884.63   394.7  886.81   406.6  889.64
   446.4   890.4   462.4  894.36   474.3   895.9   486.3  895.18   490.3   896.5
   498.2  902.09   506.2  910.24   514.2  915.44   596.5  959.85     663  1000.7
#Mann= 3 , 0 , 0
       0     .06       0   337.7    .045       0   352.7      .1       0
Bank Sta=337.7,352.7
XS Rating Curve= 0 ,0
Exp/Cntr=0.3,0.1