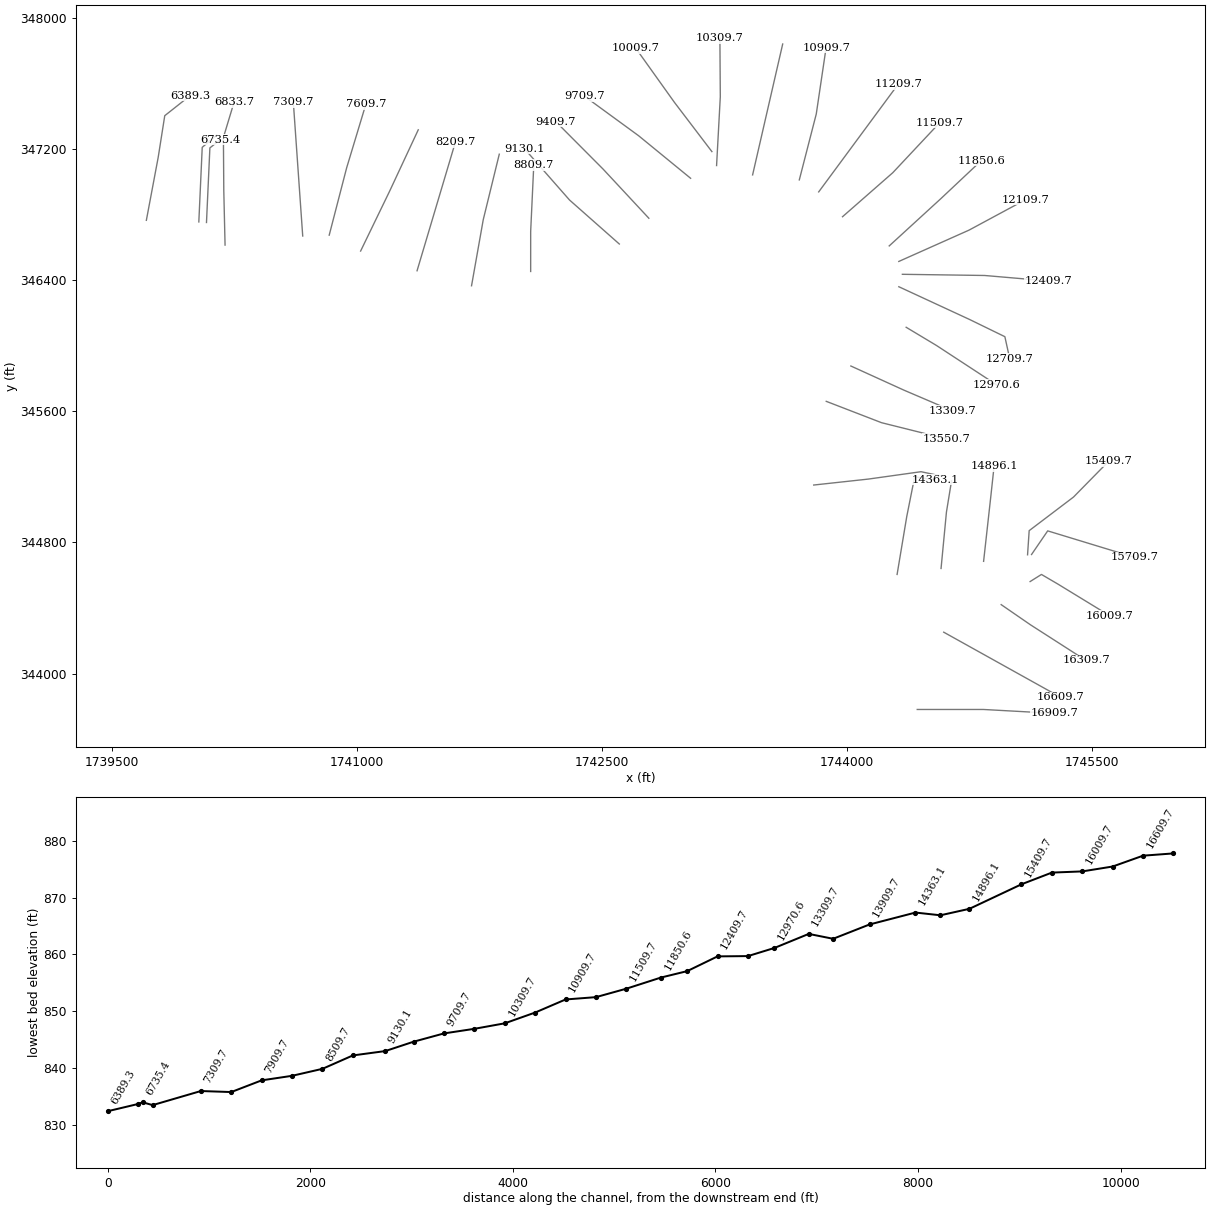
HEC-RAS study SPLAURFK.prj: SPLAURFK

--- SPLAURFK.g01 (geometry) --- (continued)

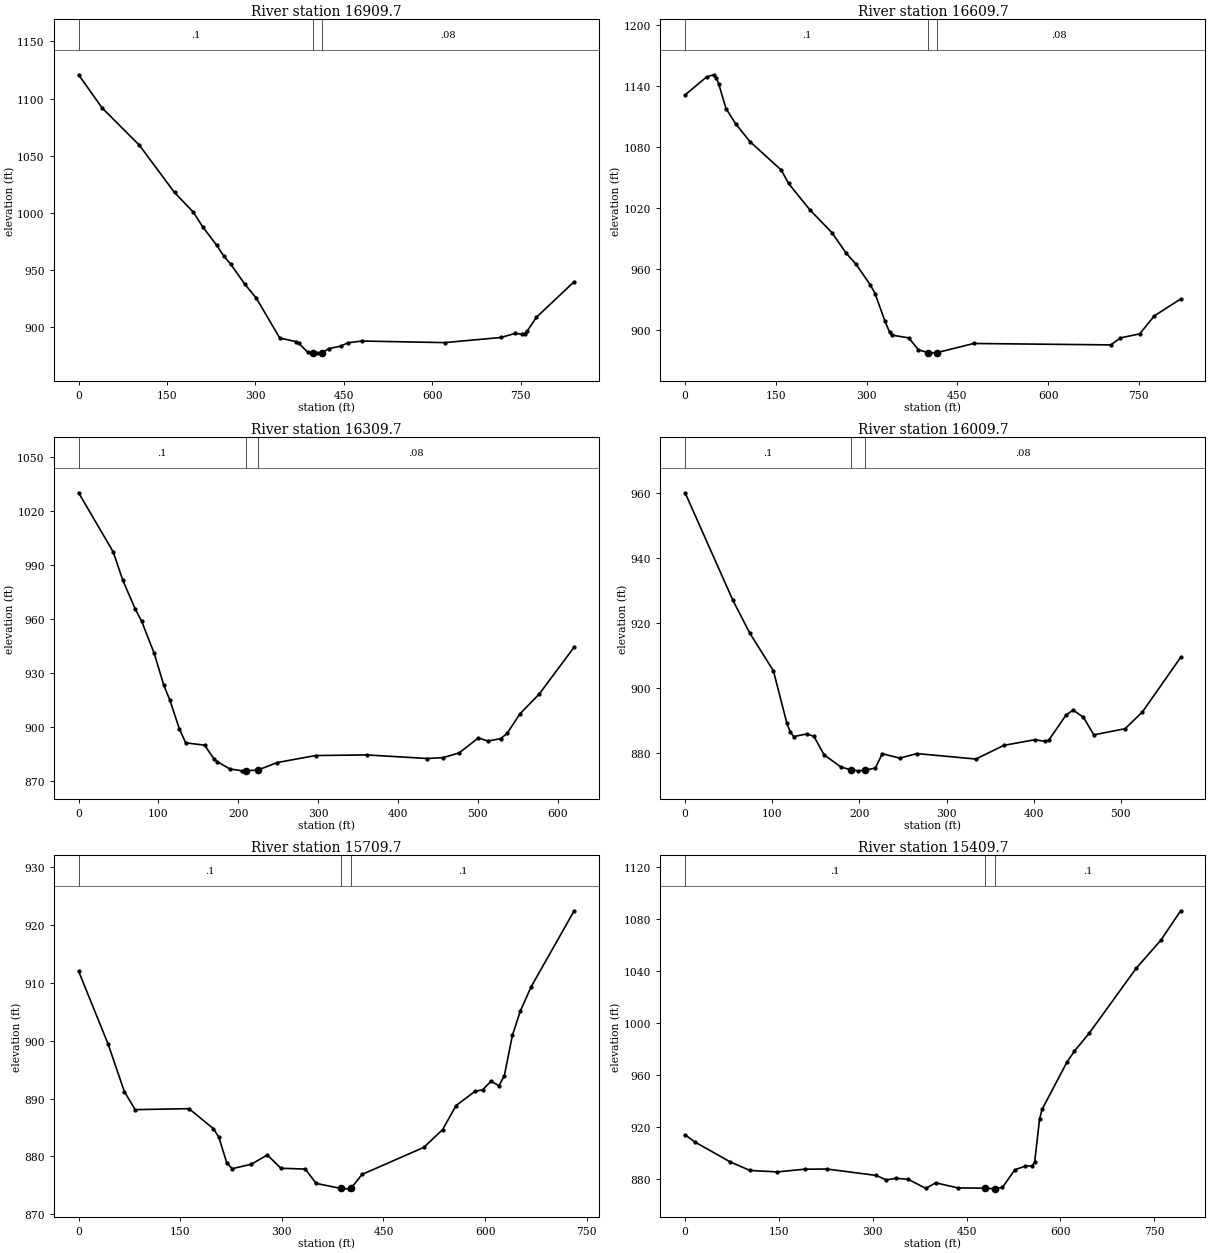
Type RM Length L Ch R = 1 ,16909.7 ,311.5,300,289.6
XS GIS Cut Line= 3
     1744428.995      343781.287     1744833.831      343781.287
     1745269.107      343757.457
#Sta/Elev= 30
       0 1120.79    39.7  1091.9   103.2 1059.15   162.7 1017.91   194.5  1000.8
   210.4     988   234.2   971.8   246.1  962.49     258  955.27   281.8  937.93
   301.6  925.46   341.3   890.7   369.1  887.59   373.1  886.43     389  878.14
   397.3  877.88   404.8  877.78   412.3  877.82   424.8  881.48   444.8  883.67
   456.8  886.55   480.8   888.1   620.8  886.71   716.8  891.21   740.8   894.8
   752.8  894.01   756.8  894.61   760.8  896.64   776.8  908.89   840.8  939.99
#Mann= 3 , 0 , 0
       0      .1       0   397.3    .045       0   412.3     .08       0
Bank Sta=397.3,412.3
XS Rating Curve= 0 ,0
Exp/Cntr=0.3,0.1

Type RM Length L Ch R = 1 ,16609.7 ,302.1,300,298.6
XS GIS Cut Line= 3
     1744591.137      344252.472     1744949.258      344053.877
     1745307.379      343855.283
#Sta/Elev= 30
       0 1130.83    35.8 1148.65    47.7 1150.61    51.7 1147.64    55.7 1141.29
    67.6 1117.45    83.5 1102.49   107.3  1084.9     159 1056.95     171 1043.78
   206.7  1017.6   242.5  995.57   266.4  975.21   282.3   964.6   306.1  944.18
   314.1  935.46     330  908.95   337.9  897.86   341.9  894.78   369.7  892.08
   385.6  880.34     402  877.49   405.5  877.38     417  877.67   477.1  886.58
   703.7  885.18   719.6  892.07   751.4  896.04   775.3  913.63     819   930.3
#Mann= 3 , 0 , 0
       0      .1       0     402    .045       0     417     .08       0
Bank Sta=402,417
XS Rating Curve= 0 ,0
Exp/Cntr=0.3,0.1

Type RM Length L Ch R = 1 ,16309.7 ,298.3,300,300.5
XS GIS Cut Line= 3
     1744942.841      344420.484     1745121.706      344297.754
     1745461.938      344080.206
#Sta/Elev= 30
       0 1030.19    43.4  997.23    55.2  981.65      71  965.37    78.9  958.75
    94.7   940.8   106.5  923.36   114.4  914.68   126.2  898.83   134.1  891.05
   157.8  889.75   169.6   882.1   173.5  880.65   189.3  876.54   205.1  875.47
   209.4  875.54   224.4  875.88   248.9   880.1   296.9  883.98   360.9  884.33
   436.8  882.33   456.8  882.85   476.8  885.46   500.8  893.82   512.8  892.01
   528.8  893.42   536.8   896.3   552.8  907.16   576.8  918.08   620.8  944.32
#Mann= 3 , 0 , 0
       0      .1       0   209.4    .045       0   224.4     .08       0
Bank Sta=209.4,224.4
XS Rating Curve= 0 ,0
Exp/Cntr=0.3,0.1

Type RM Length L Ch R = 1 ,16009.7 ,294.7,300,305.7
XS GIS Cut Line= 4
     1745119.924      344561.109     1745189.368      344604.511
     1745289.985      344545.809     1745606.218      344353.372
#Sta/Elev= 30
       0  960.18    54.6  927.23    74.1  917.05   101.3  905.41   116.8  889.23
   120.7  886.61   124.6  885.15   140.1  885.98   147.9  885.18   159.6   879.5
     179  875.76   190.9  874.88   198.4  874.61   205.9  874.79   218.3  875.47
   226.2  879.89   246.2  878.52     266  879.92   333.7  878.24   365.6  882.44
   401.4  884.19   413.3  883.67   417.3  884.07   437.2  891.79   445.2  893.32
   457.1  891.08     469  885.68   504.9  887.58   524.8  892.75   568.6  909.52
#Mann= 3 , 0 , 0
       0      .1       0   190.9    .045       0   205.9     .08       0
Bank Sta=190.9,205.9
XS Rating Curve= 0 ,0
Exp/Cntr=0.3,0.1

Type RM Length L Ch R = 1 ,15709.7 ,278.9,300,324.7
XS GIS Cut Line= 4
     1745128.604      344726.039     1745227.563      344870.136
     1745437.778      344806.364     1745760.305      344708.455
#Sta/Elev= 30
       0  912.04    43.7  899.38    67.5  891.23    83.4   888.1   162.9  888.27
   198.8  884.82   206.8  883.38   218.7   878.9   226.7  877.89   254.7  878.65
   278.6  880.26   298.6  877.96   334.6  877.82   350.6  875.34     387  874.48
   398.4   874.4     402  874.47   418.3  876.89   509.5  881.57   537.2  884.63
   557.1   888.8   584.8  891.24   596.7  891.56   608.6  893.02   620.5  892.24
   628.4  893.95   640.3  900.96   652.2  905.21   668.1  909.38   731.5   922.5
#Mann= 3 , 0 , 0
       0      .1       0     387    .045       0     402      .1       0
Bank Sta=387,402
XS Rating Curve= 0 ,0
Exp/Cntr=0.3,0.1

Type RM Length L Ch R = 1 ,15409.7 ,494.9,513.6,528.7
XS GIS Cut Line= 4
     1745104.299      344724.303     1745114.165      344871.474
     1745385.577      345076.369     1745599.496      345293.298
#Sta/Elev= 30
       0  913.93      16  908.32    71.8  893.17   103.6   886.5   147.5  885.37
     191  887.46   226.6   887.6   305.7  882.65   321.5  879.23   337.3  880.48
   357.1  879.64   384.8  872.65   400.6  876.97   436.2  873.05   480.1  872.85
   495.1  872.35   495.5  872.34   507.4  873.45   527.1  887.06     543  889.68
   554.8  890.12   558.8  892.88   566.7  926.14   570.7  933.58   610.2  969.67
   622.1  978.22   645.8  992.02     721 1042.09   760.6 1063.84   792.2 1086.46
#Mann= 3 , 0 , 0
       0      .1       0   480.1    .045       0   495.1      .1       0
Bank Sta=480.1,495.1
XS Rating Curve= 0 ,0
Exp/Cntr=0.3,0.1

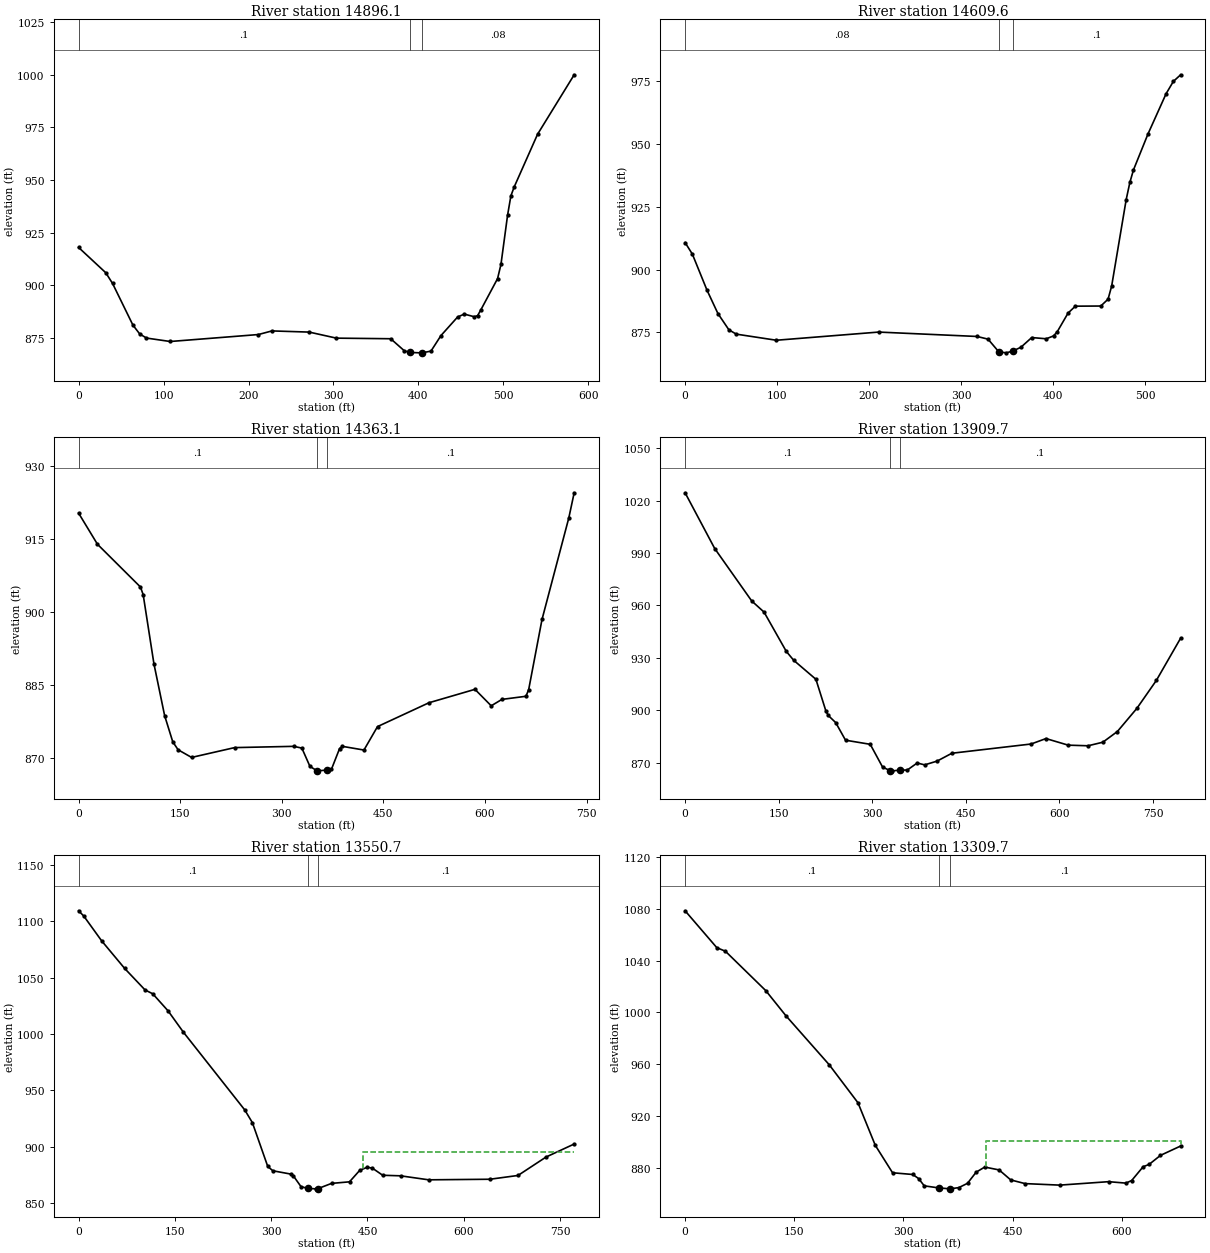
Type RM Length L Ch R = 1 ,14896.1 ,286.6,286.4,284.7
XS GIS Cut Line= 3
     1744835.202      344684.372     1744878.604      345073.261
     1744899.438      345264.234
#Sta/Elev= 30
       0     918    31.9  906.04    39.9  900.97    63.9  881.19    71.9  876.98
    79.9  875.03   107.8   873.4   211.6   876.7   227.6  878.42   271.5  877.86
   303.5  874.99   367.4  874.71   383.3  869.04   389.6   868.2   403.1  868.02
   404.6  868.06   414.8  868.83   426.6  876.23   446.2  885.03     454   886.4
   465.8  885.14   469.7  885.66   473.6  888.46   493.2  903.22   497.2  909.95
     505  933.33   508.9   942.5   512.8  946.73   540.3  971.71   583.4  999.93
#Mann= 3 , 0 , 0
       0      .1       0   389.6    .045       0   404.6     .08       0
Bank Sta=389.6,404.6
XS Rating Curve= 0 ,0
Exp/Cntr=0.3,0.1

Type RM Length L Ch R = 1 ,14609.6 ,247.6,246.5,246.3
XS GIS Cut Line= 3
     1744574.785       344640.97     1744607.771       344984.72
     1744639.021      345175.692
#Sta/Elev= 30
       0  910.74     7.9  906.14    23.8  891.82    35.7   882.5    47.6  876.05
    55.6  874.32    99.2  871.89   210.4  875.14   317.5  873.39   329.4  872.32
   341.1  867.28   349.3  866.88   356.1  867.58   365.1  869.09   376.9  872.96
   392.7  872.47   400.6  873.61   404.6  875.25   416.4  882.69   424.3  885.44
     452   885.5   459.9  888.23   463.8  893.45   479.6  927.84   483.6  934.67
   487.5  939.62   503.3  953.93     523  969.95   530.9  974.84   538.8  977.47
#Mann= 3 , 0 , 0
       0     .08       0   341.1    .045       0   356.1      .1       0
Bank Sta=341.1,356.1
XS Rating Curve= 0 ,0
Exp/Cntr=0.3,0.1

Type RM Length L Ch R = 1 ,14363.1 ,483.8,453.5,424.5
XS GIS Cut Line= 4
     1744305.688      344604.511     1744364.716      344956.942
     1744413.327      345199.997     1744538.327        345180.9
#Sta/Elev= 30
       0  920.37    27.8  913.98    91.3  905.18    95.3  903.61   111.2  889.37
     127  878.71     139  873.33   146.9  871.69   166.8  870.12   230.3  872.14
   317.6   872.4   329.6  872.04   341.5  868.29   351.6   867.4   353.4  867.36
   366.6  867.52   373.3  867.68   385.3  871.94   389.3   872.4   421.3  871.64
   441.3  876.46   517.3  881.37   585.2  884.13   609.2  880.74     625  882.06
   660.5   882.7   664.5  884.06   684.2   898.5   723.8  919.41   731.7  924.57
#Mann= 3 , 0 , 0
       0      .1       0   351.6    .045       0   366.6      .1       0
Bank Sta=351.6,366.6
XS Rating Curve= 0 ,0
Exp/Cntr=0.3,0.1

Type RM Length L Ch R = 1 ,13909.7 ,370.1,359,350.2
XS GIS Cut Line= 4
     1743795.271       345149.65     1744129.686      345185.947
     1744452.051      345230.919     1744581.729       345203.47
#Sta/Elev= 30
       0 1024.56    47.5  992.61   106.8  962.58   126.6  956.19   162.2   933.7
   174.1  928.59   209.7  917.72   225.6  899.66   229.5  896.97   241.4  892.91
   257.2  882.81   296.8  880.46   316.6  867.41   328.9  865.33   332.4  865.26
   343.9  865.64   356.2  865.73   372.1  869.76     384  868.68   403.9  870.83
   427.7  875.34   554.7  880.63   578.5  883.75   614.2  879.97     646  879.62
   669.7  881.66     693  887.79   724.2  901.03   755.4  917.02   794.4  941.27
#Mann= 3 , 0 , 0
       0      .1       0   328.9    .045       0   343.9      .1       0
Bank Sta=328.9,343.9
XS Rating Curve= 0 ,0
Exp/Cntr=0.3,0.1

Type RM Length L Ch R = 1 ,13550.7 ,242.3,241,237.2
XS GIS Cut Line= 3
     1743872.033      345659.894     1744210.202      345529.859
     1744607.771        345430.9
#Sta/Elev= 30
       0 1109.38       8 1104.71    35.8 1082.76    71.7 1058.24   103.5 1039.14
   115.5 1035.74   139.4 1020.56   163.2  1001.7   258.8  932.73   270.7  921.43
   294.6  882.65   302.6  878.76   330.5  875.83   334.4  874.35   346.4  864.72
   357.2  863.07   370.3  862.74   372.2  862.79   394.1  867.58     422  868.96
   437.9  879.12   449.8  881.93   457.8  881.02   473.7  874.78   501.5  874.29
   545.3  870.74   640.8  871.25   684.5  874.61   728.2  890.96     772  902.49
#Mann= 3 , 0 , 0
       0      .1       0   357.2    .045       0   372.2      .1       0
#XS Ineff= 2 , 0
                          442.74             895
Permanent Ineff=
       F       F
Bank Sta=357.2,372.2
XS Rating Curve= 0 ,0
Exp/Cntr=0.3,0.1

Type RM Length L Ch R = 1 ,13309.7 ,341.5,339.1,335.2
XS GIS Cut Line= 3
     1744022.702      345875.345     1744347.347      345728.228
     1744645.966      345601.039
#Sta/Elev= 30
       0 1078.58    43.6 1050.05    55.4  1047.3   110.9 1016.83   138.6   997.4
     198  959.58   237.6  930.12   261.4  897.21   285.1  876.03   312.9  874.69
   320.8  871.58   328.7   865.9   348.9   864.3   363.9  863.61   364.3   863.6
   376.2  864.56   388.1  867.87     400   876.5   411.8  880.44   431.6  878.21
   447.5  870.49   467.2  867.65   514.8  866.47     582  869.14   605.8  868.02
   613.7  870.02   629.5  880.72   637.5  882.42   653.3  889.48     681  896.71
#Mann= 3 , 0 , 0
       0      .1       0   348.9    .045       0   363.9      .1       0
#XS Ineff= 2 , 0
                          413.51           900.6
Permanent Ineff=
       F       F
Bank Sta=348.9,363.9
XS Rating Curve= 0 ,0
Exp/Cntr=0.3,0.1

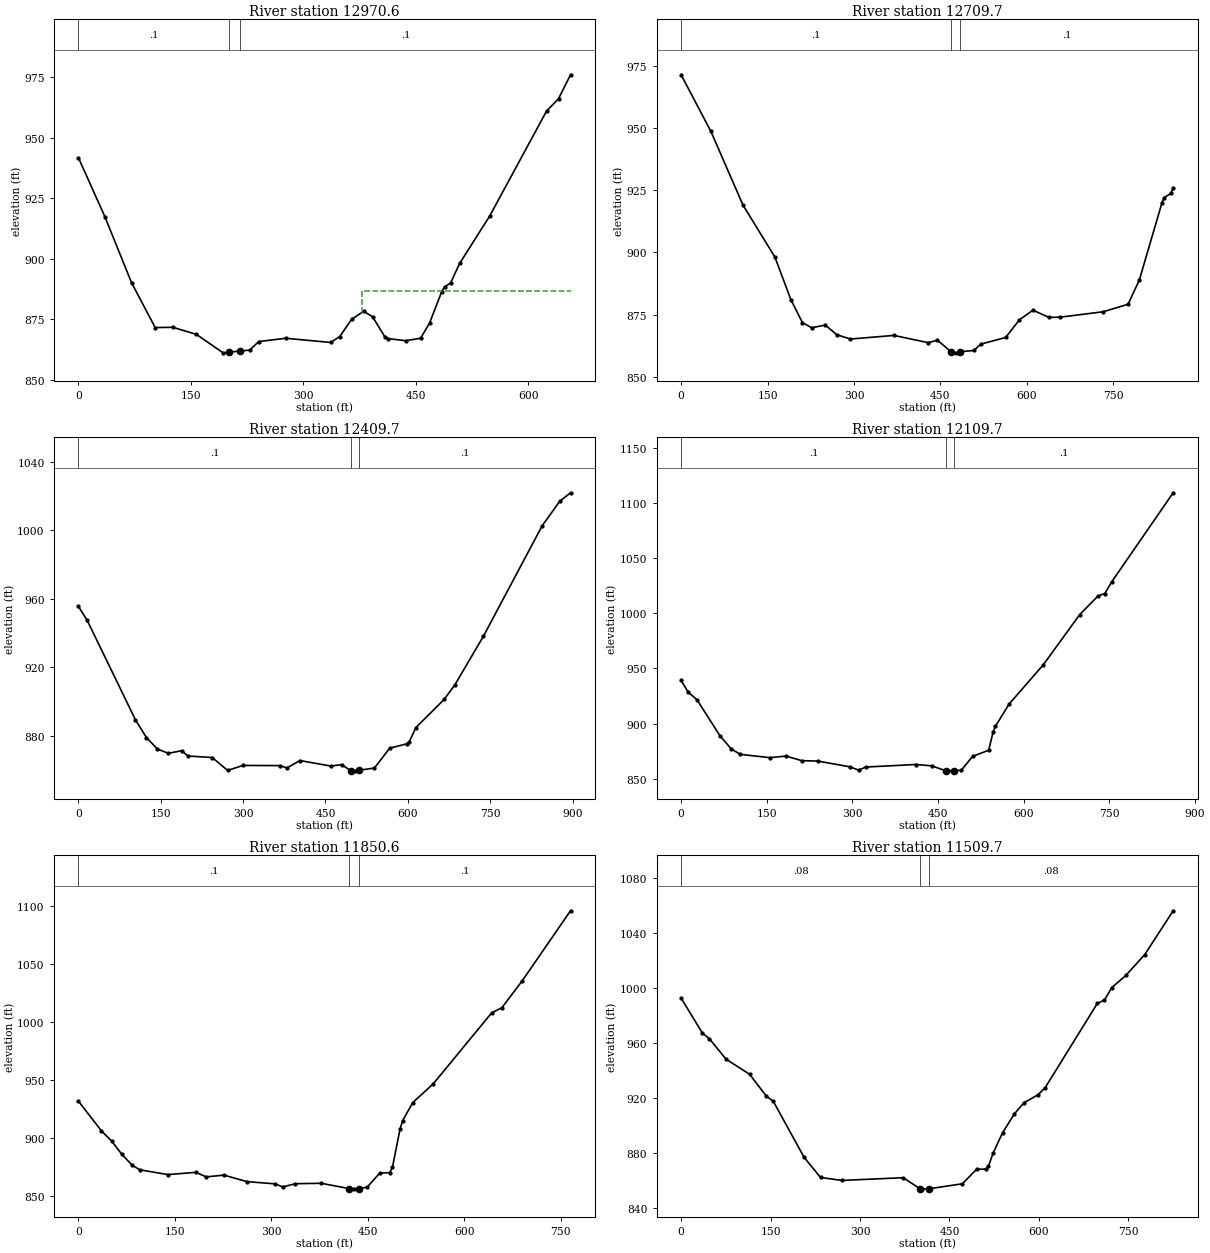
Type RM Length L Ch R = 1 ,12970.6 ,256.6,260.9,265.2
XS GIS Cut Line= 3
     1744361.243      346111.456     1744547.007      346000.345
      1744915.41      345760.257
#Sta/Elev= 30
       0  941.74    35.4  917.25    70.8   890.1   102.3  871.56   125.9  871.68
   157.4  868.74   192.8  861.12   200.6  861.34   215.6  861.89   228.4  862.25
   240.4  865.78   276.4  867.14   336.4  865.41   348.4  867.84   364.4  875.01
   380.4   878.3   392.4  875.97   408.3  867.86   412.3  867.01   436.3  866.14
   456.3  867.15   468.3  873.48   484.3  886.31   488.3  888.39   496.3  889.99
   508.3  898.07   548.2  917.55   624.2  961.01   640.2  966.15   656.2  976.03
#Mann= 3 , 0 , 0
       0      .1       0   200.6    .045       0   215.6      .1       0
#XS Ineff= 2 , 0
                           377.9          886.57
Permanent Ineff=
       F       F
Bank Sta=200.6,215.6
XS Rating Curve= 0 ,0
Exp/Cntr=0.3,0.1

Type RM Length L Ch R = 1 ,12709.7 ,292.5,300,306.5
XS GIS Cut Line= 4
     1744316.327      346358.678     1744749.069      346159.149
      1744965.41      346054.164     1744994.924      345920.484
#Sta/Elev= 30
       0  971.39    51.6  948.69   107.2  919.14   162.8  898.14   190.6  880.99
   210.5  871.87   226.4  869.76   250.2  870.86     270  866.98   293.9  865.24
   369.3  866.69   428.9  863.77   444.8  864.78     469  860.01   476.5  859.69
     484  860.15   508.1  860.63   519.9  863.18   563.2  865.86   586.9  872.91
   610.6  876.84   638.2  873.93   657.9  874.02   732.6   876.2   775.7  879.22
   795.2  888.95   834.3  919.85   838.2  922.03     850  923.74   853.9  926.06
#Mann= 3 , 0 , 0
       0      .1       0     469    .045       0     484      .1       0
Bank Sta=469,484
XS Rating Curve= 0 ,0
Exp/Cntr=0.3,0.1

Type RM Length L Ch R = 1 ,12409.7 ,290.3,300,313.1
XS GIS Cut Line= 3
     1744338.029      346434.481     1744841.427      346427.284
     1745232.912      346393.729
#Sta/Elev= 30
       0   955.6      16  947.45   103.9  889.38   123.9  879.04   143.8  872.41
   163.8  869.87   187.8  871.39   199.8  868.29   243.7  867.42   271.7  859.88
   299.7   862.8   367.6  862.69   379.6  861.31   403.6  865.65   459.5  862.44
   479.5  863.24   495.9  859.77   503.4  859.64   510.9  859.96   539.2  861.28
     567  872.88   598.7  875.45   602.7  876.57   614.6  884.89   666.2  901.34
     686  910.01   737.6  938.16   844.8 1002.76   876.5 1016.94   896.4    1022
#Mann= 3 , 0 , 0
       0      .1       0   495.9    .045       0   510.9      .1       0
Bank Sta=495.9,510.9
XS Rating Curve= 0 ,0
Exp/Cntr=0.3,0.1

Type RM Length L Ch R = 1 ,12109.7 ,251.7,259,264.9
XS GIS Cut Line= 3
     1744316.213      346512.864     1744746.316      346703.956
     1745090.816      346888.784
#Sta/Elev= 30
       0  939.22      12  928.74    27.9  921.53    67.8  889.07    87.8   876.9
   103.7  872.01   155.6     869   183.5  870.44   211.4  866.26   239.3  865.91
   295.2  860.72   311.1  857.66   323.1  860.49   410.8  862.79   438.7   861.6
   463.1  857.15   466.6  857.04   478.1  857.31   490.6  857.58   510.5  870.22
   538.5  875.72   546.4  892.52   550.4  897.56   574.4  917.76   634.2  953.33
     698  998.92     730 1015.81   741.9 1018.02   753.9 1028.55   861.6  1109.5
#Mann= 3 , 0 , 0
       0      .1       0   463.1    .045       0   478.1      .1       0
Bank Sta=463.1,478.1
XS Rating Curve= 0 ,0
Exp/Cntr=0.3,0.1

Type RM Length L Ch R = 1 ,11850.6 ,341.4,341,342.4
XS GIS Cut Line= 3
     1744257.482      346607.534     1744574.485      346896.605
     1744819.982      347126.631
#Sta/Elev= 30
       0  931.46    35.8  905.84    51.6  897.11    67.5  885.63    83.4  876.35
    95.3  872.32     139   868.2   182.7  870.13   198.6  866.24   226.4  867.72
   262.2  862.12   305.9  860.19   317.8  857.55   337.6  860.35   377.4   860.7
   421.5  856.09     429  855.91   436.5  856.16   448.8  857.27   468.6  869.42
   484.4  869.92   488.4  874.51   500.3  907.63   504.2  914.59     520  930.27
   551.7   946.3   642.7 1007.57   658.6    1012   690.2 1035.14   765.4 1095.55
#Mann= 3 , 0 , 0
       0      .1       0   421.5    .045       0   436.5      .1       0
Bank Sta=421.5,436.5
XS Rating Curve= 0 ,0
Exp/Cntr=0.3,0.1

Type RM Length L Ch R = 1 ,11509.7 ,295.1,300,302.7
XS GIS Cut Line= 3
     1743971.754      346785.592     1744279.337       347053.91
     1744565.245      347357.529
#Sta/Elev= 30
       0  992.57    35.7  967.18    47.6  962.98    75.3  948.22   114.9  937.19
   142.7  921.45   154.6  917.56   206.1  876.98   233.8  862.22   269.5  860.07
   372.5  862.03   400.7  854.01   404.2  853.95   415.7     854   471.7  857.64
   495.6  868.18   511.4  868.33   515.4   870.4   523.4   880.1   539.2   894.8
   559.1  908.53     575  916.55   598.8  922.38   610.7  927.58   698.1  988.77
     710  991.14     722 1000.12   745.8 1009.02   777.6 1024.25   825.2 1056.04
#Mann= 3 , 0 , 0
       0     .08       0   400.7    .045       0   415.7     .08       0
Bank Sta=400.7,415.7
XS Rating Curve= 0 ,0
Exp/Cntr=0.3,0.1

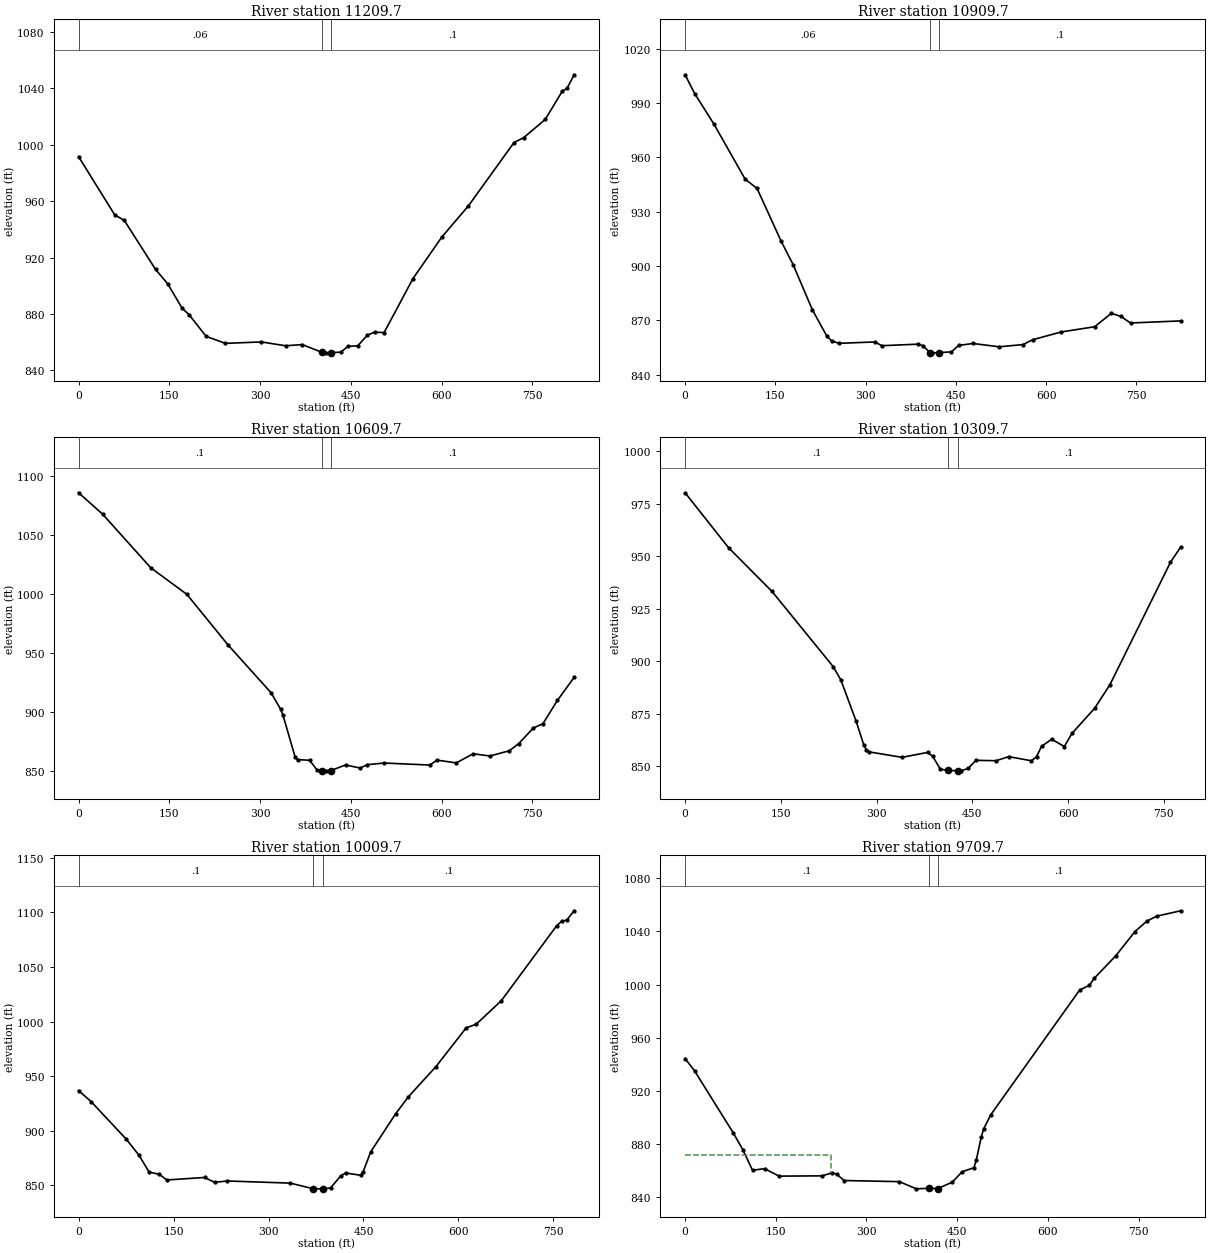
Type RM Length L Ch R = 1 ,11209.7 ,291.3,300,311.1
XS GIS Cut Line= 3
     1743825.817      346936.865     1744069.633       347265.87
     1744313.449      347594.874
#Sta/Elev= 30
       0  991.55    59.6  950.31    75.5  946.37   127.2   911.6   147.1  901.45
     171  884.13   182.9  879.36   210.7  864.15   242.5  859.18   302.2   860.2
   341.9  857.47   369.7  858.32     402  852.83   409.5  852.46     417  852.61
   433.4  852.96   445.3  857.12   461.2  857.41   477.1  864.99     489  867.11
   504.9  866.84   552.6  905.15   600.3  934.61   644.1  956.64   719.6 1001.63
   735.5 1005.03   771.3 1018.05   799.1 1037.85   807.1 1040.06     819 1049.66
#Mann= 3 , 0 , 0
       0     .06       0     402    .045       0     417      .1       0
Bank Sta=402,417
XS Rating Curve= 0 ,0
Exp/Cntr=0.3,0.1

Type RM Length L Ch R = 1 ,10909.7 ,299.4,300,298.2
XS GIS Cut Line= 3
     1743707.045      347009.993     1743810.883      347411.582
     1743871.069       347815.69
#Sta/Elev= 30
       0  1005.7      16  995.26    47.9  978.46    99.7  948.07   119.6  942.88
   159.5   913.8   179.5  900.81   211.4   875.9   235.3  861.41   243.3  858.73
   255.3   857.3   315.1  858.07     327     856   386.9  856.85   394.8  856.06
   407.3  852.08   410.8  852.05   422.3  852.18   442.6   852.6   454.5  856.15
   478.3  857.22   521.9  855.39   561.6  856.63   577.4  859.28     625  863.59
   680.6  866.48   708.3   873.9   724.2  872.17   740.1  868.54   823.4   869.7
#Mann= 3 , 0 , 0
       0     .06       0   407.3    .045       0   422.3      .1       0
Bank Sta=407.3,422.3
XS Rating Curve= 0 ,0
Exp/Cntr=0.3,0.1

Type RM Length L Ch R = 1 ,10609.7 ,295.9,300,305.5
XS GIS Cut Line= 3
     1743421.254       347040.53     1743513.334      347439.544
     1743605.413      347838.557
#Sta/Elev= 30
       0 1085.52    39.8  1067.3   119.3 1021.87   178.9   999.4   246.5  956.74
   318.1  915.94     334  901.87   337.9  896.68   357.8  861.44   361.8  859.26
   381.7  858.72   393.6  850.69     402  849.88   409.5  849.75     417  850.02
   441.3  854.76   465.2   852.1   477.1  854.99   504.9  856.37   580.5  854.67
   592.4  858.83   624.2  856.48     652  864.22   679.8  862.34   711.7  866.75
   727.6  872.93   751.4  886.01   767.3  889.68   791.2  909.41     819  929.05
#Mann= 3 , 0 , 0
       0      .1       0     402    .045       0     417      .1       0
Bank Sta=402,417
XS Rating Curve= 0 ,0
Exp/Cntr=0.3,0.1

Type RM Length L Ch R = 1 ,10309.7 ,284.1,300,313.7
XS GIS Cut Line= 3
     1743200.691      347097.515     1743223.485      347516.669
     1743221.024      347873.159
#Sta/Elev= 30
       0  980.33      68   954.2   135.9  933.42   231.9  897.53   243.9  891.24
   267.9  871.53   279.8   860.3   283.8  857.87   287.8   856.9   339.8  854.29
   379.8  856.62   387.8  854.83   399.8  848.66   412.3  848.04   427.3   847.9
   431.7  847.85   443.5  848.97   455.4  852.87   487.1  852.67   506.9  854.62
   542.6  852.65   550.5  854.55   558.4  859.52   574.3  862.91   594.1  859.42
     606  865.66   641.6  877.66   665.4  888.82   760.4  947.22   776.3  954.45
#Mann= 3 , 0 , 0
       0      .1       0   412.3    .045       0   427.3      .1       0
Bank Sta=412.3,427.3
XS Rating Curve= 0 ,0
Exp/Cntr=0.3,0.1

Type RM Length L Ch R = 1 ,10009.7 ,294.7,300,307.2
XS GIS Cut Line= 3
     1743171.979      347182.621     1742942.463        347483.1
     1742706.698       347812.11
#Sta/Elev= 30
       0  936.83    19.9  926.66    75.6  892.15    95.5  877.52   111.4  862.21
   127.4  860.23   139.3     855     199  857.28   214.9  852.84   234.8  854.09
   334.3  852.13   370.6  846.98   385.6  846.89     386  846.88     398  847.67
   413.8  858.61   421.8  861.43   445.6  859.29   449.5  862.49   461.4  880.72
   501.1  915.86     521  931.18   564.6   958.9   612.2  994.29   628.1  997.63
   667.8 1019.19   755.1 1087.74     763  1091.9     771 1092.95   782.9 1101.55
#Mann= 3 , 0 , 0
       0      .1       0   370.6    .045       0   385.6      .1       0
Bank Sta=370.6,385.6
XS Rating Curve= 0 ,0
Exp/Cntr=0.3,0.1

Type RM Length L Ch R = 1 ,9709.7  ,303.1,300,296.5
XS GIS Cut Line= 3
     1743041.741       347019.95     1742723.712       347279.11
     1742392.642      347519.888
#Sta/Elev= 30
       0  944.26    15.9  934.81    79.7  888.19    95.6  875.49   111.5  860.04
   131.4  861.29   155.3  855.66     227  855.85     243  858.18   250.9  857.04
   262.9  852.34   354.5  851.49   382.4  846.07   402.8  846.45   417.8  846.25
     442  851.12     458  858.87   477.8  862.03   481.8  868.14   489.7  884.83
   493.7  891.15   505.6  901.93   652.7  995.97   668.6  999.38   676.5 1004.65
   712.3 1021.69   744.1 1039.98     764  1047.9   779.9 1051.52   819.6 1055.61
#Mann= 3 , 0 , 0
       0      .1       0   402.8    .045       0   417.8      .1       0
#XS Ineff= 2 , 0
          241.38  871.43
Permanent Ineff=
       F       F
Bank Sta=402.8,417.8
XS Rating Curve= 0 ,0
Exp/Cntr=0.3,0.1

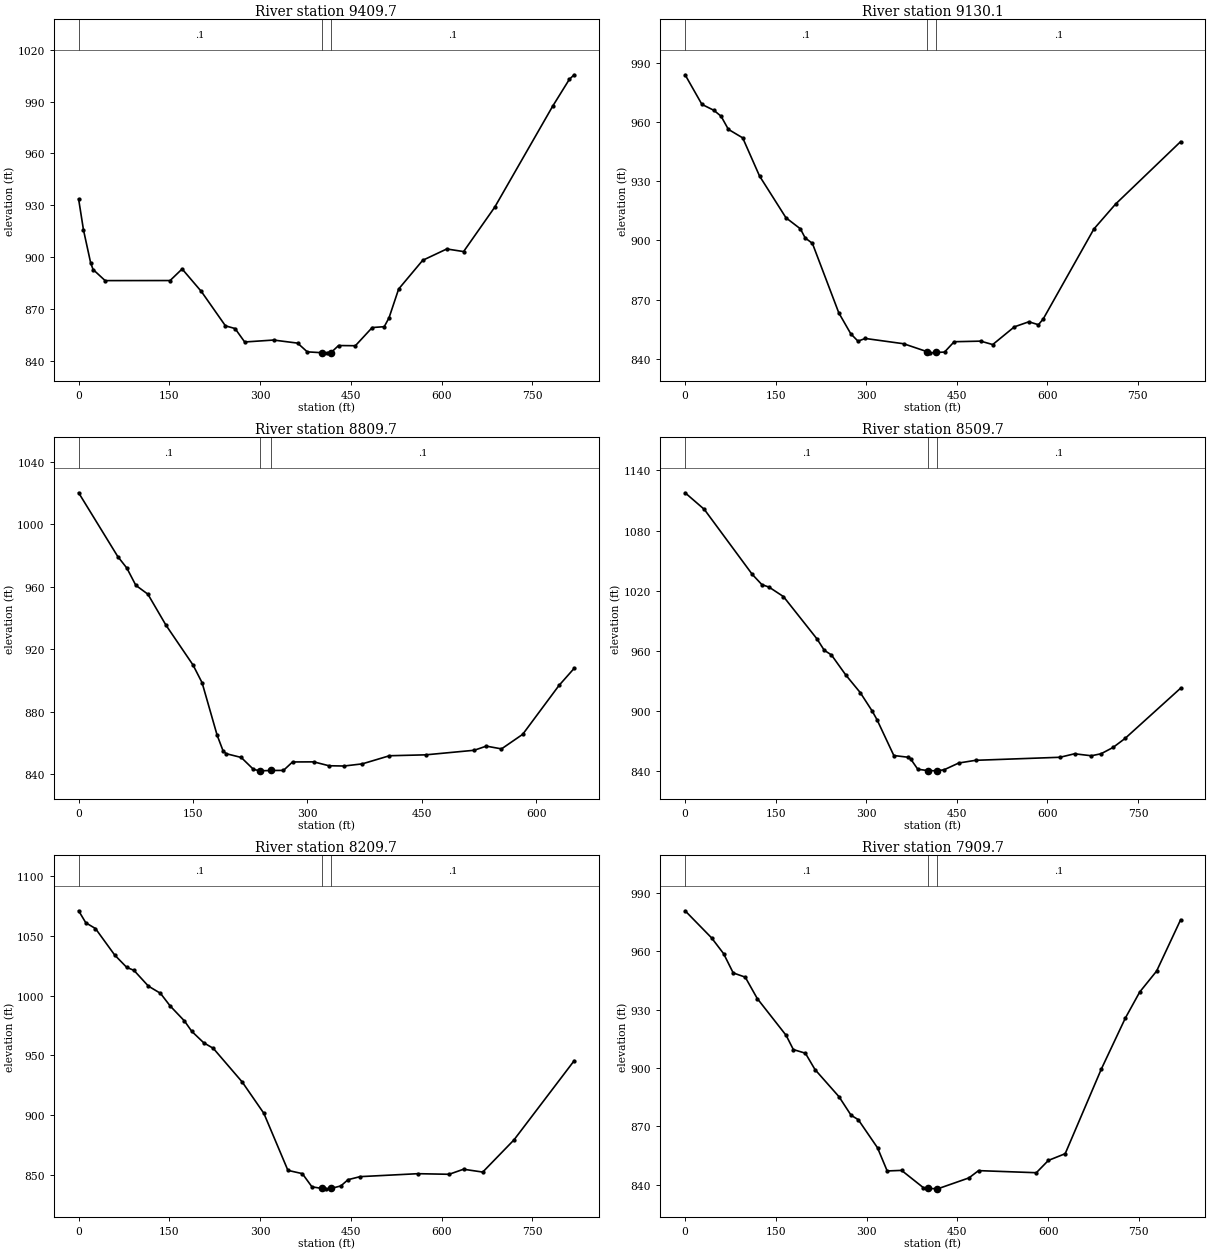
Type RM Length L Ch R = 1 ,9409.7  ,277.8,279.6,278.2
XS GIS Cut Line= 3
     1742786.005      346776.326     1742506.193      347075.705
     1742216.669      347365.231
#Sta/Elev= 30
       0  933.54       8  915.74    19.9  896.63    23.9  892.81    43.8   886.4
   151.2  886.44   171.1  893.14   202.9   880.1   242.7  860.23   258.6  858.67
   274.5  850.89   322.3  852.01     362  850.23     378  845.18   402.3  844.68
   409.8  844.61   417.3  844.78   429.7  848.84   457.5  848.72   485.3  859.24
   505.2  859.74   513.1  864.85     529  881.52   568.8  898.15   608.6  904.71
   636.4   903.2     688  928.96   783.5  987.22   811.3  1002.9   819.2 1005.49
#Mann= 3 , 0 , 0
       0      .1       0   402.3    .045       0   417.3      .1       0
Bank Sta=402.3,417.3
XS Rating Curve= 0 ,0
Exp/Cntr=0.3,0.1

Type RM Length L Ch R = 1 ,9130.1  ,339.4,320.4,302.4
XS GIS Cut Line= 3
     1742605.279      346619.224     1742300.479      346887.497
     1742025.802      347198.991
#Sta/Elev= 30
       0  984.09    27.9  969.06    47.8  966.04    59.7  963.03    71.7   956.4
    95.5  952.06   123.4   932.7   167.2  911.51   191.1   905.9     199  901.29
     211  898.53   254.8  863.23   274.7   852.6   286.6  848.89   298.6  850.26
   362.3  847.57   401.3  843.53     406  842.96   416.3  843.18     430  843.34
     446   848.6   489.9   848.9   509.9  847.16   545.8  856.16   569.8  858.72
   585.7  857.23   593.7   860.2   677.6  905.81   713.5  918.45   821.4  950.16
#Mann= 3 , 0 , 0
       0      .1       0   401.3    .045       0   416.3      .1       0
Bank Sta=401.3,416.3
XS Rating Curve= 0 ,0
Exp/Cntr=0.3,0.1

Type RM Length L Ch R = 1 ,8809.7  ,304.3,300,295.5
XS GIS Cut Line= 3
     1742062.632      346451.734     1742062.737       346696.53
     1742081.729      347101.039
#Sta/Elev= 30
       0  1020.3    51.3  979.47    63.2  972.09      75  961.02    90.8  955.35
   114.5  935.52     150  909.99   161.9  898.62   181.6  865.04   189.5  854.87
   193.5  853.18   213.2  850.76     229  843.25   236.9  842.19   237.3   842.2
   252.3  842.41   268.6  842.47   280.5  847.88   308.3  847.94   328.2  845.45
     348  845.28   371.8  846.64   407.6  851.86   455.2  852.44   518.7  855.37
   534.6  858.02   554.5  856.25   582.3  865.58   629.9  896.88   649.8  907.86
#Mann= 3 , 0 , 0
       0      .1       0   237.3    .045       0   252.3      .1       0
Bank Sta=237.3,252.3
XS Rating Curve= 0 ,0
Exp/Cntr=0.3,0.1

Type RM Length L Ch R = 1 ,8509.7  ,302.6,300,298.9
XS GIS Cut Line= 3
     1741700.743      346364.531     1741772.402       346767.35
     1741870.538      347166.786
#Sta/Elev= 30
       0 1117.72    31.8 1101.14   111.2 1036.18   127.1 1025.95     139 1023.44
   162.9 1013.96   218.5  971.58   230.4  960.34   242.3  955.65   266.1  935.59
     290  918.03   309.8  899.57   317.8   890.9   345.6  855.14   369.4  853.41
   373.4  851.77   385.3  841.42   401.6  840.12   416.6  839.84   417.1  839.83
   429.1  840.96   453.1  847.65     481  850.35   620.8  853.39   644.8  856.87
   672.7   854.9   688.7  856.89   708.6   863.2   728.6  872.27   820.5  922.45
#Mann= 3 , 0 , 0
       0      .1       0   401.6    .045       0   416.6      .1       0
Bank Sta=401.6,416.6
XS Rating Curve= 0 ,0
Exp/Cntr=0.3,0.1

Type RM Length L Ch R = 1 ,8209.7  ,303.6,300,296.7
XS GIS Cut Line= 3
     1741367.269       346456.05     1741484.631      346848.372
     1741601.992      347240.694
#Sta/Elev= 30
       0 1070.79    11.9 1060.73    27.8 1055.97    59.6 1033.84    79.5 1023.52
    91.4 1021.05   115.3 1007.88   135.2 1001.89   151.1  991.42   174.9  978.78
   186.9  970.17   206.7  960.58   222.6  955.91   270.4  927.79   306.1  901.68
   345.9  854.02   369.7   851.3   385.6  840.29     402  838.92   409.5   838.6
     417  838.91   433.4  841.04   445.3  846.25   465.2  848.78   560.6  851.25
   612.3  850.75   636.1  854.96   667.9   852.6   719.6  879.52     819  945.59
#Mann= 3 , 0 , 0
       0      .1       0     402    .045       0     417      .1       0
Bank Sta=402,417
XS Rating Curve= 0 ,0
Exp/Cntr=0.3,0.1

Type RM Length L Ch R = 1 ,7909.7  ,295.5,300,303.2
XS GIS Cut Line= 3
     1741021.778      346576.252     1741200.861      346944.506
     1741374.571      347315.395
#Sta/Elev= 30
       0  980.83    43.7  966.92    63.6   958.8    79.5  948.87    99.4  946.69
   119.3  935.67     167  916.74   178.9  909.44   198.8  907.57   214.7  899.16
   254.4  885.18   274.3  875.66   286.2  873.38     318  858.93     334     847
   357.8  847.29   393.6  838.45     402     838     417  837.83   417.4   837.8
   469.1  843.42     485  847.17   580.5  846.09   600.4  852.42   628.2  855.88
   687.8  899.33   727.6  925.63   751.4  939.06   779.3  949.82     819  976.22
#Mann= 3 , 0 , 0
       0      .1       0     402    .045       0     417      .1       0
Bank Sta=402,417
XS Rating Curve= 0 ,0
Exp/Cntr=0.3,0.1

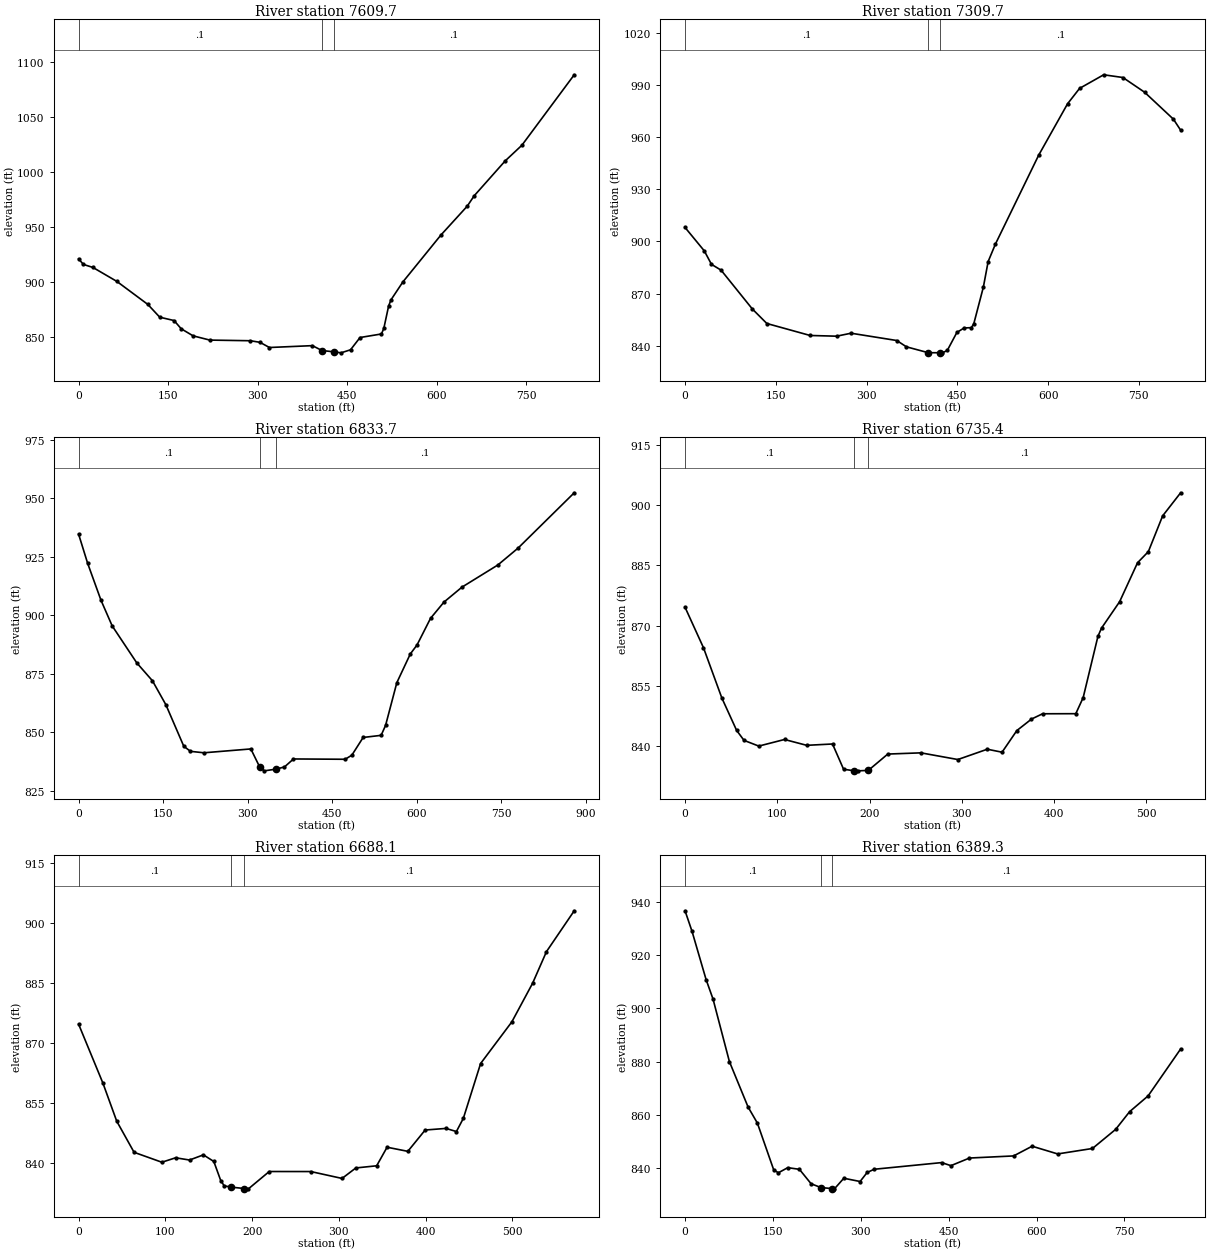
Type RM Length L Ch R = 1 ,7609.7  ,292.6,300,308.2
XS GIS Cut Line= 3
     1740829.503      346673.127     1740936.122       347083.15
     1741054.206      347472.421
#Sta/Elev= 30
       0  921.12       8  916.12      24  913.35      64  900.69   115.9  879.77
   135.9  868.15   159.9   865.1   171.9   857.6   191.8  851.18   219.8  847.33
   287.8  846.74   303.8  845.31   319.7  840.59   391.7  842.28   407.7  837.85
   427.6  836.66   439.6  835.74   455.6  838.52   471.5  849.67   507.4   852.9
   511.4  858.05   519.4  878.35   523.4  883.94   543.3  900.21   607.1  942.87
     651     969   662.9  978.59   714.8 1010.28   742.7 1024.45   830.4 1088.52
#Mann= 3 , 0 , 0
       0      .1       0   407.7    .045       0   427.6      .1       0
Bank Sta=407.7,427.6
XS Rating Curve= 0 ,0
Exp/Cntr=0.3,0.1

Type RM Length L Ch R = 1 ,7309.7  ,476.9,475.9,474.2
XS GIS Cut Line= 3
     1740667.336      346667.906     1740638.559      347076.393
     1740609.782      347484.881
#Sta/Elev= 30
       0  908.06    31.8   894.6    43.7  886.84    59.6  883.48   111.3  861.12
   135.2   852.8   206.7  845.91   250.5   845.5   274.3  847.21   349.9  843.01
   365.8  839.39     402  835.99   421.4  835.98   425.4  835.92   433.4  837.32
   449.3  847.69   461.2  850.23   473.1  850.41   477.1  852.56     493  873.74
   500.9  888.44   512.9  898.48   584.4  949.64   632.1   979.2     652  988.08
   691.8  995.91   723.6  994.34   759.4  985.88   807.1  970.35     819  964.03
#Mann= 3 , 0 , 0
       0      .1       0     402    .045       0   421.4      .1       0
Bank Sta=402,421.4
XS Rating Curve= 0 ,0
Exp/Cntr=0.3,0.1

Type RM Length L Ch R = 1 ,6833.7  ,99.8,98.3,97.3
XS GIS Cut Line= 4
     1740191.973      346612.613      1740184.16      346945.947
     1740181.886      347268.866      1740246.66      347482.405
#Sta/Elev= 30
       0  934.63    15.9  922.27    39.7  906.39    59.5  895.46   103.2  879.61
     131  871.96   154.8  861.73   186.6  843.96   198.5  841.78   222.3  841.16
   305.6  842.81   321.5  834.99   329.5  833.44   350.4  834.17   365.3  835.11
   381.3  838.52     473  838.39   484.9  840.15   504.9  847.72   536.8  848.62
   544.7  852.87   564.7  871.17   588.6  883.44   600.5  887.27   624.5  898.68
   648.4  905.64   680.3  912.02     744   921.5   779.9  928.73   879.5  952.38
#Mann= 3 , 0 , 0
       0      .1       0   321.5    .045       0   350.4      .1       0
Bank Sta=321.5,350.4
XS Rating Curve= 0 ,0
Exp/Cntr=0.3,0.1

Type RM Length L Ch R = 1 ,6735.4  ,47.4,47.4,47.4
XS GIS Cut Line= 3
     1740078.257      346750.345     1740099.091      347205.206
     1740163.327      347255.553
#Sta/Elev= 30
       0  874.58      20  864.51    39.9  852.02    55.9  843.98    63.9   841.5
    79.9  840.08   107.8  841.72   131.8  840.27   159.8   840.6   171.8  834.32
   183.6  833.94   187.7  833.93   198.6  834.04   219.7   838.1   255.6   838.4
   295.6  836.74   327.5   839.3   343.5  838.56   359.5  843.93   375.4  846.79
   387.4  848.11   423.4  848.13   431.4  852.13   447.4  867.36   451.3   869.4
   470.9  875.96   490.3  885.63     502  888.39   517.5  897.28     537  903.02
#Mann= 3 , 0 , 0
       0      .1       0   183.6    .045       0   198.6      .1       0
Bank Sta=183.6,198.6
XS Rating Curve= 0 ,0
Exp/Cntr=0.3,0.1

Type RM Length L Ch R = 1 ,6688.1  ,301.9,298.7,295.7
XS GIS Cut Line= 3
     1740031.382      346753.817     1740052.216      347208.678
     1740140.757      347283.331
#Sta/Elev= 30
       0  874.76      28  860.04    43.9  850.54    63.9  842.76    95.9  840.28
   111.8  841.39   127.8  840.83   143.8  842.12   155.8  840.47   163.8  835.69
   167.8  834.37   176.1  834.05   191.1  833.71   195.7  833.63   219.7  837.96
   267.6  837.95   303.6  836.23   319.5  838.85   343.5  839.39   355.5  844.03
   379.4     843   399.4  848.33   423.4  848.73   435.4  847.95   443.4  851.25
   463.3  864.95   499.3  875.36   523.2     885   539.2  892.91   571.2  903.12
#Mann= 3 , 0 , 0
       0      .1       0   176.1    .045       0   191.1      .1       0
Bank Sta=176.1,191.1
XS Rating Curve= 0 ,0
Exp/Cntr=0.3,0.1

Type RM Length L Ch R = 1 ,6389.3  ,979.5,981.7,983.5
XS GIS Cut Line= 4
     1739710.202      346763.655     1739782.652      347147.368
     1739822.843      347401.571     1739978.431      347524.072
#Sta/Elev= 30
       0  936.62      12  928.87    35.9  910.85    47.8   903.5    75.7  880.09
   107.6  863.04   123.5     857   151.4  839.44   159.4  838.39   175.3   840.3
   195.2  839.68   215.2  834.26     232  832.84     251  832.46     255  832.36
     271  836.33   298.8  835.11   310.8  838.49   322.8   839.7     438   842.2
   453.8  841.05   485.5  843.91   560.8   844.7   592.4  848.34     636  845.45
   695.4  847.49     735  854.66   758.8  861.29   790.4  867.21   845.9   884.8
#Mann= 3 , 0 , 0
       0      .1       0     232    .045       0     251      .1       0
Bank Sta=232,251
XS Rating Curve= 0 ,0
Exp/Cntr=0.3,0.1