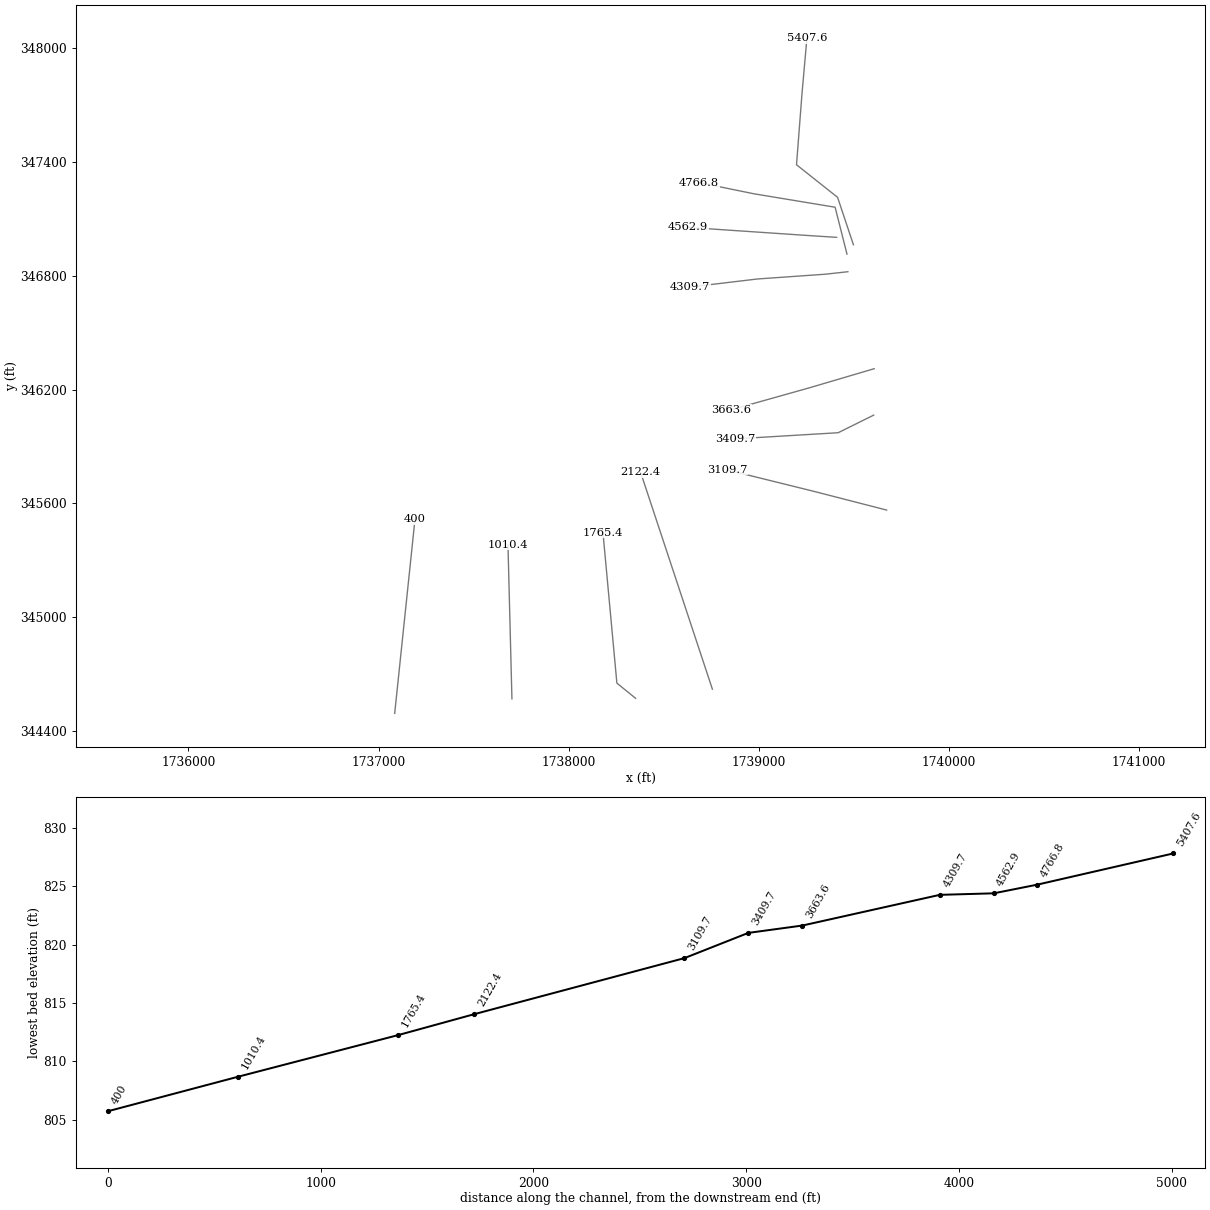
HEC-RAS study SPLAURFK.prj: SPLAURFK

--- SPLAURFK.g01 (geometry) --- (continued)

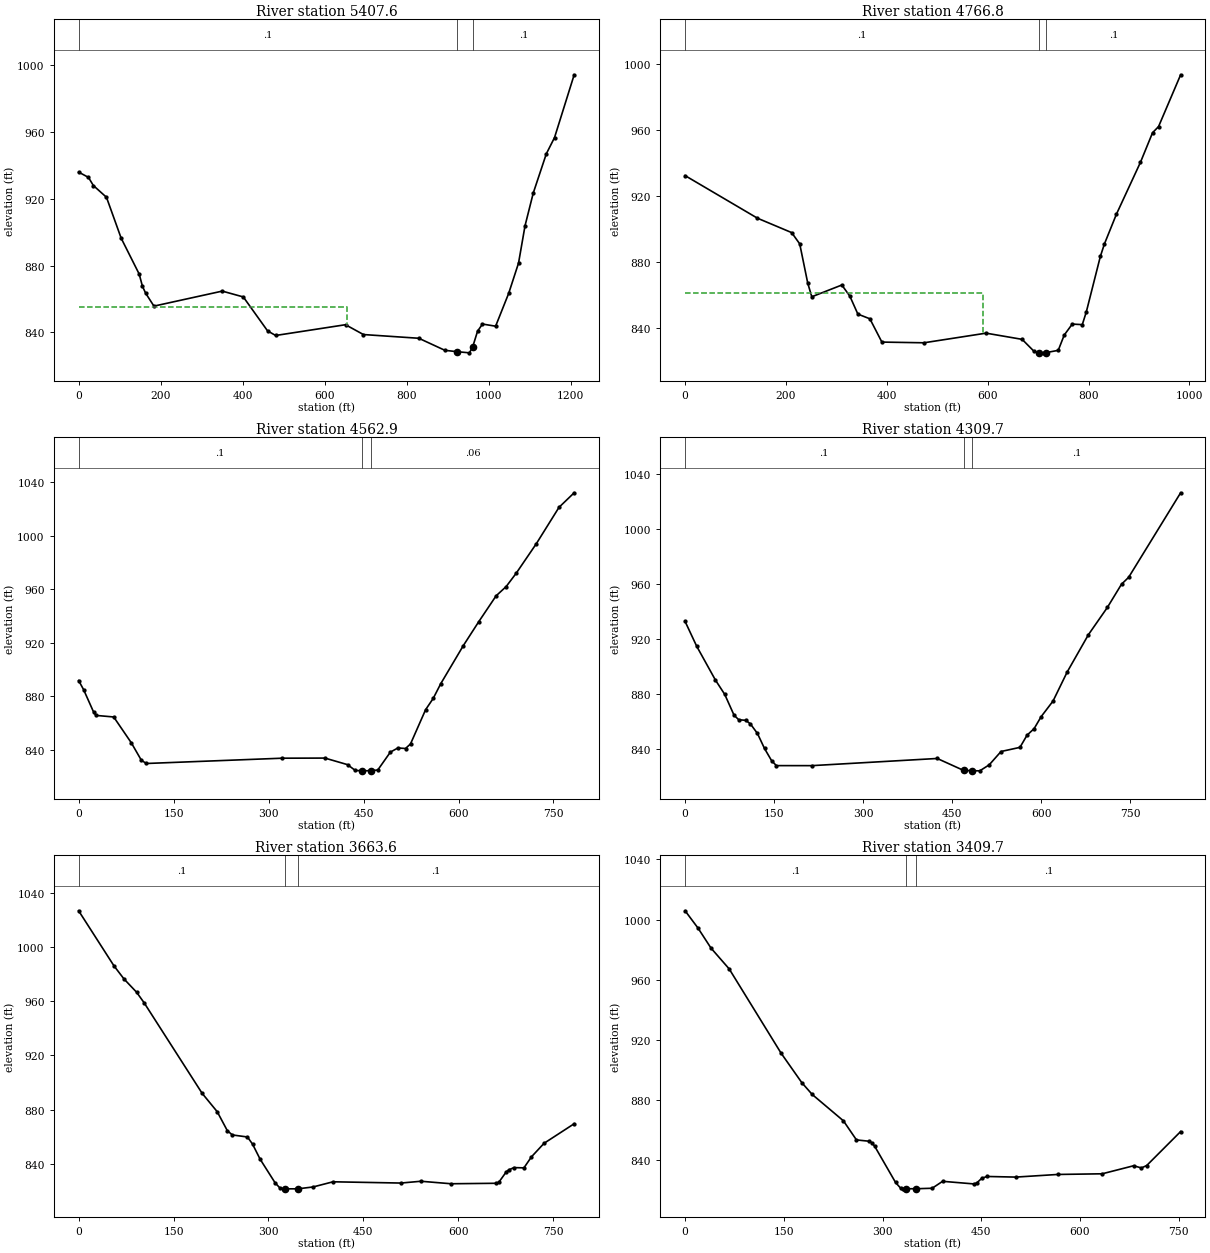
Type RM Length L Ch R = 1 ,5407.6  ,607.6,640.8,674.2
XS GIS Cut Line= 5
     1739499.264      346964.176     1739415.931      347214.176
     1739199.785      347386.051     1739228.431      347758.447
     1739254.473      348052.717
#Sta/Elev= 30
       0  936.09      24  932.92    35.9  928.05    67.9  921.01   103.8  896.46
   147.7     875   155.7  867.63   163.7  863.44   183.7   855.8   350.3  864.79
   401.6   861.3   460.8  840.97   480.5  838.21   650.9  844.66   694.6  838.77
   829.7  836.54   893.3  829.32   921.9  828.53   953.1  827.81   961.1  831.39
     973   840.8     985  845.06    1017  843.77  1048.9  863.45  1072.9  881.57
  1088.8     904  1108.8  923.54  1140.7  947.07  1160.7  956.79  1208.6   994.4
#Mann= 3 , 0 , 0
       0      .1       0   921.9    .045       0   961.1      .1       0
#XS Ineff= 2 , 0
          654.49  855.14
Permanent Ineff=
       F       F
Bank Sta=921.9,961.1
XS Rating Curve= 0 ,0
Exp/Cntr=0.3,0.1

Type RM Length L Ch R = 1 ,4766.8  ,201,203.9,206.9
XS GIS Cut Line= 4
      1739465.41      346914.697      1739402.91      347162.092
     1738975.786      347232.917     1738687.259      347291.934
#Sta/Elev= 30
       0  932.36   143.5  906.59   211.3  897.88   227.3  891.05   243.2  867.29
   251.2  859.05   310.8  866.17   326.7  859.42   342.6  848.56   366.4  845.73
   390.2  831.64   473.6  831.21   596.8  837.04   668.3  833.29   692.1  825.98
   700.8  825.26     712  825.13   715.8  825.28   739.9  826.64   751.8   835.9
   767.7  842.53   787.6  842.19   795.6  849.93   823.4  883.46   831.4  890.96
   855.3  909.04     903  940.47   926.9   958.3   938.8  962.03   982.6  993.37
#Mann= 3 , 0 , 0
       0      .1       0   700.8    .045       0   715.8      .1       0
#XS Ineff= 2 , 0
          590.16  861.14
Permanent Ineff=
       F       F
Bank Sta=700.8,715.8
XS Rating Curve= 0 ,0
Exp/Cntr=0.3,0.1

Type RM Length L Ch R = 1 ,4562.9  ,250.1,253.2,257.4
XS GIS Cut Line= 3
     1739410.723      347003.238     1739288.327      347011.051
     1738629.822      347055.629
#Sta/Elev= 30
       0  891.89     7.9  885.04    23.7  868.27    27.7  865.82    55.4  864.66
    83.1  845.43    98.9  832.44   106.8  829.88   321.4  833.84     389  833.93
   424.8  829.01   436.8  824.72   447.5  824.39   462.5  824.53   472.5  825.02
   492.4  838.39   504.3   841.5   516.3  841.09   524.2   844.5   548.1  870.16
     560  878.49   571.9  889.48   607.7  918.08   631.6  935.62   659.4  955.22
   675.3  962.16   691.2  972.16     723  994.26   758.8 1021.42   782.7 1032.27
#Mann= 3 , 0 , 0
       0      .1       0   447.5    .045       0   462.5     .06       0
Bank Sta=447.5,462.5
XS Rating Curve= 0 ,0
Exp/Cntr=0.3,0.1

Type RM Length L Ch R = 1 ,4309.7  ,641.2,646,649.6
XS GIS Cut Line= 4
     1739470.156      346821.943     1739352.968      346808.923
     1738995.181      346783.714     1738639.427      346741.214
#Sta/Elev= 30
       0  932.98    19.6  914.89    51.1  890.33    66.8   879.9    82.5  864.72
    90.4  861.45   102.2  861.03     110  858.43   121.9  851.46   133.8  840.52
   145.8  831.61   153.8  828.06   213.6  828.04   424.8  833.26   469.1  824.59
   484.1  824.33   496.5  824.26   512.4  828.63   532.3  838.33   564.2  841.35
   576.1   850.2     588  854.95     600  863.77   619.9  875.05   643.8  896.24
   679.6  923.41   711.5  943.21   735.3   960.1   747.3  965.11   834.9 1026.64
#Mann= 3 , 0 , 0
       0      .1       0   469.1    .045       0   484.1      .1       0
Bank Sta=469.1,484.1
XS Rating Curve= 0 ,0
Exp/Cntr=0.3,0.1

Type RM Length L Ch R = 1 ,3663.6  ,259,254,249.1
XS GIS Cut Line= 3
     1739608.639       346310.53     1739264.889      346208.967
     1738855.999      346093.888
#Sta/Elev= 30
       0  1026.7    55.8  986.12    71.7  976.41    91.6  966.64   103.6  958.78
   195.2  892.07     219  878.54     235  864.54   242.9  861.38   266.8  859.87
   274.8  854.68   286.8  843.53   310.6  826.01   318.6  822.05   326.6  821.63
   346.5  821.65   370.4     823   402.1  826.83   509.3   825.9     541  827.22
   588.7  825.38   660.2  825.73   664.1  826.48     676  834.23     680  835.63
   687.9  837.29   703.8   837.1   715.7  845.23   735.6  855.22   783.2  869.64
#Mann= 3 , 0 , 0
       0      .1       0   326.6    .045       0   346.5      .1       0
Bank Sta=326.6,346.5
XS Rating Curve= 0 ,0
Exp/Cntr=0.3,0.1

Type RM Length L Ch R = 1 ,3409.7  ,307,300,293.2
XS GIS Cut Line= 4
     1739606.035      346065.738      1739418.95      345972.879
       1739284.5      345964.812     1738875.735      345940.287
#Sta/Elev= 30
       0 1005.85    19.7   994.3    39.4  981.02      67   967.2   145.8  911.24
   177.3  891.62   193.1  883.76   240.6  866.21   260.4  853.52   280.2  852.62
   284.1   851.5   288.1   849.3   319.8  825.24   327.7  821.35   331.7     821
   336.1  821.06   351.1  821.07   375.4  821.39   391.3     826     439  824.26
     443  824.83   450.9  828.05   458.8  829.22   502.6  828.81   566.2  830.56
   633.8     831   681.5  836.34   693.4   834.9   701.4  836.49     753  859.09
#Mann= 3 , 0 , 0
       0      .1       0   336.1    .045       0   351.1      .1       0
Bank Sta=336.1,351.1
XS Rating Curve= 0 ,0
Exp/Cntr=0.3,0.1

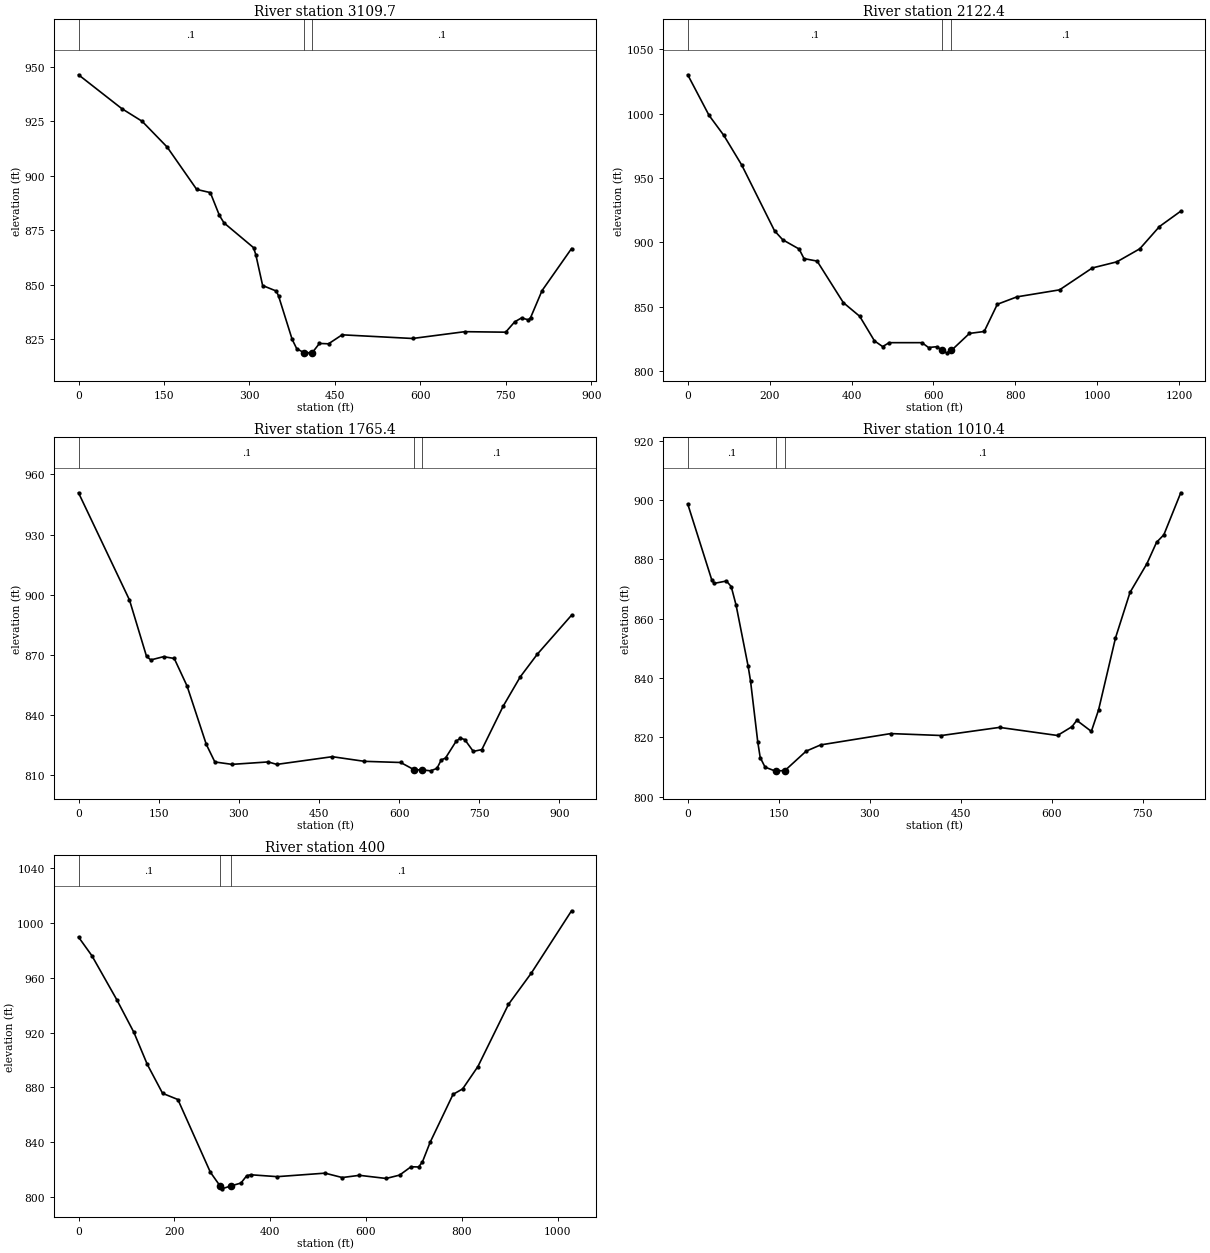
Type RM Length L Ch R = 1 ,3109.7  ,1010.3,987.2,963.9
XS GIS Cut Line= 3
      1739674.08      345564.981     1739283.987      345665.519
     1738835.202      345776.676
#Sta/Elev= 30
       0   946.3    75.8  930.82   111.7  924.97   155.6  913.15   207.4  893.75
   231.3  892.29   247.3  881.81   255.3  878.41   307.1  867.07   311.1  863.87
   323.1   849.7     347  847.17     351  844.95   374.9  825.02   382.9  820.76
   395.3  818.95   398.8  818.84   410.3  818.97   422.8  823.15   438.7  822.98
   462.6   827.1   586.2  825.42   677.9  828.54   749.6  828.31   765.5  833.07
   777.5  834.85   789.5  833.96   793.4  835.03   813.4  847.35   865.2  866.64
#Mann= 3 , 0 , 0
       0      .1       0   395.3    .045       0   410.3      .1       0
Bank Sta=395.3,410.3
XS Rating Curve= 0 ,0
Exp/Cntr=0.3,0.1

Type RM Length L Ch R = 1 ,2122.4  ,362.1,357,351.9
XS GIS Cut Line= 2
     1738757.077      344620.426     1738379.473      345763.655
#Sta/Elev= 30
       0 1030.21      52   998.7      88  983.16     132  959.98     212  908.92
     232  901.95     272  894.75     284  887.29     316  885.36     380  853.07
     420  842.45     456  823.33     476   818.9     492  821.94     572  821.95
     588  818.17     608  818.81   621.9  815.93     632  814.04     644  815.96
     688  829.14     724  830.63     756  851.78     804  857.57     908     863
     988  880.03    1048  884.79    1104  894.94    1152  912.24    1204  924.18
#Mann= 3 , 0 , 0
       0      .1       0   621.9    .045       0     644      .1       0
Bank Sta=621.9,644
XS Rating Curve= 0 ,0
Exp/Cntr=0.3,0.1

Type RM Length L Ch R = 1 ,1765.4  ,757.4,755,752.4
XS GIS Cut Line= 3
     1738353.219      344572.074     1738254.464      344652.341
     1738181.344       345444.47
#Sta/Elev= 30
       0  950.84    95.4  897.41   127.3  869.31   135.3  867.53   159.2  869.15
   179.2  868.26   203.2  854.52   239.2  825.42   255.2  816.67   287.2  815.48
   355.1  816.69   371.1  815.46     475   819.3     535  816.99     603  816.41
   628.5  812.74   643.5  812.73   658.9  812.25   670.9  813.48   678.9  817.68
   686.9  818.63   706.9  827.05   714.9  828.55   722.9  827.83   738.9  821.94
   754.9  822.84   794.8  844.47   826.8  859.09   858.8  870.42   922.8  889.82
#Mann= 3 , 0 , 0
       0      .1       0   628.5    .045       0   643.5      .1       0
Bank Sta=628.5,643.5
XS Rating Curve= 0 ,0
Exp/Cntr=0.3,0.1

Type RM Length L Ch R = 1 ,1010.4  ,613.3,610.5,607.6
XS GIS Cut Line= 2
     1737702.177       344569.47     1737681.344       345381.97
#Sta/Elev= 30
       0  898.72    39.8  872.99    43.8  871.93    63.8  872.72    71.7  870.84
    79.7  864.61    99.6  843.96   103.6  838.91   115.5  818.36   119.5  813.16
   127.5  809.92   143.4  808.67   145.1  808.67   160.1  808.74   195.2  815.31
   219.1  817.42   334.7  821.24   418.3  820.59     514  823.33   609.6   820.6
   633.5  823.58   641.4   825.7   665.4  821.98   677.3  829.23   705.2  853.51
   729.1  868.86     757  878.57   772.9  885.78   784.9  888.31   812.8  902.49
#Mann= 3 , 0 , 0
       0      .1       0   145.1    .045       0   160.1      .1       0
Bank Sta=145.1,160.1
XS Rating Curve= 0 ,0
Exp/Cntr=0.3,0.1

Type RM Length L Ch R = 1 ,400     ,413.9,400,386
XS GIS Cut Line= 2
     1737085.202      344492.822     1737191.973      345516.259
#Sta/Elev= 30
       0  989.83    27.9  976.21    79.8  944.06   115.7  920.05   143.6  896.67
   175.5  875.55   207.4  871.03   275.2  817.87   295.1  808.02   299.1  805.72
   318.5  807.89     339  809.95     351  815.26     359  816.02   414.8  814.63
   514.5  817.19   550.4  813.98   586.3   815.6   642.1  813.31     670  815.75
     694  821.86   709.9  821.71   717.9  825.52   733.8  839.71   781.7  874.82
   801.7  878.79   833.6  895.17   897.4  940.64   945.2  963.55    1029 1009.04
#Mann= 3 , 0 , 0
       0      .1       0   295.1    .045       0   318.5      .1       0
Bank Sta=295.1,318.5
XS Rating Curve= 0 ,0
Exp/Cntr=0.3,0.1

Chan Stop Cuts=-1
Use User Specified Reach Order=0
Composite Channel Slope=5